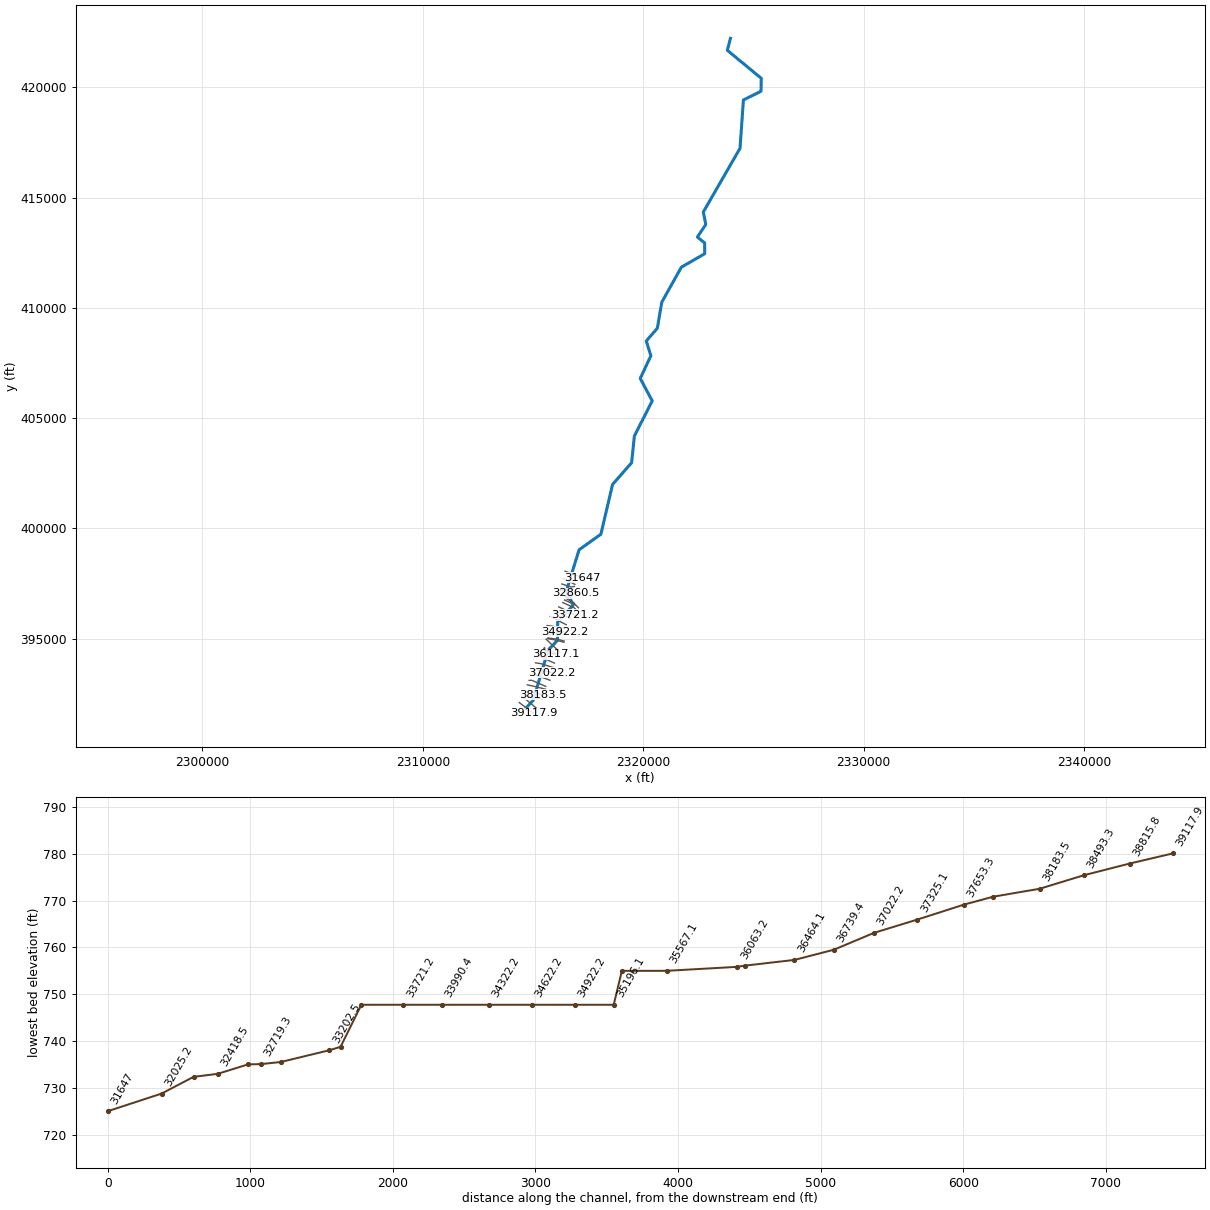
--- SIRJOHNSRN.prj (project) ---

Proj Title=SIRJOHNSRN
Current Plan=p01
Default Exp/Contr=0,0
English Units
Geom File=g01
Flow File=f01
Plan File=p01
BEGIN DESCRIPTION:
END DESCRIPTION:
DSS Export Rating Curves= 0
DSS Export Rating Curve Sorted= 0
DSS Export Volume Flow Curves= 0
DXF OffsetX= 0
DXF OffsetY= 0
DXF ScaleX= 0
DXF ScaleY= 0

--- SIRJOHNSRN.p01 (plan) ---

Plan Title=Floodplain
Program Version=4.00
Geom File=g01
Flow File=f01
K Sum by GR=0
Std Step Tol=0.01
Critical Tol=0.01
Num of Std Step Trials=20
Max Error Tol=0.3
Flow Tol Ratio=0.001
Split Flow NTrial=30
Split Flow Tol=0.02
Split Flow Ratio=0.02
Log Output Level=0
Friction Slope Method=1
Unsteady Friction Slope Method=2
Unsteady Bridges Friction Slope Method=1
Global Log Level=0
CheckData=False
Run HTab=0
Run UNet=0
Run PostProcess=0
UNET Theta=0
UNET Theta Warmup=0
UNET ZTol=0
UNET ZSATol=0
UNET MxIter=0
UNET MaxInSteps=0
UNET DtIC=0
UNET DtMin=0
UNET MaxCRTS=0
UNET WFStab=0
UNET SFStab=0
UNET WFX=0
UNET SFX=0
UNET DSS MLevel=0
UNET DZMax Abort=0
UNET Convert EG Bridges=0
UNET Use Existing IB Tables=0
UNET Froude Limit=0
UNET Froude Power=0
Write IC File=0
Echo Input=False
Echo Output=False
Write Detailed=0

--- SIRJOHNSRN.f01 (steady flow) ---

Flow Title=NFF Regression Equation
Program Version=4.00
Number of Profiles=1
Profile Names=P100yr
River Rch & RM=SIRJOHNSRN,Main      ,39117.9
544.3133
River Rch & RM=SIRJOHNSRN,Main      ,37653.3
590.2151
River Rch & RM=SIRJOHNSRN,Main      ,37022.2
642.5860
River Rch & RM=SIRJOHNSRN,Main      ,36117.1
696.4550
River Rch & RM=SIRJOHNSRN,Main      ,33990.4
769.8112
River Rch & RM=SIRJOHNSRN,Main      ,32249.5
850.1646
River Rch & RM=SIRJOHNSRN,Main      ,31647
897.3177
River Rch & RM=SIRJOHNSRN,Main      ,29550.4
995.5705
River Rch & RM=SIRJOHNSRN,Main      ,26458.1
1058.175
River Rch & RM=SIRJOHNSRN,Main      ,24425.9
1163.260
River Rch & RM=SIRJOHNSRN,Main      ,22001.8
1261.646
River Rch & RM=SIRJOHNSRN,Main      ,18984.3
1396.846
River Rch & RM=SIRJOHNSRN,Main      ,13908.1
1515.075
River Rch & RM=SIRJOHNSRN,Main      ,6747.3
1682.620
River Rch & RM=SIRJOHNSRN,Main      ,439.3
1865.418
River Rch & RM=SIRJOHNSRN,Main      ,126
1865.626
Boundary for River Rch & Prof#=SIRJOHNSRN,Main      ,1
Up Type=0
Dn Type=3
Dn Slope=0.010321

--- SIRJOHNSRN.g01 (geometry) ---

Geom Title=USGS 10m DEM
Program Version=4.10

River Reach=SIRJOHNSRN      ,Main
Reach XY= 30
     2314680.672      391857.324     2315010.053      392204.802
     2315686.556      394482.388     2316112.306       394922.59
     2316123.164      395776.558     2316825.707      396517.893
      2316519.56       397177.56     2317093.179      399032.076
     2318081.214      399736.178     2318611.871      401994.533
      2319475.52      402979.717     2319600.964      404190.905
     2320410.866      405782.831     2319866.687      406801.772
     2320349.732      407826.948     2320140.276      408498.758
     2320640.202      409072.801     2320847.438      410263.743
     2321734.186      411846.359     2322791.973       412455.41
     2322789.947      412944.273     2322459.845      413210.693
     2322841.888       413780.89     2322729.854      414347.855
     2324394.026      417235.108     2324548.677      419426.537
     2325346.334      419824.098     2325358.019      420408.382
      2323818.96       421677.86     2323959.585      422220.829

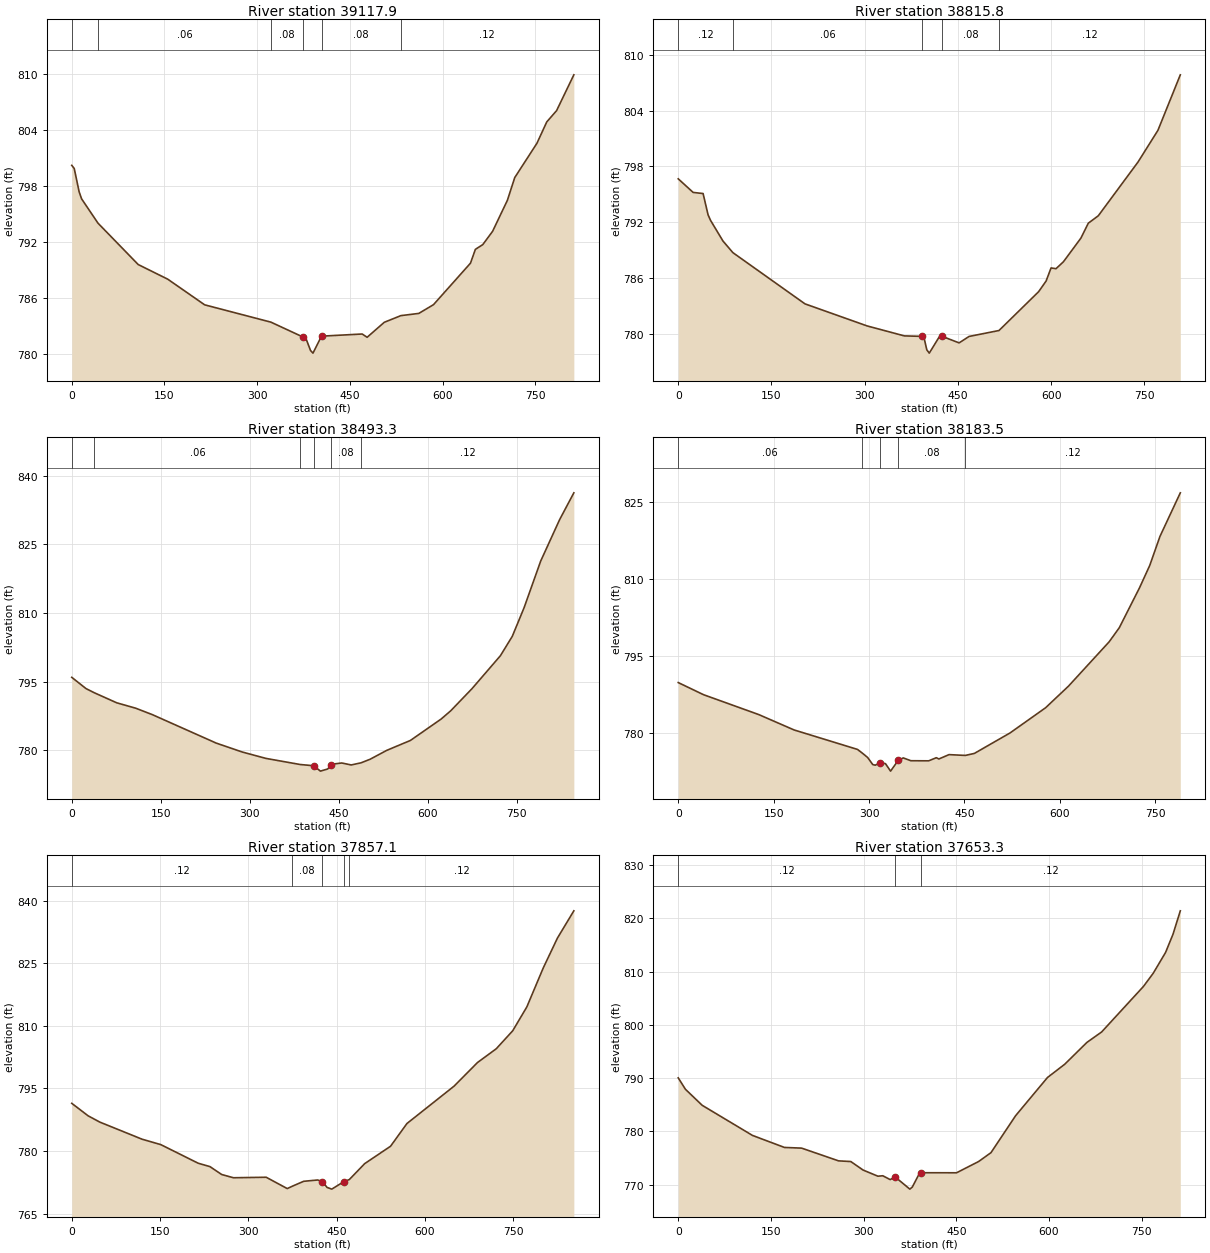
Type RM Length L Ch R = 1 ,39117.9 ,299.1,302.1,297.6
XS GIS Cut Line= 2
     2314377.519      392105.345     2315024.192      391613.959
#Sta/Elev= 30
       0  800.25       4  799.91    11.9  797.42    15.9  796.66   42.38794.0536
   107.5  789.61   155.3  788.04     215  785.29  322.18783.4324     374  781.84
   378.2  781.79   386.2   780.4   390.2  780.11     404  781.93   469.8  782.16
   477.8  781.81   505.6  783.42  532.38 784.132   561.4  784.37   585.2  785.31
     645  789.76   652.9  791.24   664.9  791.75   680.8  793.18   704.7   796.5
   716.6  798.94   752.5  802.62   768.4  804.91   784.3  806.12   812.2  809.96
#Mann= 6 ,-1 , 0
       0     .12       0   42.38     .06       0  322.18     .08       0
     374    .045       0     404     .08       0  532.38     .12       0
Bank Sta=374,404
XS Rating Curve= 0 ,0
Exp/Cntr=0.3,0.1

Type RM Length L Ch R = 1 ,38815.8 ,306,322.5,336.8
XS GIS Cut Line= 2
     2314546.482      392354.452     2315169.813       391840.37
#Sta/Elev= 30
       0  796.67      24  795.21      40  795.09      48  792.81      52  792.21
      72  789.99   87.98788.7412     204  783.24     304  780.87     364   779.8
     392  779.75     396  779.48     400  778.31     404  777.95     420  779.69
     424  779.77     452  779.05     468  779.74  516.21780.3789     580  784.55
     592  785.69     600   787.1     608  787.02     620  787.77     648   790.3
     660  791.91     676   792.7     740  798.48     772  801.88     808  807.84
#Mann= 5 ,-1 , 0
       0     .12       0   87.98     .06       0     392    .045       0
     424     .08       0  516.21     .12       0
Bank Sta=392,424
XS Rating Curve= 0 ,0
Exp/Cntr=0.3,0.1

Type RM Length L Ch R = 1 ,38493.3 ,309.7,309.9,304.4
XS GIS Cut Line= 2
     2314586.643       392420.46     2315415.644       392249.86
#Sta/Elev= 30
       0  795.95      24  793.49    38.3  792.56    75.8  790.38   107.8   789.2
   135.7   787.8   243.5  781.57   287.4  779.62   327.4  778.22  385.06776.8868
   407.7  776.62   419.2  775.44   431.2   775.9   437.7  776.71   439.2  776.96
   455.1  777.22   471.1  776.79  487.55777.2515     503  778.04     531  779.98
   570.9  782.15   622.8  786.84   638.8  788.63   674.7  793.47   722.6  800.68
   742.6  804.91   762.5  811.17   790.5  821.37   822.4  830.43   846.4   836.3
#Mann= 6 ,-1 , 0
       0     .12       0    38.3     .06       0  385.06     .08       0
   407.7    .045       0   437.7     .08       0  487.55     .12       0
Bank Sta=407.7,437.7
XS Rating Curve= 0 ,0
Exp/Cntr=0.3,0.1

Type RM Length L Ch R = 1 ,38183.5 ,318,326.4,322.2
XS GIS Cut Line= 3
     2314678.253      392621.404     2314872.146      392617.308
     2315445.633      392457.551
#Sta/Elev= 30
       0  789.84    39.6  787.48   126.6  783.59   182.1  780.59   281.8  776.79
  288.88776.1188   297.8  775.21   305.8  773.83   309.8  773.71   317.8  774.22
   325.8  774.01   333.8  772.55   345.8  774.64   353.8  775.13   365.7  774.58
   393.7  774.56   405.7  775.17   409.7  774.92   425.7  775.77  451.38775.6156
   465.6  776.01   521.6     780   577.5  784.92   613.5  789.14   677.4  797.79
   693.4  800.55   725.3  808.37   741.3  812.72   757.3  818.37   789.3  826.88
#Mann= 5 ,-1 , 0
       0     .06       0  288.88     .12       0   317.8    .045       0
   345.8     .08       0  451.38     .12       0
Bank Sta=317.8,345.8
XS Rating Curve= 0 ,0
Exp/Cntr=0.3,0.1

Type RM Length L Ch R = 1 ,37857.1 ,208.6,203.7,198.4
XS GIS Cut Line= 3
     2314741.894      392909.243     2315164.729      392813.043
     2315571.002       392710.26
#Sta/Elev= 30
       0  791.44    27.8  788.44    47.7  786.93   119.4  782.83   151.2  781.53
   214.8  777.06   234.7  776.25   254.6  774.36   274.5  773.58   330.2   773.7
     366  770.98   374.2771.5246   393.9  772.73   417.7  773.04   425.7  772.66
   433.6  771.26   441.6  770.85   461.6  772.61  471.43 773.151   497.5  776.97
   541.4  781.14   569.3   786.6   649.2  795.55   689.1  801.23     721  804.54
   748.9  808.85   772.9  814.58   800.8  823.94   824.8  831.08   852.7  837.63
#Mann= 5 ,-1 , 0
       0     .12       0   374.2     .08       0   425.7    .045       0
   461.6     .08       0  471.43     .12       0
Bank Sta=425.7,461.6
XS Rating Curve= 0 ,0
Exp/Cntr=0.3,0.1

Type RM Length L Ch R = 1 ,37653.3 ,326.3,328.2,329.1
XS GIS Cut Line= 3
     2314825.721      393108.868     2314937.687      393115.695
     2315580.812       392838.51
#Sta/Elev= 30
       0  790.07    11.6  787.93    38.7  784.92   120.1  779.26   171.9     777
   199.7  776.87   259.4  774.48   279.3  774.35   299.2  772.75   323.1   771.6
     331  771.68     343  770.96   350.9  771.47   374.8  769.17   378.8  769.56
   390.7  772.21   393.4  772.25   450.4  772.24   486.2  774.36   506.1  776.02
   545.9  782.95   597.6  790.14   625.5  792.63   661.3  796.72   685.2  798.69
   752.8  807.23   768.7  809.72   788.6  813.61   800.6  817.02   812.5  821.44
#Mann= 3 ,-1 , 0
       0     .12       0   350.9    .045       0   393.4     .12       0
Bank Sta=350.9,393.4
XS Rating Curve= 0 ,0
Exp/Cntr=0.3,0.1

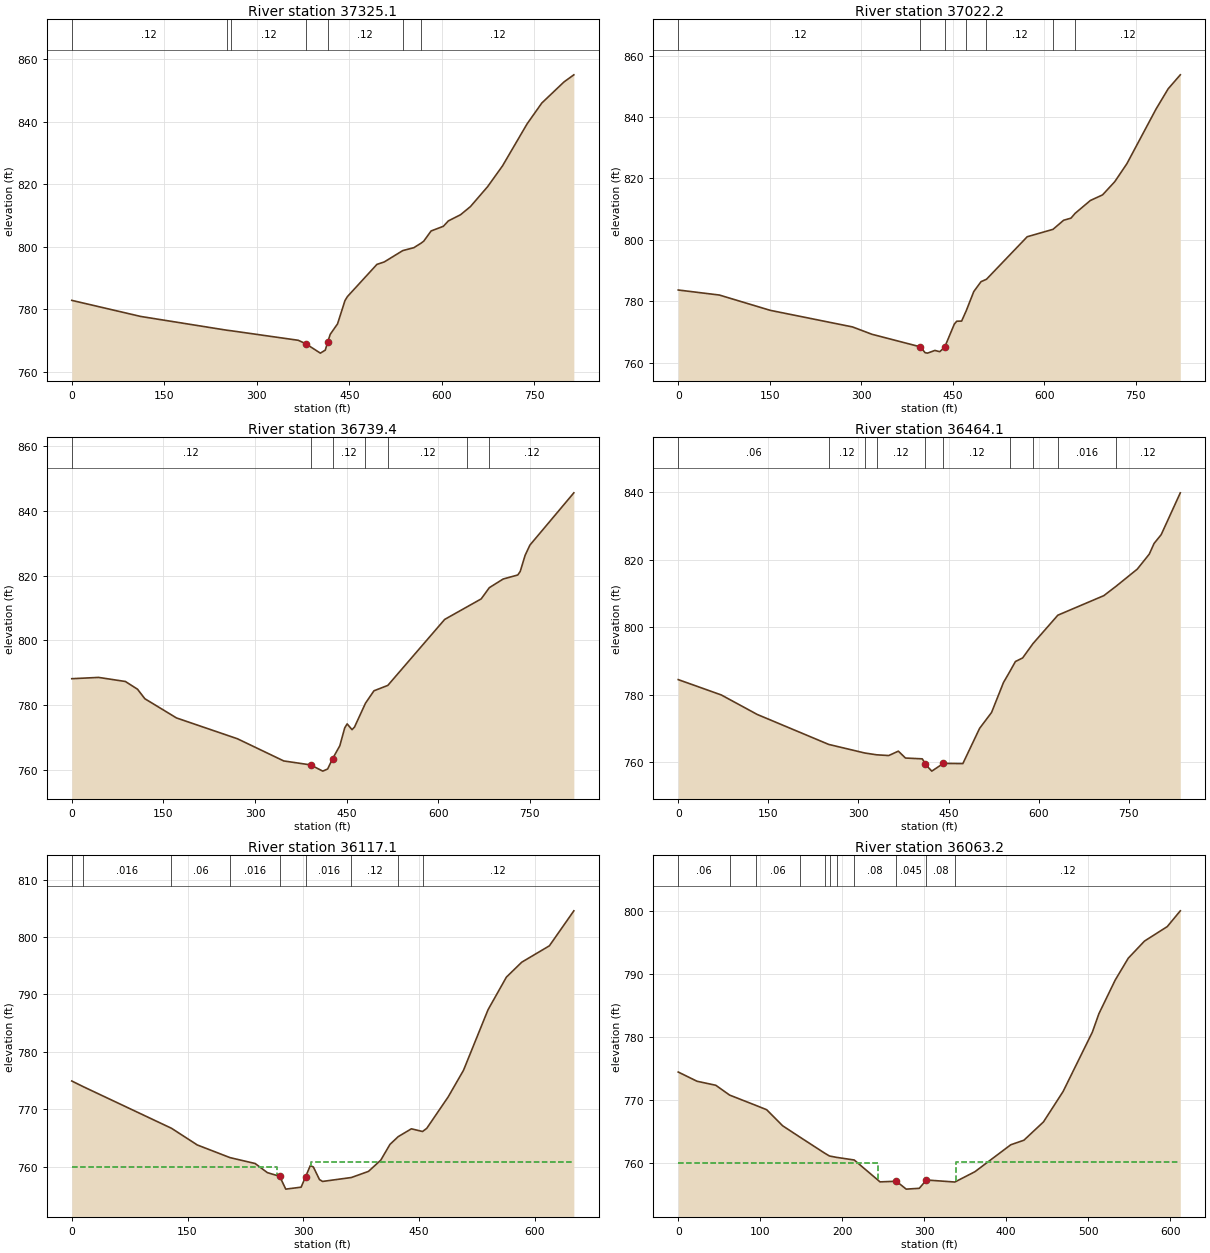
Type RM Length L Ch R = 1 ,37325.1 ,296.4,302.9,306.9
XS GIS Cut Line= 2
     2315011.421      393401.073      2315773.49      393115.032
#Sta/Elev= 30
       0  782.83   111.7  777.69  251.15773.2919  258.55773.1091   367.1  770.07
   379.1     769     403  765.96     411  766.92     415  769.53     419  771.96
   430.9  775.32   442.9  782.74   446.9  784.04   494.8  794.34   506.7  795.12
  536.68798.7485   554.6  799.67  566.08801.0833   570.6  801.75   582.6  805.02
   602.5  806.52   610.5  808.23   630.4  810.22   646.4  812.82   674.3  819.21
   698.3  825.81   738.2  839.26   762.1  845.93     798  852.66     814  854.94
#Mann= 7 ,-1 , 0
       0     .12       0  251.15     .06       0  258.55     .12       0
   379.1    .045       0     415     .12       0  536.68    .016       0
  566.08     .12       0
Bank Sta=379.1,415
XS Rating Curve= 0 ,0
Exp/Cntr=0.3,0.1

Type RM Length L Ch R = 1 ,37022.2 ,286.8,282.9,278.8
XS GIS Cut Line= 3
     2315063.319      393612.878     2315466.479      393546.316
     2315872.527      393464.617
#Sta/Elev= 30
       0  783.68    67.4  782.04   150.8  777.06   285.6  771.66   317.4  769.27
   396.7  765.18   404.6  763.26   408.6  763.13   420.6  764.01   428.5   763.6
   436.5     765   452.4  772.56   456.4  773.52   464.4  773.56  471.93776.8932
   484.3  783.16   496.2  786.39  505.14 787.174   571.9  801.02  614.14803.4236
   631.6  806.39   643.6  807.07  650.58808.6666   675.4  812.82   695.4  814.65
   715.3  818.92   735.2  824.78     783  842.58   802.9  849.18   822.8  853.73
#Mann= 7 ,-1 , 0
       0     .12       0   396.7    .045       0   436.5     .12       0
  471.93    .016       0  505.14     .12       0  614.14    .016       0
  650.58     .12       0
Bank Sta=396.7,436.5
XS Rating Curve= 0 ,0
Exp/Cntr=0.3,0.1

Type RM Length L Ch R = 1 ,36739.4 ,276.5,275.2,271
XS GIS Cut Line= 3
     2315113.189      393906.417     2315373.264      393865.325
     2315905.788      393696.009
#Sta/Elev= 30
       0   788.1    43.9   788.5    87.8  787.24   107.7  784.84   119.7   781.9
   171.5  775.96   271.3  769.52   347.1  762.66     391  761.44     411  759.51
     419  760.18     427  763.33   438.9  767.36   446.9  772.87   450.9  774.12
   458.9  772.34   462.9  773.12  480.93780.5202   494.8  784.36  517.51786.0284
   610.6  806.44  647.42810.3482   670.4  812.79  683.73816.2661   706.3  818.93
   730.3  820.19   734.3  821.28   742.3  826.26   750.2  829.44   822.1   845.6
#Mann= 7 ,-1 , 0
       0     .12       0     391    .045       0     427     .12       0
  480.93    .016       0  517.51     .12       0  647.42    .016       0
  683.73     .12       0
Bank Sta=391,427
XS Rating Curve= 0 ,0
Exp/Cntr=0.3,0.1

Type RM Length L Ch R = 1 ,36464.1 ,339.8,347.1,352.7
XS GIS Cut Line= 3
     2315212.764      394236.903     2315603.906      394058.095
      2315974.25      393892.349
#Sta/Elev= 30
       0  784.47    71.7  779.92   131.4  774.15  250.52765.2581  310.57762.7108
  330.13762.1802   350.4  761.96   366.4  763.26   378.3  761.22   406.2  760.98
   410.2  759.87   411.4  759.35   422.1  757.34   441.4  759.63   473.8  759.57
   501.7  770.02   521.6  774.73   541.4   783.6  551.82786.8024   561.3  789.83
   573.3  790.89  590.44795.1211  631.94803.5667   708.5  809.36  729.33812.2076
   764.2  817.23   784.1  821.66   792.1  824.82     804  827.45   835.8  839.84
#Mann= 10 ,-1 , 0
       0     .06       0  250.52     .12       0  310.57     .06       0
  330.13     .12       0   410.2    .045       0   441.4     .12       0
  551.82    .016       0  590.44     .12       0  631.94    .016       0
  729.33     .12       0
Bank Sta=411.4,441.4
XS Rating Curve= 0 ,0
Exp/Cntr=0.3,0.1

Type RM Length L Ch R = 1 ,36117.1 ,61.1,53.8,52.6
XS GIS Cut Line= 5
     2315494.789       394556.24     2315509.809      394487.968
     2315579.227      394405.043      2315866.19      394341.865
     2316035.505      394284.516
#Sta/Elev= 30
       0  774.94   14.95773.9494  129.23  766.71   162.6  763.81  205.08761.6035
   237.6  760.58   253.5  758.99   269.4  758.35   277.3  756.12   297.2  756.46
     303  758.28   309.1  760.22   313.1  759.97     321  757.78     325  757.46
  362.37758.1435   384.5  759.21   400.4  761.16   412.3   763.9  422.99765.2552
   440.1  766.62  454.52766.1489     460   766.7   487.8  772.18   507.6   776.8
   539.4  787.34   563.2  793.02   583.1  795.62   618.9  798.47   650.6  804.56
#Mann= 9 ,-1 , 0
       0     .06       0   14.95    .016       0  129.23     .06       0
  205.08    .016       0   269.4    .045       0     303    .016       0
  362.37     .12       0  422.99    .016       0  454.52     .12       0
#XS Ineff= 2 , 0
          265.84  760.03  309.91          760.84
Permanent Ineff=
       F       F
Bank Sta=269.4,303
XS Rating Curve= 0 ,0
Exp/Cntr=0.3,0.1

Type RM Length L Ch R = 1 ,36063.2 ,434,496.1,454.6
XS GIS Cut Line= 5
     2315523.463      394595.838     2315531.656      394550.778
     2315589.005      394453.831     2315877.114      394389.656
     2316027.313      394337.769
#Sta/Elev= 30
       0  774.44    22.9  772.98    45.8  772.34   62.72770.7808   94.59769.1539
   107.9  768.46   127.4  765.91  148.28764.1285  178.69761.5654  184.59761.1131
  193.22760.8994  214.72760.4812   246.2  757.01   266.1  757.11   278.1  755.86
   294.1  755.99   302.7  757.31  337.46756.9867   361.9  758.62   405.7   762.9
   421.7  763.62   445.6  766.53   469.5  771.35   505.2  780.77   513.2   783.7
   533.1  789.04     549   792.5   568.8  795.22   596.6  797.52   612.5  800.02
#Mann= 11 ,-1 , 0
       0     .06       0   62.72     .08       0   94.59     .06       0
  148.28    .016       0  178.69     .06       0  184.59     .12       0
  193.22    .016       0  214.72     .08       0   266.1    .045       0
   302.7     .08       0  337.46     .12       0
#XS Ineff= 2 , 0
          244.17  759.93   338.8          760.14
Permanent Ineff=
       F       F
Bank Sta=266.1,302.7
XS Rating Curve= 0 ,0
Exp/Cntr=0.3,0.1

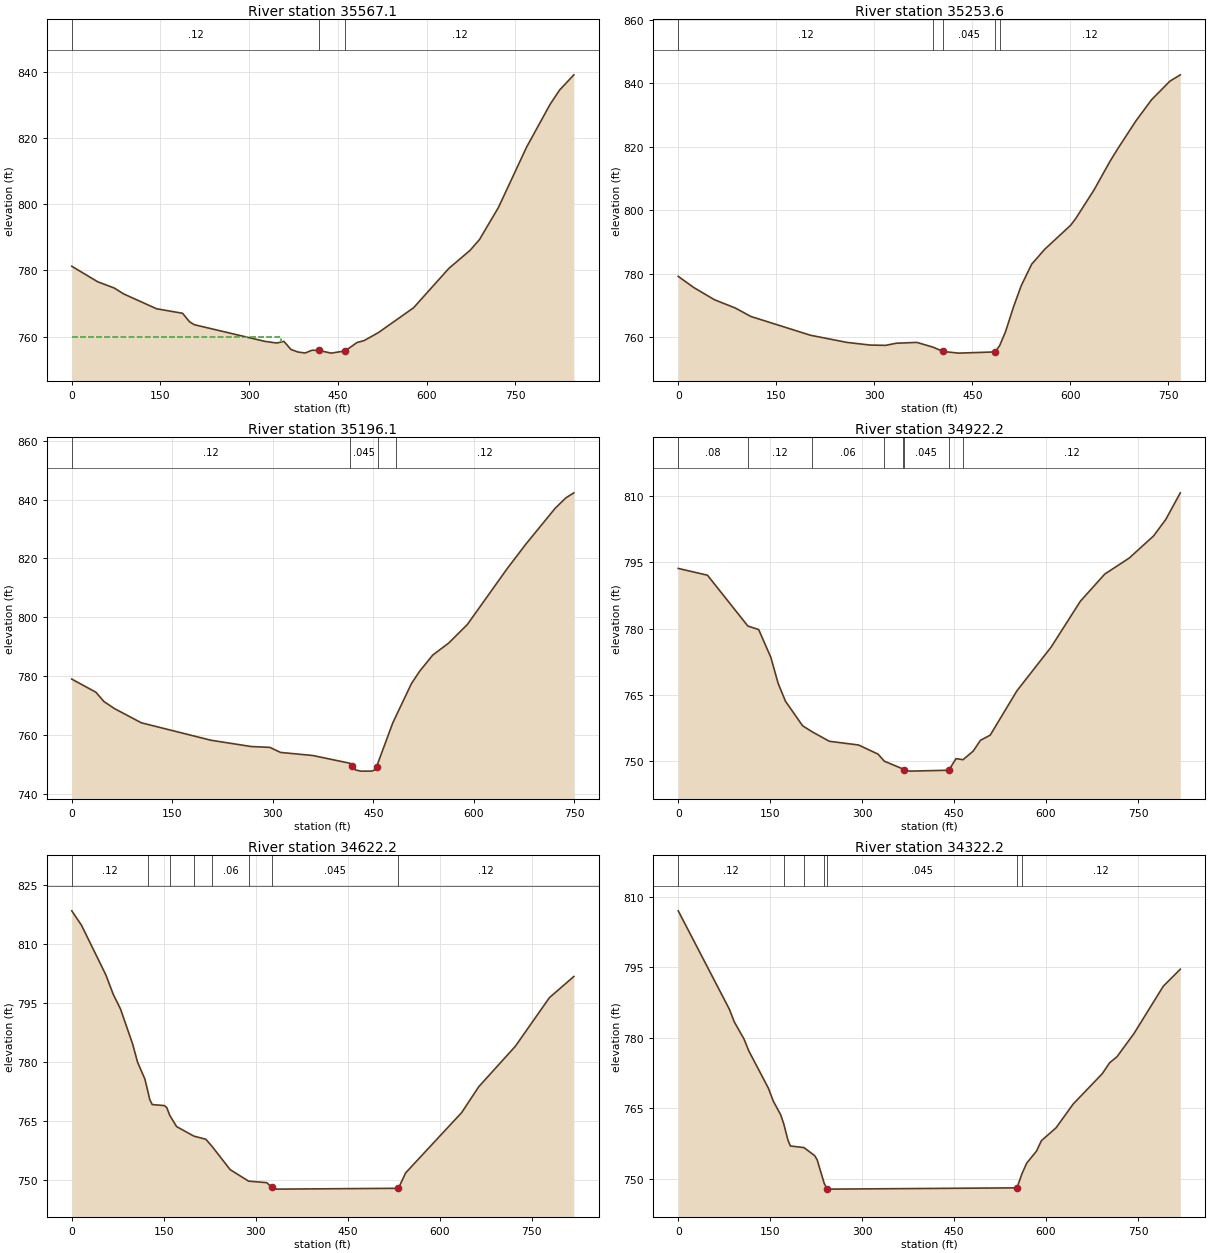
Type RM Length L Ch R = 1 ,35567.1 ,300.2,313.5,327.2
XS GIS Cut Line= 2
     2315595.508      394977.232     2316214.679      394396.117
#Sta/Elev= 30
       0  781.24    43.8  776.56    71.8  774.67    87.7  772.89   143.5   768.4
   187.4  767.04   199.3  764.46   207.3  763.59   326.9  758.55   346.8  758.06
   358.8  758.56   370.8  756.11   382.7  755.34   394.7  755.05   406.6  755.89
   418.6  755.81   438.5  755.01   462.4  755.67   482.4  758.21   494.3  758.78
   518.3  761.17   578.1   768.7   637.9  780.61   673.7  786.04   689.7  789.33
   721.6  798.96   769.4  817.25   809.3   830.2   825.2  834.46   849.2  839.03
#Mann= 3 ,-1 , 0
       0     .12       0   418.6    .045       0   462.4     .12       0
#XS Ineff= 2 , 0
           354.3  760.03
Permanent Ineff=
       F       F
Bank Sta=418.6,462.4
XS Rating Curve= 0 ,0
Exp/Cntr=0.3,0.1

Type RM Length L Ch R = 1 ,35253.6 ,56.2,57.5,57.8
XS GIS Cut Line= 3
     2315653.822      395007.347     2316009.291      394943.545
      2316402.52      394838.076
#Sta/Elev= 30
       0  779.18    23.8  775.66    55.6   771.8    87.3  769.22   111.1  766.55
   202.4  760.63     258  758.38   293.7  757.54   317.5  757.45   333.4  758.11
   365.1  758.38  389.87756.8834   405.1  755.53     429     755   484.9  755.38
  491.82757.3493   500.8  761.72   512.8  769.41   524.8  776.21   540.8     783
   560.7  787.69   600.6   795.3   608.6   797.5   636.6  806.51   660.5  815.35
   672.5  819.35   700.4  828.16   724.4  834.84   752.3  840.65   768.3  842.66
#Mann= 5 ,-1 , 0
       0     .12       0  389.87     .04       0   405.1    .045       0
   484.9     .04       0  491.82     .12       0
Bank Sta=405.1,484.9
XS Rating Curve= 0 ,0
Exp/Cntr=0.3,0.1

Type RM Length L Ch R = 1 ,35196.1 ,261.7,273.9,286.8
XS GIS Cut Line= 3
      2315683.77       395034.69     2316095.228      394977.399
     2316418.145      394892.763
#Sta/Elev= 30
       0  779.01      36  774.56    47.9  771.41    63.9  768.97   103.9  764.16
   207.7  758.24   267.6  756.11   295.6  755.82   311.6   754.1   359.5  753.06
   415.4  750.41   418.6  749.51   423.4  748.15   431.3  747.75   447.2  747.75
   451.2  748.05   455.2  749.32  456.84   750.5     479  764.12  484.19766.6396
   506.8  777.46   518.8  781.59   538.6  787.16   562.5  791.26   590.3  797.56
   649.9  816.59   677.7  824.89   721.4  837.06   737.3  840.58   749.2  842.29
#Mann= 4 ,-1 , 0
       0     .12       0   415.4    .045       0  456.84     .04       0
  484.19     .12       0
Bank Sta=418.6,455.2
XS Rating Curve= 0 ,0
Exp/Cntr=0.3,0.1

Type RM Length L Ch R = 1 ,34922.2 ,309.4,300,290.1
XS GIS Cut Line= 3
     2315650.406      395171.061      2316054.08      395239.872
     2316457.197      395311.988
#Sta/Elev= 30
       0  793.59    47.7  792.06  113.62780.5568   131.2  779.77   151.1  773.47
     163  767.59   174.9  763.57   202.8  758.02  218.56756.6357   246.5   754.5
   294.2  753.66     326  751.59  336.16749.9948   366.2748.2618  367.89  748.09
   377.7  747.75   441.3  747.95   453.2  750.58  464.55 750.334   481.1  752.27
     493  754.72   508.9  755.89   552.6  765.94   608.3  775.81     656  786.18
   695.8  792.32   735.5  795.92   775.3  800.93   795.2  804.65     819  810.69
#Mann= 8 ,-1 , 0
       0     .08       0  113.62     .12       0  218.56     .06       0
  336.16     .08       0   366.2     .04       0  367.89    .045       0
   441.3     .04       0  464.55     .12       0
Bank Sta=367.89,441.3
XS Rating Curve= 0 ,0
Exp/Cntr=0.3,0.1

Type RM Length L Ch R = 1 ,34622.2 ,310,300,290.1
XS GIS Cut Line= 3
     2315642.907      395598.351     2316047.994      395538.392
     2316452.946      395477.523
#Sta/Elev= 30
       0  818.46    15.9  814.79    55.7  802.15    67.6  797.27    79.5  793.52
    99.4  784.57   107.3  780.02   119.3  775.71   124.2 772.555   127.2   770.5
   131.2  769.24   151.1  768.97     155  768.47  159.81766.5062     171  763.64
  199.12761.2204   218.7  760.42  228.89758.6003   258.4   752.7  288.43749.7819
   318.1  749.39     326  748.24     334  747.75   532.8  747.96   544.7  751.89
   636.1  767.22     664  773.79   723.6  784.05   779.2  796.41     819  801.78
#Mann= 8 ,-1 , 0
       0     .12       0   124.2    .016       0  159.81     .12       0
  199.12     .08       0  228.89     .06       0  288.43     .04       0
     326    .045       0   532.8     .12       0
Bank Sta=326,532.8
XS Rating Curve= 0 ,0
Exp/Cntr=0.3,0.1

Type RM Length L Ch R = 1 ,34322.2 ,330.6,331.8,332.7
XS GIS Cut Line= 3
      2315782.17      396011.249     2316144.796       395821.01
     2316508.765      395633.322
#Sta/Elev= 30
       0  807.02    83.5  786.04    91.4  783.38   107.3  779.72   115.3  777.14
   147.1  769.24     155  766.51     167  763.61     172761.7164   178.9  758.23
   182.9  756.94  205.05   756.6   222.6  754.88   226.6     754   238.1748.9895
   242.5  747.84   246.5  747.75   552.6  748.02   560.7751.0292   568.5   753.3
   584.4  755.84   592.4  758.07   616.2  760.79   644.1  765.85   691.8  772.35
   703.7  774.66   715.6  775.93   743.5   780.9   791.2  790.96     819  794.59
#Mann= 7 ,-1 , 0
       0     .12       0     172    .016       0  205.05     .12       0
   238.1     .04       0   242.5    .045       0   552.6     .04       0
   560.7     .12       0
Bank Sta=242.5,552.6
XS Rating Curve= 0 ,0
Exp/Cntr=0.3,0.1

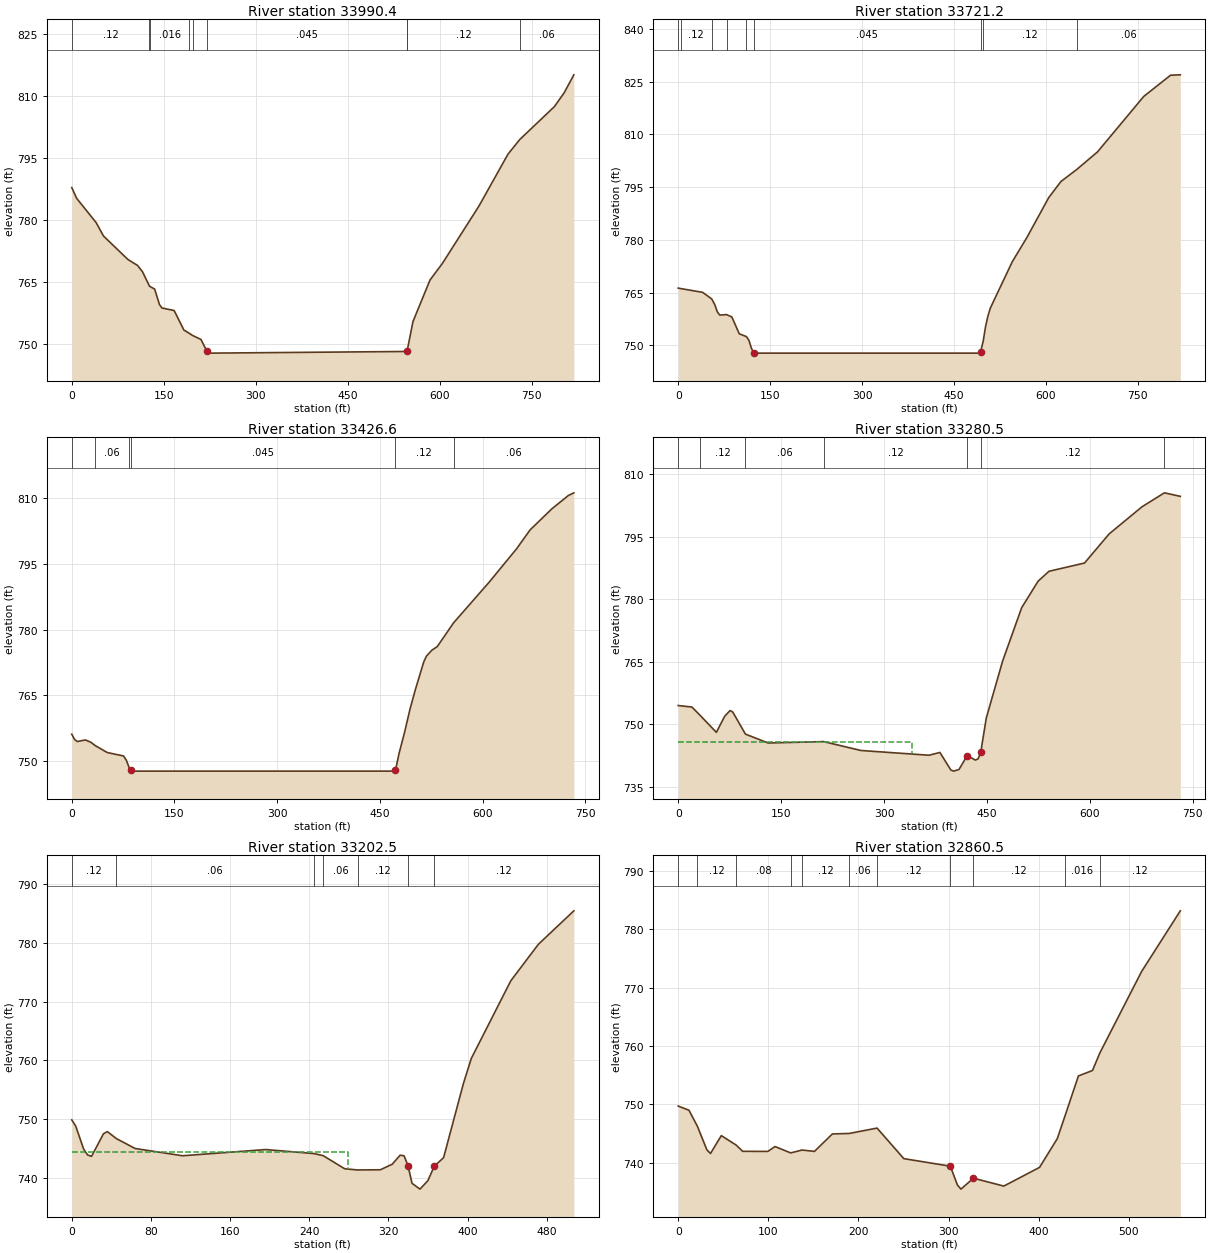
Type RM Length L Ch R = 1 ,33990.4 ,268.6,269.2,268.5
XS GIS Cut Line= 3
     2315973.006       396265.91     2316340.792      396085.843
     2316708.577      395905.776
#Sta/Elev= 30
       0  787.84       8  785.23    39.8  779.35    51.7  776.12    91.4  770.45
   107.3  768.98   115.3  767.48  126.52764.0498  127.02763.9323   135.2  763.26
   143.1   759.5   147.1  758.68     167  758.07   182.9  753.34  191.85752.5329
  197.07752.0217   210.7  751.07  220.71  748.15   226.6  747.75  547.11  748.15
  547.59748.6693   556.6   755.4   584.4  765.46   604.3  769.41     664  783.31
   711.7  795.96  730.99799.5058   787.2  807.43   803.1  810.76     819  815.14
#Mann= 9 ,-1 , 0
       0     .12       0  126.52     .06       0  127.02    .016       0
  191.85     .12       0  197.07     .04       0  220.71    .045       0
  547.11     .04       0  547.59     .12       0  730.99     .06       0
Bank Sta=220.71,547.11
XS Rating Curve= 0 ,0
Exp/Cntr=0.3,0.1

Type RM Length L Ch R = 1 ,33721.2 ,293.9,294.6,296
XS GIS Cut Line= 3
     2316166.203      396444.307     2316537.303      396269.619
     2316895.742      396071.804
#Sta/Elev= 30
       0  766.26    4.45766.1096    39.8  765.05   54.67763.1745    59.7  761.55
    63.7  759.55    67.7  758.58   79.02758.7145    87.6  758.03    99.6  753.25
   111.4 752.448   115.5  751.36   119.5  749.12   123.4  747.84   127.4  747.75
   489.7  747.75   493.6  748.13  497.81751.1268   501.6  755.22   505.6  758.35
   509.5  760.58   545.3  773.76   569.2  780.67   604.9  792.04   624.8  796.61
  650.91800.0718   684.4  805.02   759.9  820.81   803.7  826.85   819.6  826.96
#Mann= 9 ,-1 , 0
       0     .06       0    4.45     .12       0   54.67    .016       0
   79.02     .12       0   111.4     .04       0   123.4    .045       0
   493.6     .04       0  497.81     .12       0  650.91     .06       0
Bank Sta=123.4,493.6
XS Rating Curve= 0 ,0
Exp/Cntr=0.3,0.1

Type RM Length L Ch R = 1 ,33426.6 ,148.2,146.1,145.5
XS GIS Cut Line= 3
     2316350.986       396638.25     2316856.687      396412.425
     2316984.291      396286.123
#Sta/Elev= 30
       0  756.17       4  754.99       8  754.49    19.9  754.85    27.9  754.33
   33.89753.6014    51.8  751.99    75.7   751.2    79.7  750.23    84.1 748.433
   87.04  747.93    91.6  747.75   466.2  747.75  471.83  747.98   474.1  748.84
   478.1  751.79   486.1  756.56   494.1  761.89     502  766.37     514  772.56
     518  773.93   525.9  775.28   533.9  776.12   557.8  781.54   609.7  790.79
   649.6  798.36   669.5   802.7   701.4  807.51   725.4  810.53   733.4  811.14
#Mann= 6 ,-1 , 0
       0    .016       0   33.89     .06       0    84.1     .04       0
   87.04    .045       0  471.83     .12       0   557.8     .06       0
Bank Sta=87.04,471.83
XS Rating Curve= 0 ,0
Exp/Cntr=0.3,0.1

Type RM Length L Ch R = 1 ,33280.5 ,77.9,78,74.7
XS GIS Cut Line= 3
     2316430.847      396753.701     2316935.246      396528.744
      2317062.85      396402.442
#Sta/Elev= 30
       0  754.49    19.9  754.13   31.85752.1412    55.6  748.06    67.6  751.89
    75.5  753.29    79.5  752.93   97.95747.6381   131.1   745.5  211.95 745.838
   266.2  743.71   365.5  742.57   381.4  743.24   397.3  739.04   401.3  738.76
   409.2  739.15   421.2  742.48   433.1  741.41   437.1   741.7     441  743.36
     449   751.5   472.8  765.15   500.6  777.96   524.5   784.3   540.4  786.68
   592.2  788.66   628.1  795.65     676  802.15  708.61805.4938   731.8  804.65
#Mann= 7 ,-1 , 0
       0    .016       0   31.85     .12       0   97.95     .06       0
  211.95     .12       0   421.2    .045       0     441     .12       0
  708.61    .016       0
#XS Ineff= 2 , 0
          340.95  745.82
Permanent Ineff=
       F       F
Bank Sta=421.2,441
XS Rating Curve= 0 ,0
Exp/Cntr=0.3,0.1

Type RM Length L Ch R = 1 ,33202.5 ,298.1,342,382.6
XS GIS Cut Line= 3
     2316506.426      396818.675     2316861.147      396625.892
     2316915.373      396537.607
#Sta/Elev= 30
       0  749.84       4  748.78      12  744.86      16  743.85      20  743.62
      32  747.47      36  747.84   44.99746.6542      64  744.96   111.9  743.72
   195.9  744.78  244.53744.0954     254743.7405   275.8   741.5  288.85741.2989
   311.8  741.33   323.8  742.28   331.8  743.82   335.8  743.71   339.8  741.98
   343.8  739.02   351.8  738.03   359.8  739.47   366.3  741.94   375.7   743.4
   395.7  756.03   403.7  760.32   443.6  773.56   471.5  779.79   507.3  785.49
#Mann= 7 ,-1 , 0
       0     .12       0   44.99     .06       0  244.53     .12       0
     254     .06       0  288.85     .12       0   339.8    .045       0
   366.3     .12       0
#XS Ineff= 2 , 0
          279.59  744.39
Permanent Ineff=
       F       F
Bank Sta=339.8,366.3
XS Rating Curve= 0 ,0
Exp/Cntr=0.3,0.1

Type RM Length L Ch R = 1 ,32860.5 ,140,141.2,140.2
XS GIS Cut Line= 4
     2316507.728      396861.644     2316680.905      396816.071
     2316824.134      397000.967     2316958.249      397054.352
#Sta/Elev= 30
       0  749.73    11.9  749.02   21.18746.3028    31.8  742.24    35.8  741.61
    47.8  744.67   64.07743.0764    71.6  741.98    99.5  741.97   107.4   742.8
  124.86741.7126  137.46   742.2   151.2  741.97   171.1  744.96  189.73745.0405
  220.69745.9601   250.4  740.73     302  739.44   309.9  736.22   313.8  735.51
   327.7  737.38   361.4  736.03   401.1  739.24   420.8  744.17  428.98747.8939
   444.2  754.89   459.8  755.82  468.02758.8331   514.4  772.79   557.3  783.16
#Mann= 11 ,-1 , 0
       0    .016       0   21.18     .12       0   64.07     .08       0
  124.86     .06       0  137.46     .12       0  189.73     .06       0
  220.69     .12       0     302    .045       0   327.7     .12       0
  428.98    .016       0  468.02     .12       0
Bank Sta=302,327.7
XS Rating Curve= 0 ,0
Exp/Cntr=0.3,0.1

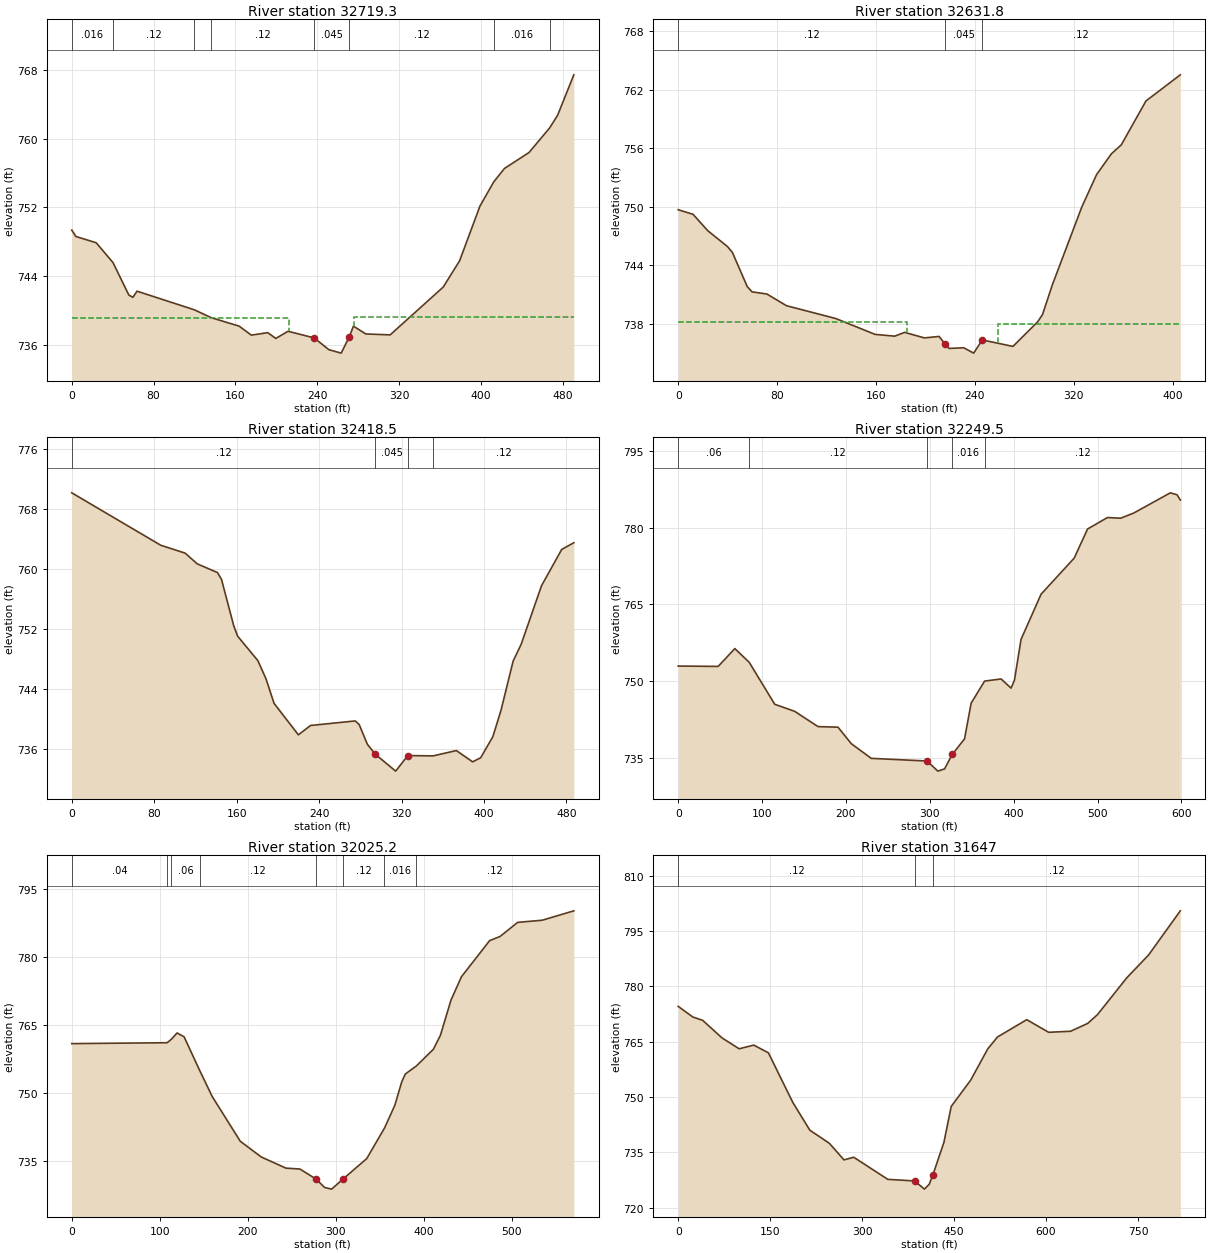
Type RM Length L Ch R = 1 ,32719.3 ,87.2,87.5,87.9
XS GIS Cut Line= 3
      2316502.52      396878.571     2316566.322      396879.873
     2316826.739      397218.414
#Sta/Elev= 30
       0  749.36       4  748.62    23.9  747.89   40.29745.5896    55.8  741.81
    59.8  741.55    63.8  742.26  119.92740.0941  136.46739.1749   163.6   738.2
   175.6  737.15   191.6  737.44   199.5  736.77   211.5   737.6     237  736.83
   251.4  735.46   263.4  735.06   271.4  736.96   275.4   738.2   287.4  737.29
   311.3  737.18   363.2  742.74   379.2  745.79   399.1  752.15  412.59754.9676
   423.1  756.53     447  758.37  467.28761.2434     475   762.7   490.9  767.41
#Mann= 8 ,-1 , 0
       0    .016       0   40.29     .12       0  119.92     .06       0
  136.46     .12       0     237    .045       0   271.4     .12       0
  412.59    .016       0  467.28     .12       0
#XS Ineff= 2 , 0
          212.07   739.2  276.06          739.26
Permanent Ineff=
       F       F
Bank Sta=237,271.4
XS Rating Curve= 0 ,0
Exp/Cntr=0.3,0.1

Type RM Length L Ch R = 1 ,32631.8 ,238.5,213.3,183.5
XS GIS Cut Line= 2
     2316480.384      396905.914     2316725.176      397230.133
#Sta/Elev= 30
       0  749.71      12  749.24    23.9  747.56    39.8  745.94    43.8  745.34
    55.8  741.84    59.7  741.29    71.7  741.07    87.6  739.87   127.4  738.56
   159.3  736.93   175.2  736.75   183.2  737.14   199.1  736.57   211.1  736.72
     216  735.92   219.1  735.49     231  735.56     239  735.01     246  736.36
   270.8   735.7   290.8  738.22   294.7  738.96   302.7  742.02   326.6  750.02
   338.5  753.32   350.5  755.45   358.5  756.37   378.4  760.86   406.2  763.54
#Mann= 3 ,-1 , 0
       0     .12       0     216    .045       0     246     .12       0
#XS Ineff= 2 , 0
          184.73  738.19  259.03          738.04
Permanent Ineff=
       F       F
Bank Sta=216,246
XS Rating Curve= 0 ,0
Exp/Cntr=0.3,0.1

Type RM Length L Ch R = 1 ,32418.5 ,177.8,168.9,159.6
XS GIS Cut Line= 4
     2316263.197      397174.751     2316442.646      397263.643
     2316507.989      397236.383     2316724.134      397232.911
#Sta/Elev= 30
       0  770.18    86.4  763.17     110  762.12   121.7  760.69   141.4  759.52
   145.3  758.61   157.1  752.44     161  751.01   180.6  747.75   188.5  745.31
   196.3  742.04   219.9  737.83   231.7  739.08     275  739.69   278.9  739.21
   286.8  736.58   294.6  735.23   314.3  732.98   326.1  735.06  350.61735.0173
   373.2  735.73     389  734.22   396.8  734.77   408.6  737.58   416.5   741.1
   428.3  747.69   436.1  749.94   455.8  757.75   475.4  762.61   487.2  763.51
#Mann= 4 ,-1 , 0
       0     .12       0   294.6    .045       0   326.1    .016       0
  350.61     .12       0
Bank Sta=294.6,326.1
XS Rating Curve= 0 ,0
Exp/Cntr=0.3,0.1

Type RM Length L Ch R = 1 ,32249.5 ,228,224.4,218.4
XS GIS Cut Line= 3
     2316308.336      397482.911     2316733.801      397340.907
     2316880.384      397373.536
#Sta/Elev= 30
       0  752.92    47.6  752.85    67.5  756.34    84.6753.6661   115.1  745.43
   138.9  744.05   166.7  741.06   190.5  740.95   206.4  737.71   230.2  734.84
   296.7  734.32   309.6  732.34   317.6  732.78   326.7   735.6   341.4  738.66
   349.3  745.66  365.34749.9766     385  750.39   396.9   748.6   400.9  750.14
   408.8  758.15   432.7     767   472.2  774.07   488.1  779.76   511.8  782.01
   527.6  781.88   543.4  782.91   586.8  786.85   594.8  786.47   598.7  785.44
#Mann= 5 ,-1 , 0
       0     .06       0    84.6     .12       0   296.7    .045       0
   326.7    .016       0  365.34     .12       0
Bank Sta=296.7,326.7
XS Rating Curve= 0 ,0
Exp/Cntr=0.3,0.1

Type RM Length L Ch R = 1 ,32025.2 ,373.3,378.2,381.5
XS GIS Cut Line= 2
     2316394.707      397729.656     2316899.916      397464.031
#Sta/Elev= 30
       0  760.84  108.48761.0401  113.31 761.816   119.7  763.19   127.7  762.35
  145.45754.9113   159.7  749.17   191.6  739.31   215.5  735.84   243.5  733.39
   259.4  733.19   277.8  730.97   287.4  729.13   295.4  728.76   307.8  730.89
   335.3  735.48  355.48742.2057   367.2   747.2   375.2  752.44   379.2  754.14
  391.64 755.894   411.1  759.59   419.1  762.67   431.1  770.42     443  775.58
     475  783.54     487  784.48   506.9  787.57   534.9  788.05   570.8  790.12
#Mann= 8 ,-1 , 0
       0     .04       0  108.48     .08       0  113.31     .06       0
  145.45     .12       0   277.8    .045       0   307.8     .12       0
  355.48    .016       0  391.64     .12       0
Bank Sta=277.8,307.8
XS Rating Curve= 0 ,0
Exp/Cntr=0.3,0.1

Type RM Length L Ch R = 1 ,31647   ,339.1,344.1,347.3
XS GIS Cut Line= 3
     2316458.178      398061.633      2316840.85       397915.85
     2317223.521      397770.066
#Sta/Elev= 30
       0  774.59    23.8   771.7    39.8  770.81    71.6  766.01    99.4  763.08
   123.2  764.08   147.1  761.98   186.9  748.52   214.7  740.98   246.5  737.43
   270.4  732.92   286.2  733.65   341.9  727.64   385.5  727.22   401.6  724.99
   409.5  726.33   415.5  728.91   433.4  737.69   445.3  747.42   477.1  754.58
   504.9  763.05   520.8  766.28   568.5  770.98   604.3  767.55   640.1  767.84
   667.9  769.96   683.8  772.33   731.5   782.3   767.3  788.55     819  800.52
#Mann= 3 ,-1 , 0
       0     .12       0   385.5    .045       0   415.5     .12       0
Bank Sta=385.5,415.5
XS Rating Curve= 0 ,0
Exp/Cntr=0.3,0.1