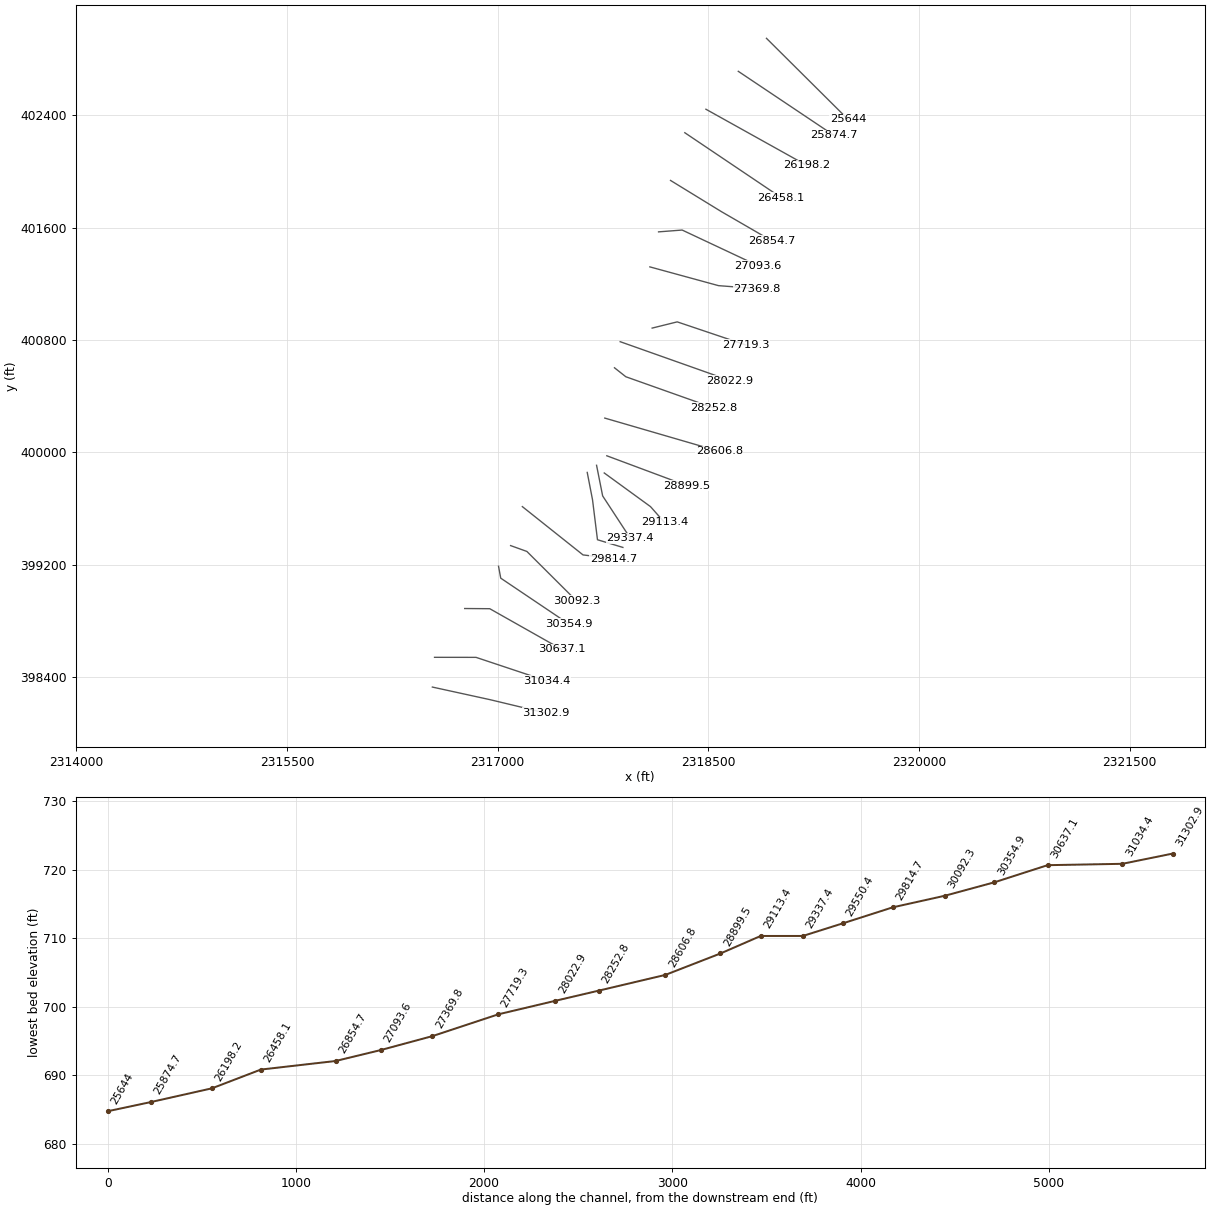
HEC-RAS study SIRJOHNSRN.prj: SIRJOHNSRN

--- SIRJOHNSRN.g01 (geometry) --- (continued)

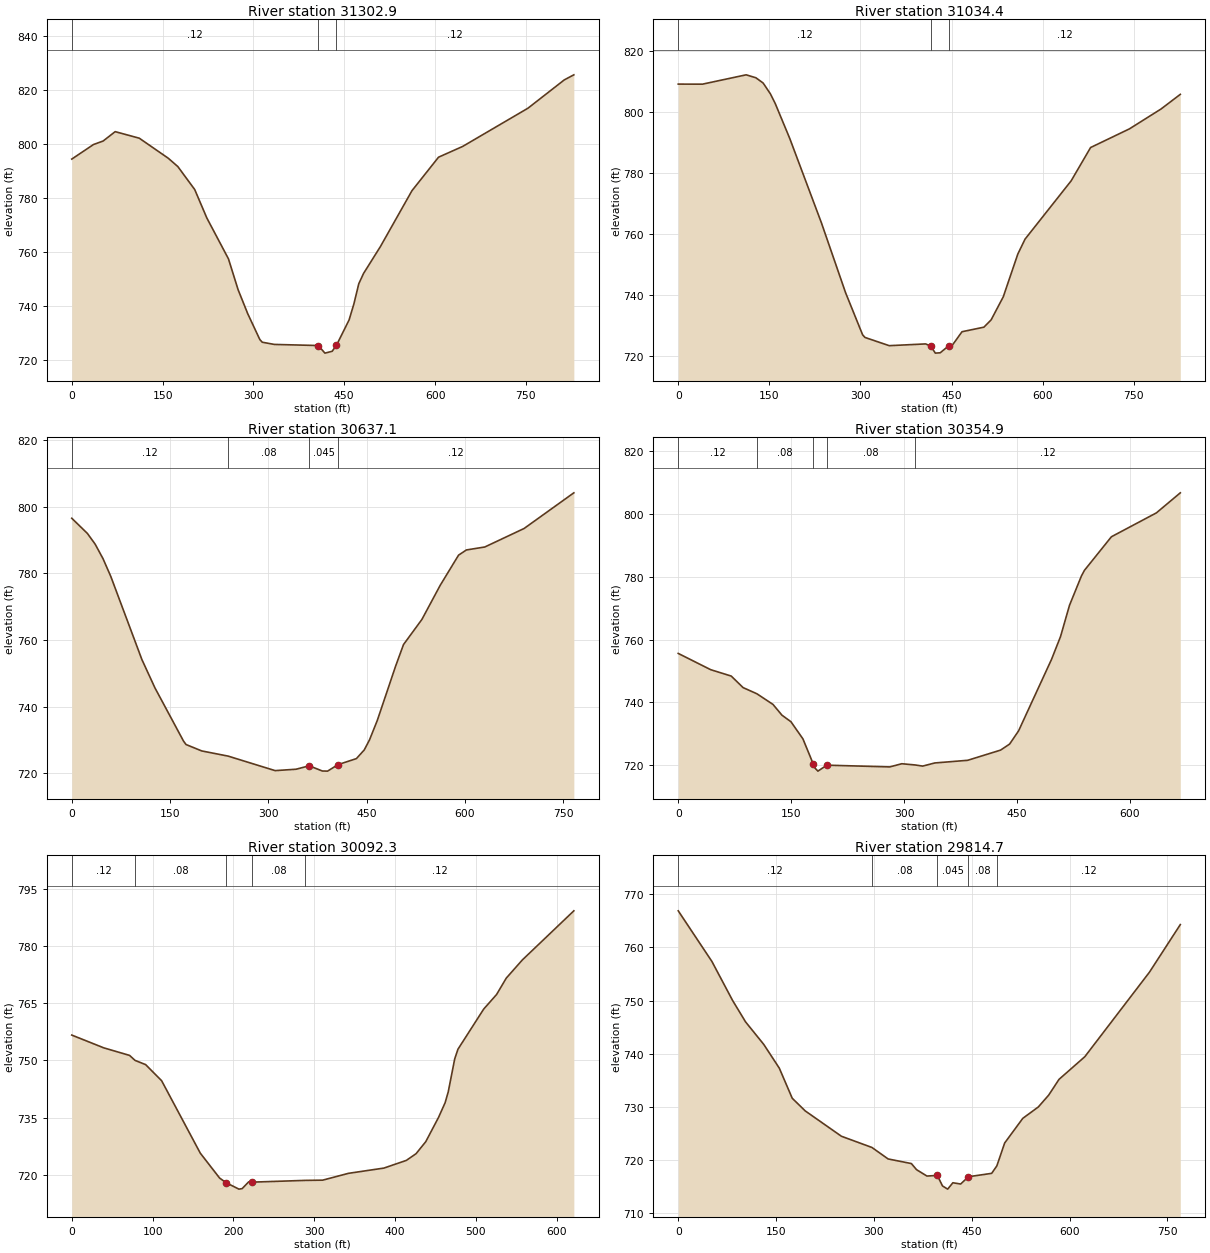
Type RM Length L Ch R = 1 ,31302.9 ,270.6,268.4,265.4
XS GIS Cut Line= 3
     2316535.641      398329.436     2316947.959      398239.297
     2317343.914      398144.342
#Sta/Elev= 30
       0  794.43    35.8  799.83    51.8  801.14    71.7  804.62   111.5  802.19
   159.3  794.76   175.2  791.65   203.1  783.11     223   772.6   258.8  757.38
   274.7  745.94   290.7  736.98   310.6  727.42   314.6  726.43   334.5  725.61
   407.1   725.2   418.1  722.38     430  723.06   437.1  725.27     458   734.7
     466   740.7     474  748.13   481.9  751.97   509.9  762.01   561.8  782.68
   605.7  795.13   645.6  799.13   753.4  813.32   813.3  823.82   829.2  825.72
#Mann= 3 ,-1 , 0
       0     .12       0   407.1    .045       0   437.1     .12       0
Bank Sta=407.1,437.1
XS Rating Curve= 0 ,0
Exp/Cntr=0.3,0.1

Type RM Length L Ch R = 1 ,31034.4 ,402.1,397.4,389.6
XS GIS Cut Line= 3
     2316551.057       398541.13      2316846.53      398540.854
     2317350.437      398372.885
#Sta/Elev= 30
       0  809.02    39.9     809   111.8  812.06   127.8   811.1   139.8  809.37
   151.7  805.84   159.7  802.66   183.7  791.16   235.6  763.65   275.5  740.68
   303.5  726.91   307.4  726.02   347.4  723.32   407.3   723.9   415.6   723.2
   423.3  720.88   431.3  720.99   445.6  723.33   451.2  723.46   467.2  727.89
   503.2  729.38   515.1  731.76   535.1  739.32   559.1  753.35     571  758.23
   646.9  777.33   678.9  788.24   742.8  794.35   794.7  800.84   826.6  805.66
#Mann= 3 ,-1 , 0
       0     .12       0   415.6    .045       0   445.6     .12       0
Bank Sta=415.6,445.6
XS Rating Curve= 0 ,0
Exp/Cntr=0.3,0.1

Type RM Length L Ch R = 1 ,30637.1 ,283.6,282.2,278
XS GIS Cut Line= 3
     2316765.801       398888.51     2316944.187      398887.208
     2317455.905      398598.145
#Sta/Elev= 30
       0  796.48    23.8  791.94    35.7  788.71    47.6  784.39    59.5  779.07
     107  754.13   126.9  745.64   170.5  729.69   174.4  728.65   198.4  726.73
  238.54725.1833   310.3  720.83   342.3  721.25   362.3  722.28   382.3  720.72
   390.3  720.68   406.3  722.63   434.3  724.43   446.3  727.04   454.3  730.04
   466.2  735.88   494.2  752.18   506.2  758.62   534.2  766.13   562.2  776.38
   590.2  785.42   602.2  786.98   630.2  787.86   690.2  793.41   766.1   804.1
#Mann= 4 ,-1 , 0
       0     .12       0  238.54     .08       0   362.3    .045       0
   406.3     .12       0
Bank Sta=362.3,406.3
XS Rating Curve= 0 ,0
Exp/Cntr=0.3,0.1

Type RM Length L Ch R = 1 ,30354.9 ,266.7,262.6,256.2
XS GIS Cut Line= 3
     2317006.687      399189.291     2317022.312      399104.656
     2317504.082      398780.437
#Sta/Elev= 30
       0  755.59      43  750.43    70.4  748.39    86.1  744.73  104.53742.7558
   125.8  739.39   137.8  735.95   149.7  733.88   165.6  728.43  179.14  720.55
   181.5  719.18   185.5  718.18   197.4  720.07     281  719.52   296.9  720.53
  314.65720.1366   324.7  719.78   340.6  720.77   384.4  721.62   428.1  724.86
   440.1  726.78     452  730.97   495.7  753.66   507.7  760.93   519.6  770.86
   535.5  780.22   539.5     782   575.3  792.67     635  800.25   666.8  806.63
#Mann= 5 ,-1 , 0
       0     .12       0  104.53     .08       0  179.14    .045       0
   197.4     .08       0  314.65     .12       0
Bank Sta=179.14,197.4
XS Rating Curve= 0 ,0
Exp/Cntr=0.3,0.1

Type RM Length L Ch R = 1 ,30092.3 ,271.3,277.7,282.9
XS GIS Cut Line= 3
     2317092.624      399336.427     2317208.509       399294.76
     2317561.374      398943.197
#Sta/Elev= 30
       0  756.63    39.7  753.27    71.5   751.3   78.27 749.991    91.4  748.88
   111.2  744.65     159  725.66   182.9  719.13   190.9  717.91   206.8  716.22
   210.8  716.35   218.8  718.11   222.8  718.05  289.02718.5123   310.4  718.57
   342.3  720.36   386.2  721.74     414  723.76     426  725.52     438  728.67
   453.9  735.08   461.9  738.87   465.8  741.73   473.8  750.38   477.8  752.91
   509.7  763.46   525.6  767.27   537.6  771.57   557.5  776.34   621.2  789.22
#Mann= 5 ,-1 , 0
       0     .12       0   78.27     .08       0   190.9    .045       0
   222.8     .08       0  289.02     .12       0
Bank Sta=190.9,222.8
XS Rating Curve= 0 ,0
Exp/Cntr=0.3,0.1

Type RM Length L Ch R = 1 ,29814.7 ,288.5,264.3,236.4
XS GIS Cut Line= 3
     2317176.211      399613.829     2317608.249       399270.02
     2317824.395      399243.979
#Sta/Elev= 30
       0  766.89    51.6  757.37    83.4  750.01   103.3  745.98   131.1  741.76
   154.9   737.3   174.8  731.62   194.6  729.25   250.2  724.47     297722.3585
   321.8   720.2   357.5  719.33   365.4  718.18   381.3  716.98   397.2   717.1
   405.2  715.12   413.1  714.52   421.1  715.72     433  715.48   444.9  716.85
   480.6  717.49  488.52718.9002   500.5   723.2   528.3  727.84   552.1  729.98
     568  732.21   583.8  735.17   623.4  739.44   722.4  755.33   769.8   764.3
#Mann= 5 ,-1 , 0
       0     .12       0     297     .08       0   397.2    .045       0
   444.9     .08       0  488.52     .12       0
Bank Sta=397.2,444.9
XS Rating Curve= 0 ,0
Exp/Cntr=0.3,0.1

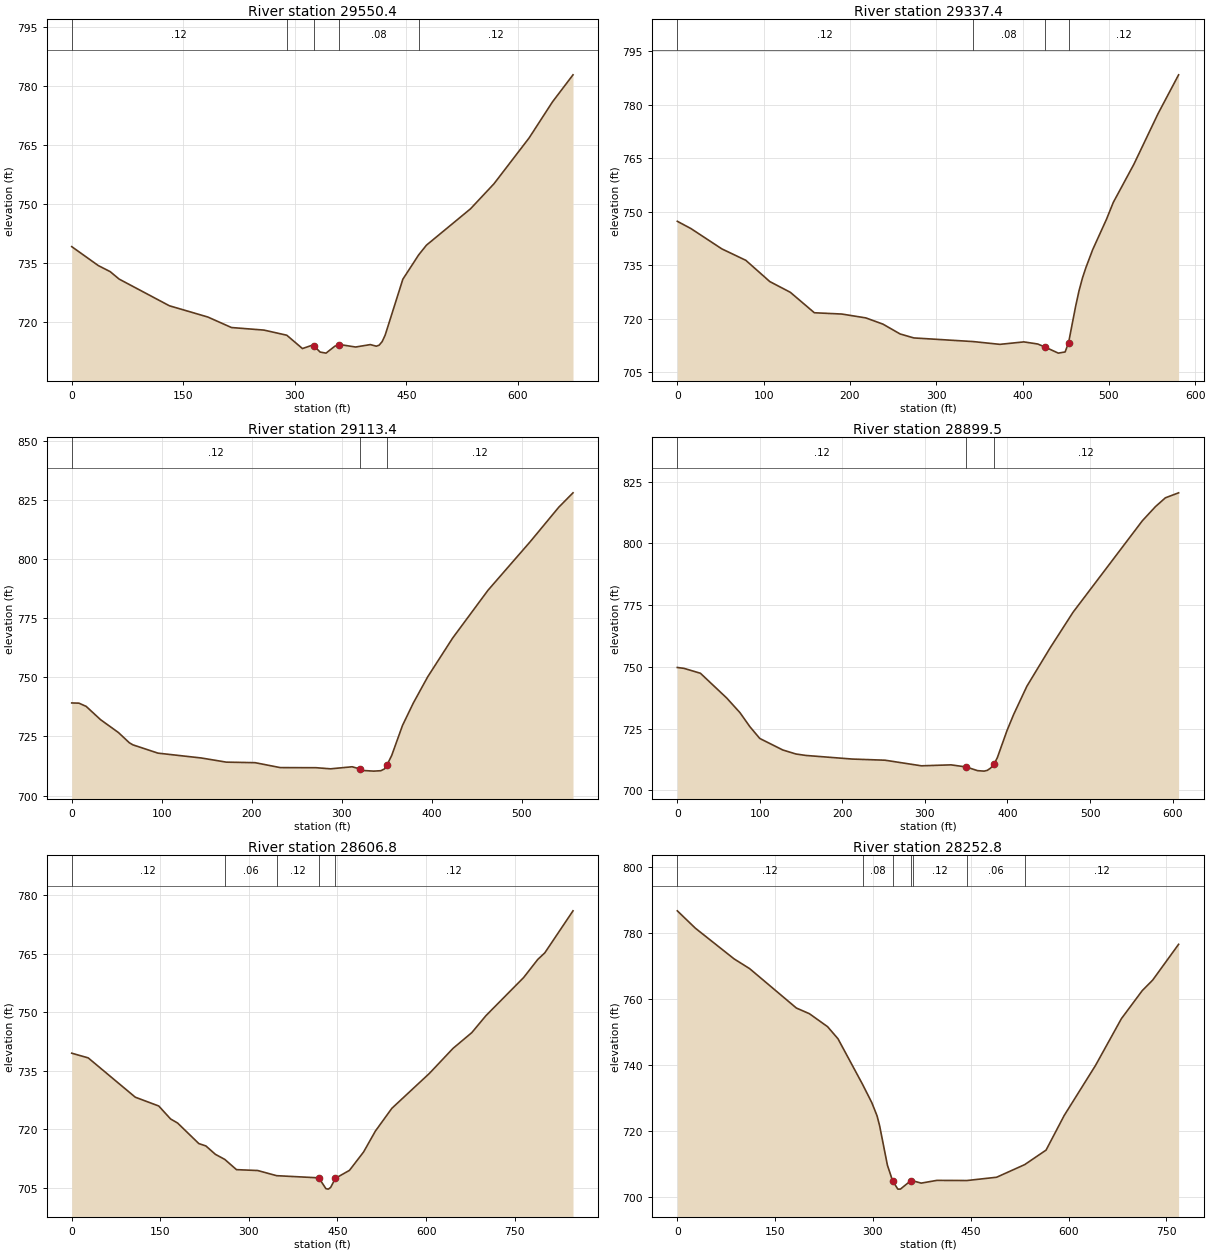
Type RM Length L Ch R = 1 ,29550.4 ,197.2,213,225.5
XS GIS Cut Line= 4
     2317638.197       399857.26     2317675.957      399661.947
     2317711.114      399378.093     2317892.103      399323.406
#Sta/Elev= 30
       0  739.24    35.8  734.42    51.7  732.89    63.7     731   131.3  724.22
     183  721.36   214.8  718.69   258.5  718.04  289.16716.7368   310.2  713.35
   322.1  714.12     326  713.94     334  712.46   341.9  712.19   353.9  713.97
     360  714.38   381.7  713.74   401.5  714.36   409.5  713.95   413.4  714.22
   417.4  715.12   421.4  716.74   445.2  730.96  466.57737.1702     477  739.62
   536.2  748.85   567.7   755.2   614.9  766.83   646.4  776.01     674  782.88
#Mann= 5 ,-1 , 0
       0     .12       0  289.16     .08       0     326    .045       0
     360     .08       0  466.57     .12       0
Bank Sta=326,360
XS Rating Curve= 0 ,0
Exp/Cntr=0.3,0.1

Type RM Length L Ch R = 1 ,29337.4 ,212.9,224,234.7
XS GIS Cut Line= 3
     2317704.603      399908.041      2317747.98      399689.971
     2317944.187      399389.812
#Sta/Elev= 30
       0  747.31    15.9  745.25    51.6  739.57    79.4  736.36   107.2   730.4
     131  727.39   158.8  721.66   190.6   721.3   218.4  720.22   238.3  718.47
   258.2  715.71   274.1   714.6  342.97 713.578   373.8   712.8   401.6  713.49
   417.6   712.9   425.6   712.1   441.5  710.34   449.4  710.67   453.4  713.27
   461.4  723.27   465.4  727.72   469.4  731.34   473.4  734.27   481.3  739.34
   497.3  747.86   505.2   752.6   529.1  763.31     557  777.45   580.9  788.38
#Mann= 4 ,-1 , 0
       0     .12       0  342.97     .08       0   425.6    .045       0
   453.4     .12       0
Bank Sta=425.6,453.4
XS Rating Curve= 0 ,0
Exp/Cntr=0.3,0.1

Type RM Length L Ch R = 1 ,29113.4 ,205.5,213.9,222.1
XS GIS Cut Line= 3
     2317759.291      399853.354     2318088.718       399613.77
     2318187.676      399501.791
#Sta/Elev= 30
       0  739.15       8  739.06      16  737.71      32  732.09    51.9  726.64
    63.9  722.36    67.9  721.45    95.8  717.94   143.8   715.9   171.7  714.14
   203.7  713.91   231.6  711.83   271.6  711.78   287.5  711.31   311.5  712.18
   320.1  711.26   323.5  710.61   335.4  710.34   343.4  710.52   347.4  711.28
   350.1   712.9   355.4  716.95   367.4  729.64   379.4   739.1   395.4  750.19
   423.1  766.57   462.4  786.78   509.6  807.44     541  821.87   556.8  827.94
#Mann= 3 ,-1 , 0
       0     .12       0   320.1    .045       0   350.1     .12       0
Bank Sta=320.1,350.1
XS Rating Curve= 0 ,0
Exp/Cntr=0.3,0.1

Type RM Length L Ch R = 1 ,28899.5 ,289.6,292.7,292.2
XS GIS Cut Line= 2
      2317777.52       399975.75      2318346.53       399763.51
#Sta/Elev= 30
       0  749.76       8  749.41      28  747.42    59.9  737.37    75.9  731.46
    87.9  725.78    99.9  721.01   127.8  716.34   143.8  714.71   155.8  714.13
   211.8  712.67   251.7   712.2   295.7  709.93   331.6  710.32   350.2  709.45
   363.6  707.98   371.6  707.78   375.6   708.1   379.6  709.03   383.6  710.61
   387.6  713.15   399.5  724.29   407.5  730.76   423.5  742.17   451.5  757.62
   479.4  772.12   563.4  809.19   579.3  814.93   591.3  818.48   607.3   820.5
#Mann= 3 ,-1 , 0
       0     .12       0   350.2    .045       0   383.6     .12       0
Bank Sta=350.2,383.6
XS Rating Curve= 0 ,0
Exp/Cntr=0.3,0.1

Type RM Length L Ch R = 1 ,28606.8 ,354.9,354.1,352.9
XS GIS Cut Line= 2
     2317763.197      400243.979     2318578.301         400007.
#Sta/Elev= 30
       0  739.47    27.9  738.27   107.6   728.2   147.4  725.94   167.4  722.62
   179.3  721.58   215.2  716.32   227.2  715.71   243.1  713.58  259.11712.2675
     279  709.64   314.8  709.42  346.85708.0955   418.4  707.54   430.4  704.77
   434.4  704.65   438.4  705.08   446.4  707.41   470.3  709.46   494.2  714.17
   514.1   719.5     542  725.34   605.8  734.32   645.6   740.7   677.5  744.75
   701.4  749.09   765.2  758.85   789.1  763.48     801  765.17   848.8  775.94
#Mann= 5 ,-1 , 0
       0     .12       0  259.11     .06       0  346.85     .12       0
   418.4    .045       0   446.4     .12       0
Bank Sta=418.4,446.4
XS Rating Curve= 0 ,0
Exp/Cntr=0.3,0.1

Type RM Length L Ch R = 1 ,28252.8 ,229.9,229.9,229.7
XS GIS Cut Line= 3
     2317832.207      400602.052     2317912.937       400538.25
     2318540.541      400315.593
#Sta/Elev= 30
       0  786.69    27.7  781.42    87.1  772.12   110.9  769.17   182.6  757.23
   202.6  755.51   230.5  751.57   246.4  747.92  284.18734.0727   298.3  728.55
   306.3  724.57   310.2  721.62   322.2  709.61   330.2  704.84   338.2  702.35
   342.2  702.36   358.1  704.92  362.07704.8207     374  704.17     398     705
  444.19 704.956   489.7  705.95  532.78709.7821   565.5  714.17   593.4  724.69
   641.2  739.78   681.1  754.02     713   762.5     729  765.69   768.8  776.54
#Mann= 7 ,-1 , 0
       0     .12       0  284.18     .08       0   330.2    .045       0
   358.1     .08       0  362.07     .12       0  444.19     .06       0
  532.78     .12       0
Bank Sta=330.2,358.1
XS Rating Curve= 0 ,0
Exp/Cntr=0.3,0.1

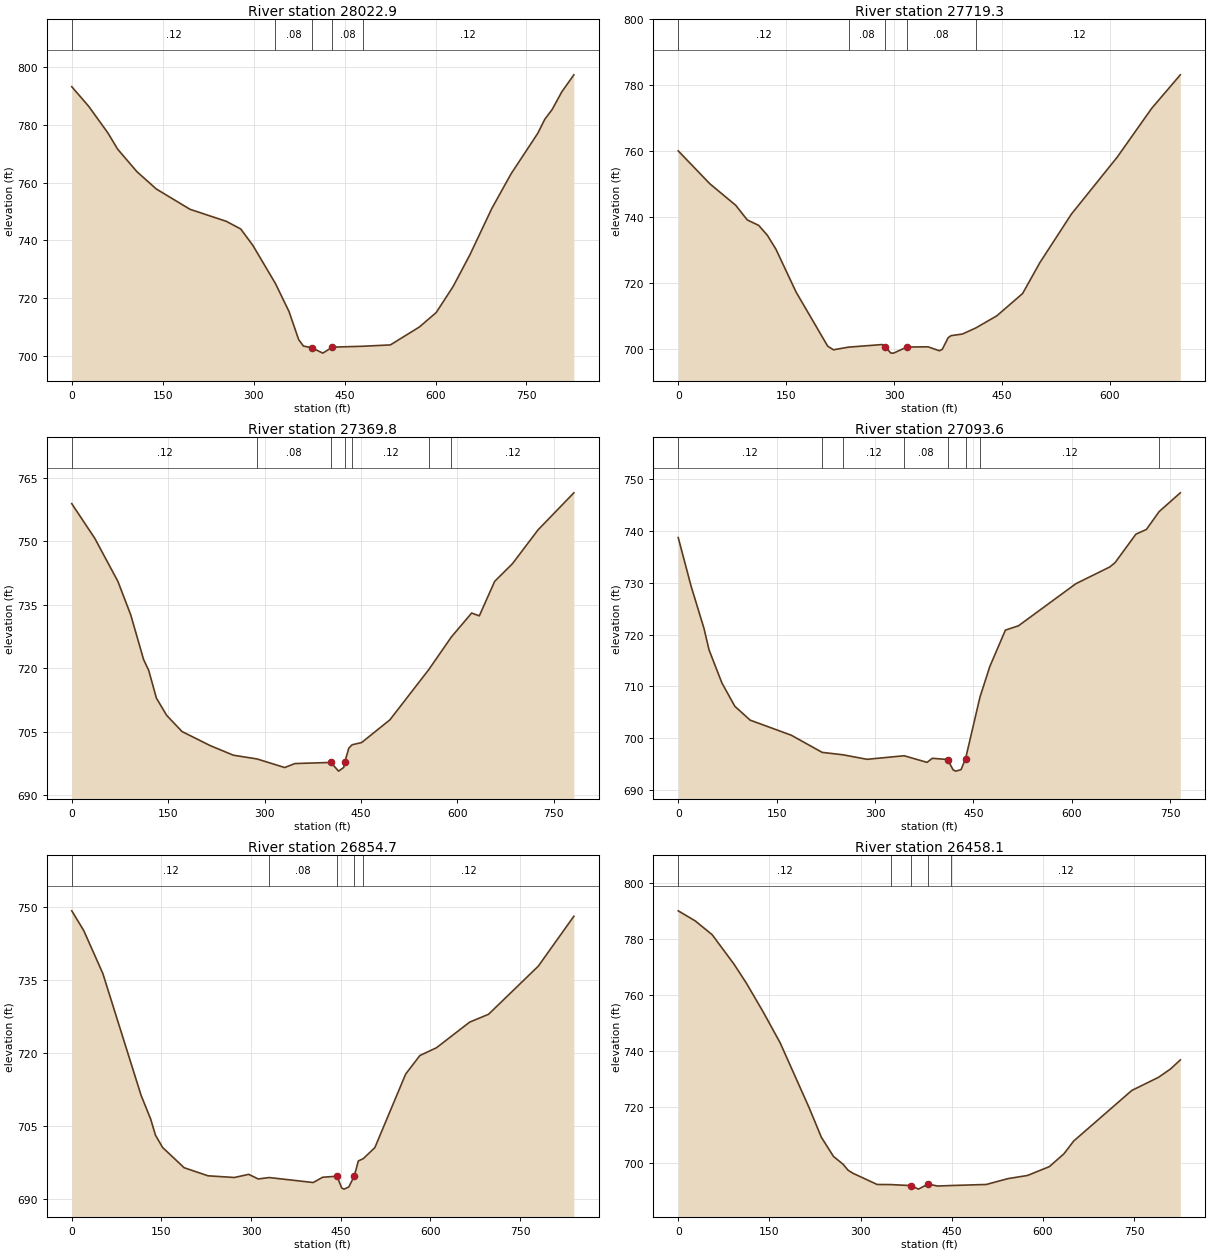
Type RM Length L Ch R = 1 ,28022.9 ,300.4,303.5,301.7
XS GIS Cut Line= 2
     2317872.675      400787.858     2318653.364      400511.382
#Sta/Elev= 30
       0  793.22    27.9  786.44    59.7  777.17    75.6   771.6   107.5  763.76
   139.4  757.78   195.1  750.72   254.8  746.57   278.7  743.91   298.6  738.26
  335.96725.0009   358.4  715.28   374.3  705.55   382.2  703.31   395.5  702.78
   414.1  700.87     430  702.95  479.86703.2494   525.6  703.72   573.4  709.93
   601.2  714.95   629.1  723.98     657  735.06   692.8  750.98   724.7  763.04
   768.5     777   780.4  781.98   792.4  785.31   808.3  791.43   828.2  797.34
#Mann= 5 ,-1 , 0
       0     .12       0  335.96     .08       0   395.5    .045       0
     430     .08       0  479.86     .12       0
Bank Sta=395.5,430
XS Rating Curve= 0 ,0
Exp/Cntr=0.3,0.1

Type RM Length L Ch R = 1 ,27719.3 ,345.9,349.6,351.2
XS GIS Cut Line= 3
     2318100.437      400884.604     2318278.822      400928.875
     2318765.801      400764.812
#Sta/Elev= 30
       0  760.16      44  750.18    79.9  743.68    95.9  739.25   111.9  737.58
   123.9  734.58   135.8  730.36   163.8  717.38   207.7     701   215.7   699.9
  236.69700.7054   283.4  701.49   287.6  700.83   295.3  698.92   299.3  698.89
   317.6  700.73   347.1   700.8     363   699.6     367  700.07     375  703.53
     379  704.18   394.9  704.67  413.47706.5129   442.7  710.19   478.6  716.96
   502.5  726.29   546.3  740.99     610  758.26   657.8  773.01   697.7   783.2
#Mann= 5 ,-1 , 0
       0     .12       0  236.69     .08       0   287.6    .045       0
   317.6     .08       0  413.47     .12       0
Bank Sta=287.6,317.6
XS Rating Curve= 0 ,0
Exp/Cntr=0.3,0.1

Type RM Length L Ch R = 1 ,27369.8 ,280.8,276.1,270.5
XS GIS Cut Line= 3
     2318084.079       401320.26     2318573.093      401186.687
      2318846.53      401165.854
#Sta/Elev= 30
       0   758.9    35.9  750.69    71.8  740.53    91.8  732.61   111.8  722.06
   119.8  719.47   131.7  712.96   147.7  708.88   171.6  705.06   215.5  701.73
   251.5  699.47  288.43698.5817   331.3  696.56   347.3   697.5   403.2  697.76
   415.1  695.71   423.1  696.57  425.03  697.98   431.1  701.15  436.22701.9372
     451  702.46     495  707.83  555.72719.7456  590.66727.4068   622.2  733.06
   634.1  732.39     658  740.54   685.8  744.74   725.5  752.71   781.2  761.46
#Mann= 7 ,-1 , 0
       0     .12       0  288.43     .08       0   403.2    .045       0
  425.03     .08       0  436.22     .12       0  555.72    .016       0
  590.66     .12       0
Bank Sta=403.2,425.03
XS Rating Curve= 0 ,0
Exp/Cntr=0.3,0.1

Type RM Length L Ch R = 1 ,27093.6 ,241.6,239,236.3
XS GIS Cut Line= 3
     2318146.009        401569.5     2318313.978       401582.52
     2318854.343      401328.614
#Sta/Elev= 30
       0  738.74    19.6  729.37    39.2  721.24      47  717.06    66.6  710.68
    86.2  706.19   109.7   703.5   172.4  700.59  219.42697.2809   251.5 696.806
   287.9  695.94  344.45 696.629   379.4  695.35   387.4  696.14   410.6   695.9
   419.2  693.89   423.2  693.66   431.2  693.94  438.12  696.08  460.05707.9561
     475  713.83   498.8  720.88   518.7  721.71   606.3  729.84     658  733.07
     666   733.9   697.8   739.4   713.8  740.31   733.2743.7563   765.5  747.38
#Mann= 8 ,-1 , 0
       0     .12       0  219.42     .06       0   251.5     .12       0
  344.45     .08       0   410.6    .045       0  438.12     .08       0
  460.05     .12       0   733.2    .016       0
Bank Sta=410.6,438.12
XS Rating Curve= 0 ,0
Exp/Cntr=0.3,0.1

Type RM Length L Ch R = 1 ,26854.7 ,396.4,396.6,392.4
XS GIS Cut Line= 3
     2318231.251      401935.612      2318592.64      401713.989
     2318952.662      401505.532
#Sta/Elev= 30
       0  749.29      20  745.24      52   736.4     116  711.35     132  706.48
     140  703.18     152  700.63     188  696.47     228  694.81     272  694.46
     296  695.11     312  694.16  330.27694.4503   403.9  693.43   419.9  694.52
   443.7  694.72   451.7   692.3   455.6  692.07   463.6  692.53  472.78  694.79
   479.4  697.86  487.78698.3456   507.1  700.61   558.6  715.72   582.4  719.54
   610.2  721.14   665.6   726.4   697.3  728.02   780.5  737.91     840  748.17
#Mann= 5 ,-1 , 0
       0     .12       0  330.27     .08       0   443.7    .045       0
  472.78     .08       0  487.78     .12       0
Bank Sta=443.7,472.78
XS Rating Curve= 0 ,0
Exp/Cntr=0.3,0.1

Type RM Length L Ch R = 1 ,26458.1 ,256.8,259.9,262.1
XS GIS Cut Line= 2
     2318332.918      402275.167     2319018.389      401813.839
#Sta/Elev= 30
       0  790.02    27.9  786.44    55.9   781.5    91.8  771.01   111.8  764.36
   139.7  754.02   167.6  743.03   215.5  719.79   235.5  709.32   255.5  702.47
   271.4  699.67   279.4  697.58   287.4  696.49   327.3  692.48  349.51692.4408
   383.2  692.08   395.2  690.82   411.1  692.61   427.1  691.92   448.5   692.1
   506.9  692.48   542.8  694.57   574.8  695.69   610.7  698.84   634.7  703.41
   650.6  707.93   746.4     726   790.3  730.67   810.3  733.68   826.2  736.88
#Mann= 5 ,-1 , 0
       0     .12       0  349.51     .08       0   383.2    .045       0
   411.1     .08       0   448.5     .12       0
Bank Sta=383.2,411.1
XS Rating Curve= 0 ,0
Exp/Cntr=0.3,0.1

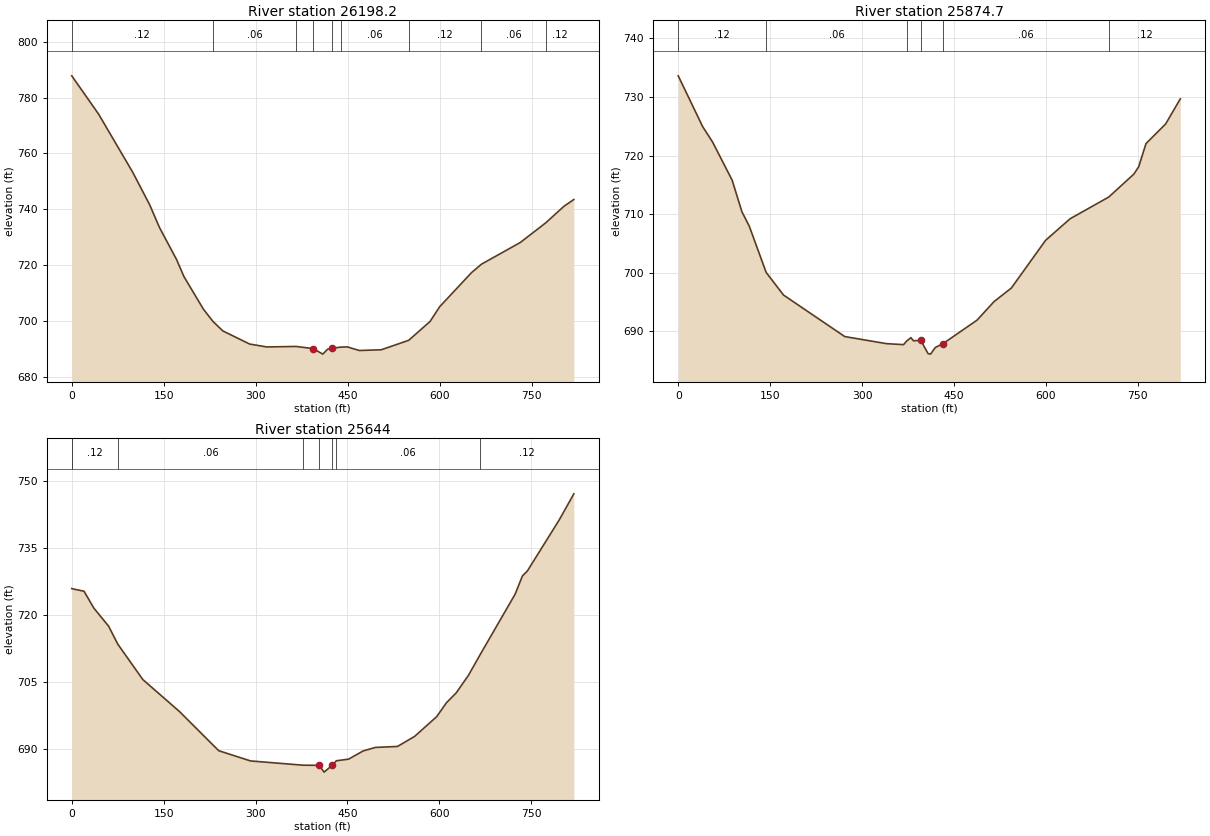
Type RM Length L Ch R = 1 ,26198.2 ,326.1,323.4,321
XS GIS Cut Line= 3
     2318483.278      402442.365     2318841.029      402243.106
     2319198.781      402043.847
#Sta/Elev= 30
       0  787.77    43.7  774.08    99.4  753.24   127.2  741.53   143.1  733.43
     171  721.94   182.9   715.9   214.7  704.19  230.22699.8184   246.5  696.38
   290.2  691.69   318.1  690.65  365.75690.8289   393.6  690.07   409.5  688.08
   417.4  689.86   424.5  690.19   438.6690.5917   449.3  690.68   469.1  689.38
   504.9  689.64   549.6693.0275   584.4  699.77   600.3   705.1     652  717.25
  668.24720.2891   731.5  728.05  773.14735.1068   803.1  741.08     819  743.46
#Mann= 9 ,-1 , 0
       0     .12       0  230.22     .06       0  365.75     .12       0
   393.6    .045       0   424.5     .12       0   438.6     .06       0
   549.6     .12       0  668.24     .06       0  773.14     .12       0
Bank Sta=393.6,424.5
XS Rating Curve= 0 ,0
Exp/Cntr=0.3,0.1

Type RM Length L Ch R = 1 ,25874.7 ,236.4,230.7,224.8
XS GIS Cut Line= 2
      2318713.63      402712.248     2319394.802       402256.25
#Sta/Elev= 30
       0  733.61      40  724.91      56  722.32      88  715.79     104  710.39
     116  707.93  143.55700.0356   171.9  696.17   271.9  689.08   339.9  687.87
   367.9   687.7  372.86688.3056   379.9   688.9   383.9  688.36   395.9  688.44
   407.9  686.17   411.9  686.08   419.8  687.22  432.33687.8737   487.8  691.88
   515.8  695.07   543.8  697.36   599.8  705.52   639.8   709.2  702.91 712.911
   743.7  716.81   751.7  718.07   763.7  722.04   795.7  725.38   819.7  729.68
#Mann= 6 ,-1 , 0
       0     .12       0  143.55     .06       0  372.86     .12       0
   395.9    .045       0  432.33     .06       0  702.91     .12       0
Bank Sta=395.9,432.33
XS Rating Curve= 0 ,0
Exp/Cntr=0.3,0.1

Type RM Length L Ch R = 1 ,25644   ,392,399.5,404.5
XS GIS Cut Line= 2
     2318914.268       402947.19     2319495.779      402369.419
#Sta/Elev= 30
       0  725.91     .31725.8829      20  725.31      36  721.53      60   717.5
   75.32713.4057     116   705.5   175.9  698.32   239.9  689.54   291.9  687.24
  377.82 686.282   403.9  686.26   411.9  684.73  425.64  686.32  431.99687.2758
   451.9  687.64   475.8  689.49   495.8  690.27   531.8  690.49   559.8  692.75
   595.8  697.18   611.8  700.31   627.8  702.53   647.8  706.49  666.07710.9246
   723.8  724.64   735.8  728.75   743.8  729.85   795.8   741.3   819.7  747.16
#Mann= 8 ,-1 , 0
       0     .06       0     .31     .12       0   75.32     .06       0
  377.82     .12       0   403.9    .045       0  425.64     .12       0
  431.99     .06       0  666.07     .12       0
Bank Sta=403.9,425.64
XS Rating Curve= 0 ,0
Exp/Cntr=0.3,0.1