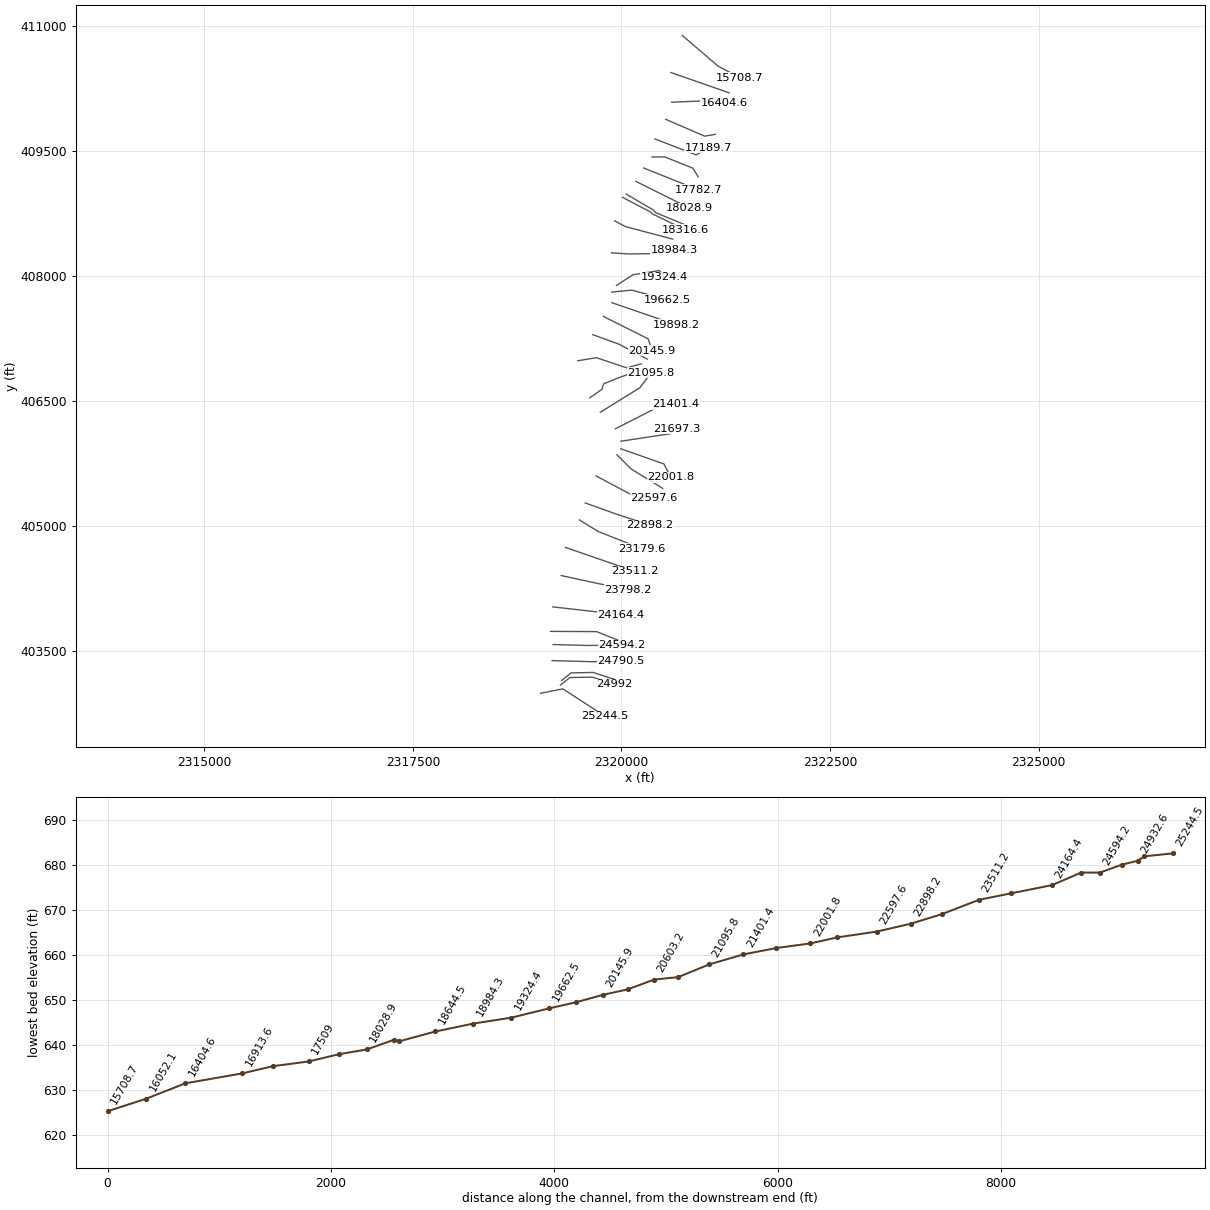
HEC-RAS study SIRJOHNSRN.prj: SIRJOHNSRN

--- SIRJOHNSRN.g01 (geometry) --- (continued)

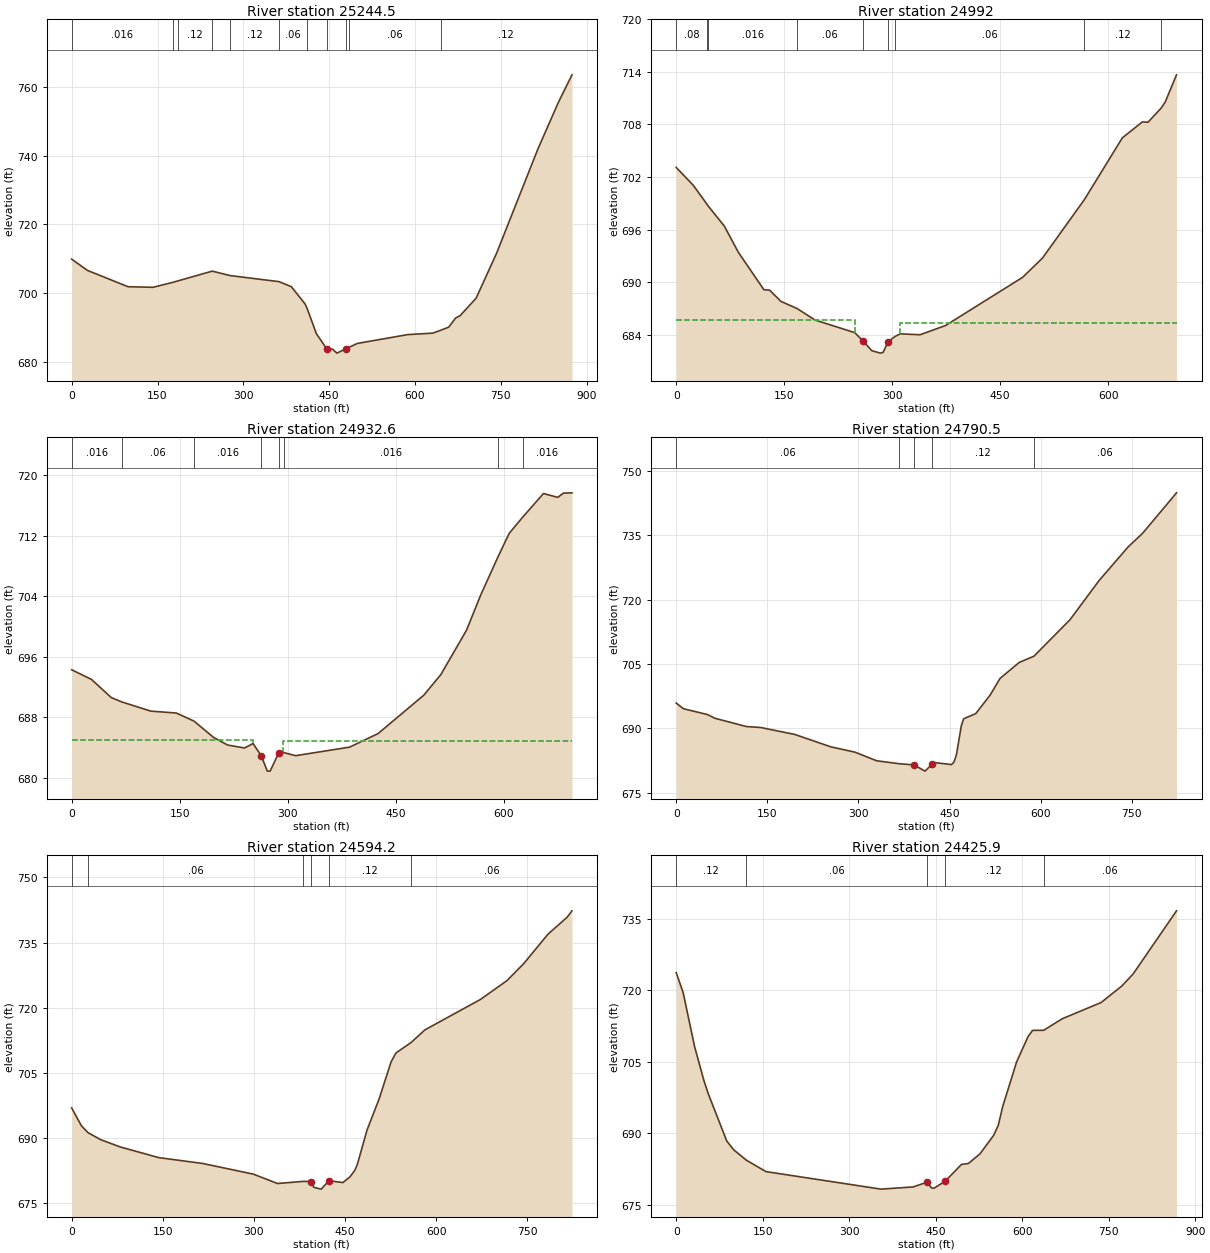
Type RM Length L Ch R = 1 ,25244.5 ,234,252.5,269.9
XS GIS Cut Line= 3
     2319030.124      402997.885     2319297.051       403051.27
      2319802.19      402723.552
#Sta/Elev= 30
       0   709.9    27.6  706.62    98.6  701.87     142   701.7  176.69703.1398
  185.31703.5561  245.73706.4133   276.5705.1232   362.5703.3485   383.9  701.88
   407.8  696.88  411.53695.5465   427.7  688.19  446.15683.7112   455.6  683.71
   463.6  682.54     479   683.8  483.93684.1638   499.5  685.37   587.2  687.93
   631.1  688.36   644.9689.1908     659  690.12     671  692.77     679  693.47
   706.9  698.55   742.8  711.69   814.5  741.84   850.4  755.46   874.4  763.56
#Mann= 11 ,-1 , 0
       0    .016       0  176.69     .06       0  185.31     .12       0
  245.73     .08       0   276.5     .12       0   362.5     .06       0
  411.53     .12       0  446.15    .045       0     479     .12       0
  483.93     .06       0   644.9     .12       0
Bank Sta=446.15,479
XS Rating Curve= 0 ,0
Exp/Cntr=0.3,0.1

Type RM Length L Ch R = 1 ,24992   ,58.9,59.5,59.6
XS GIS Cut Line= 4
     2319268.405      403095.541     2319381.687      403186.687
     2319646.009      403191.895     2319917.381       403104.36
#Sta/Elev= 30
       0  703.09    23.6  701.06   42.96698.8632   44.19698.7062    66.8   696.4
    86.4  693.39   121.8  689.13   129.7  689.08   145.4   687.8  168.05 686.973
   192.8  685.67     248  684.23   259.8  683.24   271.7  682.17   283.5  681.89
   287.4  681.98  294.44  683.21  304.23683.8024   311.1  684.09   338.8  683.99
   374.3  685.05   481.1  690.54   508.8  692.75  566.99699.4236   619.7  706.47
   647.4  708.28   655.3  708.25  673.46709.8518   679.1  710.54   694.9  713.66
#Mann= 9 ,-1 , 0
       0     .08       0   42.96     .06       0   44.19    .016       0
  168.05     .06       0   259.8    .045       0  294.44     .12       0
  304.23     .06       0  566.99     .12       0  673.46     .06       0
#XS Ineff= 2 , 0
           248.5  685.62  311.35          685.38
Permanent Ineff=
       F       F
Bank Sta=259.8,294.44
XS Rating Curve= 0 ,0
Exp/Cntr=0.3,0.1

Type RM Length L Ch R = 1 ,24932.6 ,143.7,142,140.1
XS GIS Cut Line= 4
     2319282.728      403151.531     2319396.009      403242.677
     2319660.332      403247.885     2319931.704      403160.349
#Sta/Elev= 30
       0  694.29    27.5  693.02      55  690.62   69.47 690.051     110  688.83
   145.4  688.58  169.95687.5099   196.7  685.39   216.4  684.36   240.1  683.97
   251.9  684.55   263.2  682.96   271.7  680.92   275.6  680.91   287.4  683.28
  294.45683.3605   311.1  682.95   386.1  684.08   425.6  685.87     489  690.93
   512.7  693.65   548.4  699.51   568.2  704.18  592.58709.2896   607.8  712.32
  626.56714.4512   655.3  717.56   675.1  717.05     683  717.61   694.9  717.65
#Mann= 8 ,-1 , 0
       0    .016       0   69.47     .06       0  169.95    .016       0
   263.2    .045       0   287.4     .06       0  294.45    .016       0
  592.58     .12       0  626.56    .016       0
#XS Ineff= 2 , 0
          251.39  685.07  294.01          684.93
Permanent Ineff=
       F       F
Bank Sta=263.2,287.4
XS Rating Curve= 0 ,0
Exp/Cntr=0.3,0.1

Type RM Length L Ch R = 1 ,24790.5 ,195.9,196.3,196.7
XS GIS Cut Line= 3
     2319168.938      403389.637     2319642.103      403376.791
     2319992.501      403381.924
#Sta/Elev= 30
       0  695.91    11.9  694.59    51.7  693.22    63.6  692.37   115.4  690.44
   139.2  690.21   194.9  688.61   254.6  685.71   294.4  684.47   330.1  682.46
  366.33681.7921   391.5   681.5   409.7  680.05   421.5  681.68   425.6  682.04
   453.4  681.57   457.4  682.18   461.4  683.84   469.4   690.6   473.3  692.24
   493.2  693.45   517.1   697.8   533.1  701.63   564.9  705.38  589.11706.8257
   648.6  715.35   696.3  724.45   744.1  732.28     768  735.46   823.8  744.88
#Mann= 5 ,-1 , 0
       0     .06       0  366.33     .12       0   391.5    .045       0
   421.5     .12       0  589.11     .06       0
Bank Sta=391.5,421.5
XS Rating Curve= 0 ,0
Exp/Cntr=0.3,0.1

Type RM Length L Ch R = 1 ,24594.2 ,167.3,168.4,167.6
XS GIS Cut Line= 3
     2319180.657      403582.346     2319595.271      403571.346
      2320004.22      403574.632
#Sta/Elev= 30
       0  696.97      16  692.86   26.97691.2707    47.9  689.66    79.8     688
   143.6  685.53   215.4   684.2   299.1  681.74     339  679.58   381.6680.0777
   393.6  680.02   398.8   678.7   410.8  678.29   423.6  680.23   446.5   679.8
   458.4  681.15   466.4  682.68   470.4  684.02   486.2  691.86   506.1  699.01
   525.9  707.58   533.9  709.62  558.75712.0086   581.5  714.92   672.8  721.91
   716.5  726.24   744.3  730.18     784  736.91   815.8  740.86   823.7  742.31
#Mann= 6 ,-1 , 0
       0     .12       0   26.97     .06       0   381.6     .12       0
   393.6    .045       0   423.6     .12       0  558.75     .06       0
Bank Sta=393.6,423.6
XS Rating Curve= 0 ,0
Exp/Cntr=0.3,0.1

Type RM Length L Ch R = 1 ,24425.9 ,261.1,261.5,257.7
XS GIS Cut Line= 3
     2319148.614      403740.072     2319703.228      403737.085
     2319993.666      403620.281
#Sta/Elev= 30
       0  723.74      12  719.58    31.9  708.21    47.9  701.14    55.9  698.22
    87.8  688.37    99.8  686.54  121.61684.3729   155.6  681.97   355.1  678.29
     411  678.75   434.9  679.74   442.9  678.54   446.9  678.47   466.3  679.93
   494.8  683.48   506.7  683.67   526.7  685.68   550.6  689.59   558.6  691.71
   566.5  695.74   590.3  704.97   610.1  710.29     618  711.62  637.24711.6384
   669.5  714.06   736.9  717.47   772.6  720.91   792.4  723.46   867.7  736.72
#Mann= 5 ,-1 , 0
       0     .12       0  121.61     .06       0   434.9    .045       0
   466.3     .12       0  637.24     .06       0
Bank Sta=434.9,466.3
XS Rating Curve= 0 ,0
Exp/Cntr=0.3,0.1

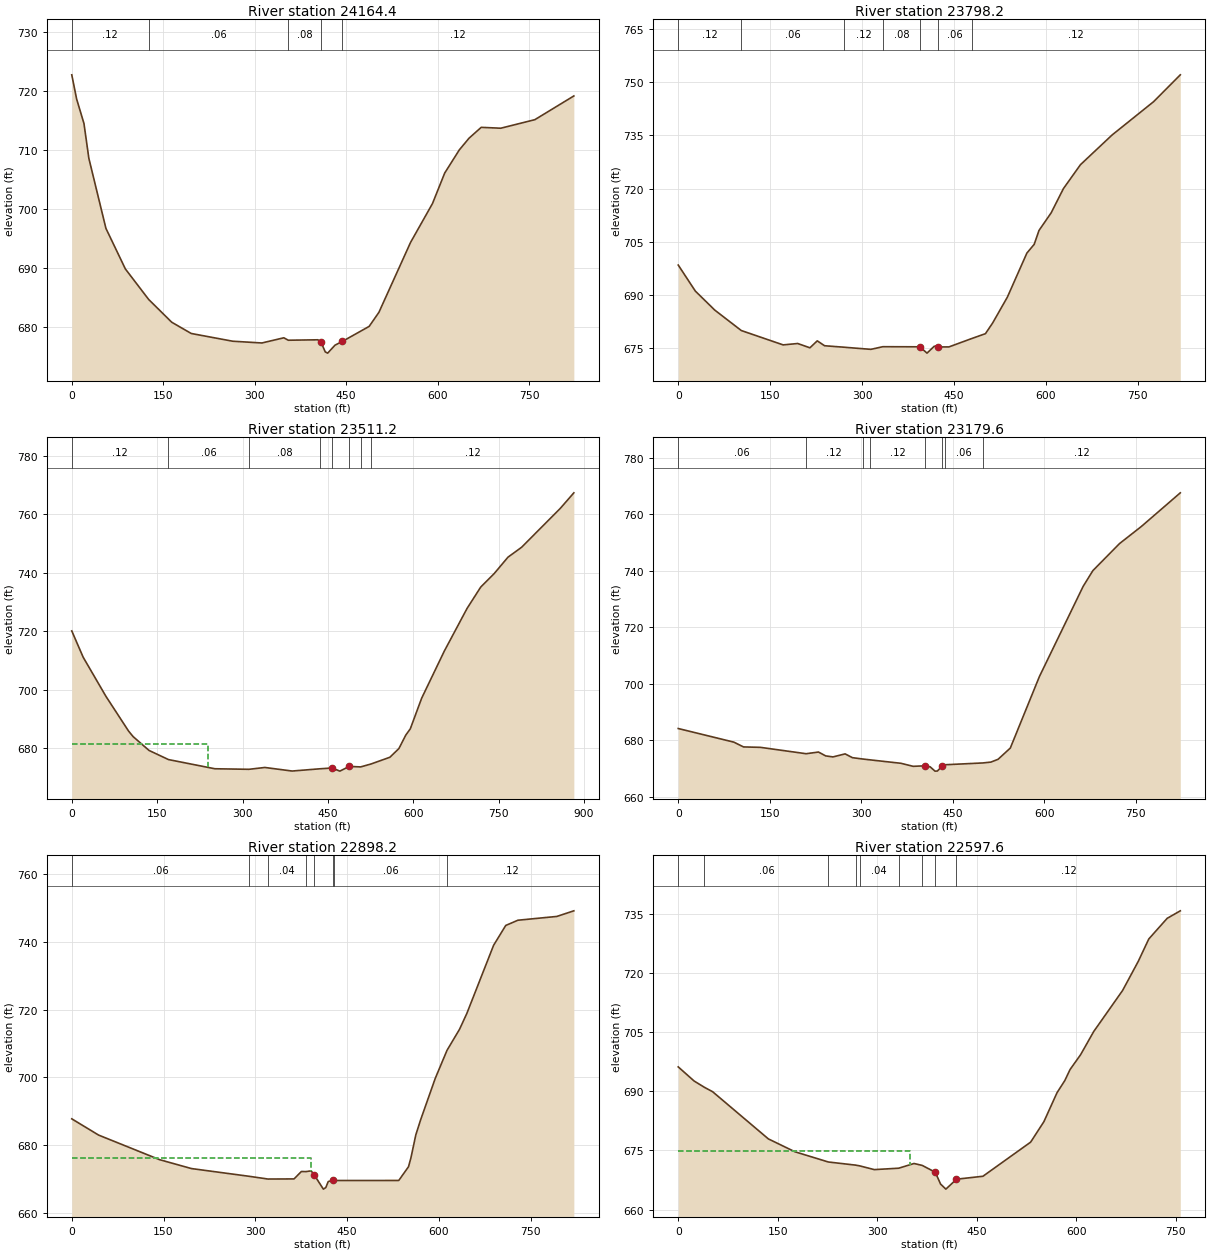
Type RM Length L Ch R = 1 ,24164.4 ,365.2,366.2,362.5
XS GIS Cut Line= 2
     2319175.908      404034.015     2319994.088      403941.111
#Sta/Elev= 30
       0  722.67       8  718.56      20  714.42      28  708.53      56  696.65
    87.9  689.77  126.12 684.597   163.9  680.74   195.9  678.83   263.8  677.52
   311.8  677.22   347.8   678.1  355.09677.6855   403.7  677.76   408.7  677.38
   415.7  675.71   419.7   675.5   431.7  676.85   443.7  677.48   487.7  680.03
   503.7  682.41   555.6  694.26   591.6  700.86   611.6  706.02   635.6  709.95
   651.6  711.94   671.5  713.77   703.5  713.62   759.5  715.07   823.4  719.09
#Mann= 5 ,-1 , 0
       0     .12       0  126.12     .06       0  355.09     .08       0
   408.7    .045       0   443.7     .12       0
Bank Sta=408.7,443.7
XS Rating Curve= 0 ,0
Exp/Cntr=0.3,0.1

Type RM Length L Ch R = 1 ,23798.2 ,290.7,286.9,283.1
XS GIS Cut Line= 3
     2319277.042      404409.403     2319677.642      404322.296
     2320078.687      404239.918
#Sta/Elev= 30
       0  698.49    27.9  691.16    59.7  685.79  102.92680.0425   171.2     676
     195  676.39   214.9  675.18   226.9  677.14   238.8  675.76  270.69675.3444
   314.4  674.74  333.93675.4896   394.4  675.46     406  673.68   417.9  675.63
   424.4  675.42   441.8  675.43  478.62677.7664   501.4  679.16   513.3  682.22
   537.2  689.47     569  701.86   580.9  704.31   588.8  708.24   608.7  713.22
   628.6  720.01   656.4  726.75   708.1  735.13   775.7  744.49   819.4  752.07
#Mann= 7 ,-1 , 0
       0     .12       0  102.92     .06       0  270.69     .12       0
  333.93     .08       0   394.4    .045       0   424.4     .06       0
  478.62     .12       0
Bank Sta=394.4,424.4
XS Rating Curve= 0 ,0
Exp/Cntr=0.3,0.1

Type RM Length L Ch R = 1 ,23511.2 ,328.3,331.6,330.2
XS GIS Cut Line= 2
     2319328.301      404746.583     2320161.821      404458.134
#Sta/Elev= 30
       0  720.19      20  711.21    59.9  697.86    99.8  685.94   107.8  684.05
   135.7  679.33  169.85676.2006   251.4  673.06  311.33672.8712   339.2   673.5
   387.1  672.28  435.69673.0438   457.4  673.32   470.9  672.25   487.4  673.86
  507.43673.6882  525.89   674.7   558.8  676.99   574.7  679.97   586.7  684.55
   594.7  686.71   614.6  697.16   654.5  713.31   694.4  727.87   718.4  735.17
   742.3  739.84   766.3   745.4   790.2  748.78   858.1  762.06     882   767.4
#Mann= 8 ,-1 , 0
       0     .12       0  169.85     .06       0  311.33     .08       0
  435.69     .12       0   457.4    .045       0   487.4     .12       0
  507.43     .06       0  525.89     .12       0
#XS Ineff= 2 , 0
          238.77  681.58
Permanent Ineff=
       F       F
Bank Sta=457.4,487.4
XS Rating Curve= 0 ,0
Exp/Cntr=0.3,0.1

Type RM Length L Ch R = 1 ,23179.6 ,279.8,281.4,282.7
XS GIS Cut Line= 3
     2319496.592      405075.751     2319718.926      404937.989
     2320241.062       404732.26
#Sta/Elev= 30
       0  684.15    91.2  679.33     107  677.64   134.7  677.49  209.56675.2387
   229.8  675.83   241.7  674.46   253.6  674.11   273.5  675.18   285.4  673.84
  302.16673.3703  314.18673.0716     365  671.85   384.9  670.78   404.8  670.96
   412.8  670.61   420.8  669.08   424.7  669.11   432.7  670.91  437.18671.3352
  498.95 671.969   512.3  672.27   524.2  673.27   544.2  677.24   591.9  702.54
   663.6  734.44   679.5     740   723.2  749.57   759.1  755.64   822.8  767.52
#Mann= 8 ,-1 , 0
       0     .06       0  209.56     .12       0  302.16     .08       0
  314.18     .12       0   404.8    .045       0   432.7     .12       0
  437.18     .06       0  498.95     .12       0
Bank Sta=404.8,432.7
XS Rating Curve= 0 ,0
Exp/Cntr=0.3,0.1

Type RM Length L Ch R = 1 ,22898.2 ,302.5,300.6,294.7
XS GIS Cut Line= 3
      2319565.46      405279.248     2319952.683      405141.168
     2320341.561       405013.48
#Sta/Elev= 30
       0  687.72    43.9  682.91   143.7  675.63   195.6  673.01  289.49670.7312
  320.64669.9133   363.2  669.95   375.2  672.14  382.96672.1148   391.2  672.34
   396.1  671.16   411.1  666.93   415.1  667.39     419  669.15   426.1  669.58
   428.9 669.484   534.3  669.49   550.2  673.54   554.2  676.18   562.1  682.93
   570.1  687.46   593.9  699.67   613.1707.9583   633.6   714.2   645.6  718.91
   689.3  739.05   709.1  744.91     729  746.46   792.6  747.58   820.4  749.24
#Mann= 8 ,-1 , 0
       0     .06       0  289.49     .08       0  320.64     .04       0
  382.96     .12       0   396.1    .045       0   426.1     .12       0
   428.9     .06       0   613.1     .12       0
#XS Ineff= 2 , 0
          391.53   676.2
Permanent Ineff=
       F       F
Bank Sta=396.1,426.1
XS Rating Curve= 0 ,0
Exp/Cntr=0.3,0.1

Type RM Length L Ch R = 1 ,22597.6 ,354,355.5,350.9
XS GIS Cut Line= 3
     2319696.682      405602.841     2320179.864      405345.541
     2320389.499      405341.635
#Sta/Elev= 30
       0  696.16      24  692.58   39.52690.9892    51.9  689.87   135.9  677.93
   175.8  674.68  226.34672.0811  267.38671.2888  273.36671.1119   295.7  670.15
  332.49670.5112   355.6   671.7  367.95671.2115   387.6  669.49   395.6  666.49
   403.6  665.21   419.6  667.72   459.5  668.47   531.4  677.11   551.4  682.29
   571.2  689.63     583  692.72   590.9  695.51   606.8  699.26   626.5  705.11
   670.1  715.52   693.8  722.92   709.6  728.56   737.3  733.78   757.1  735.68
#Mann= 9 ,-1 , 0
       0     .12       0   39.52     .06       0  226.34     .12       0
  267.38     .06       0  273.36     .04       0  332.49     .06       0
  367.95     .12       0   387.6    .045       0   419.6     .12       0
#XS Ineff= 2 , 0
          350.19   674.8
Permanent Ineff=
       F       F
Bank Sta=387.6,419.6
XS Rating Curve= 0 ,0
Exp/Cntr=0.3,0.1

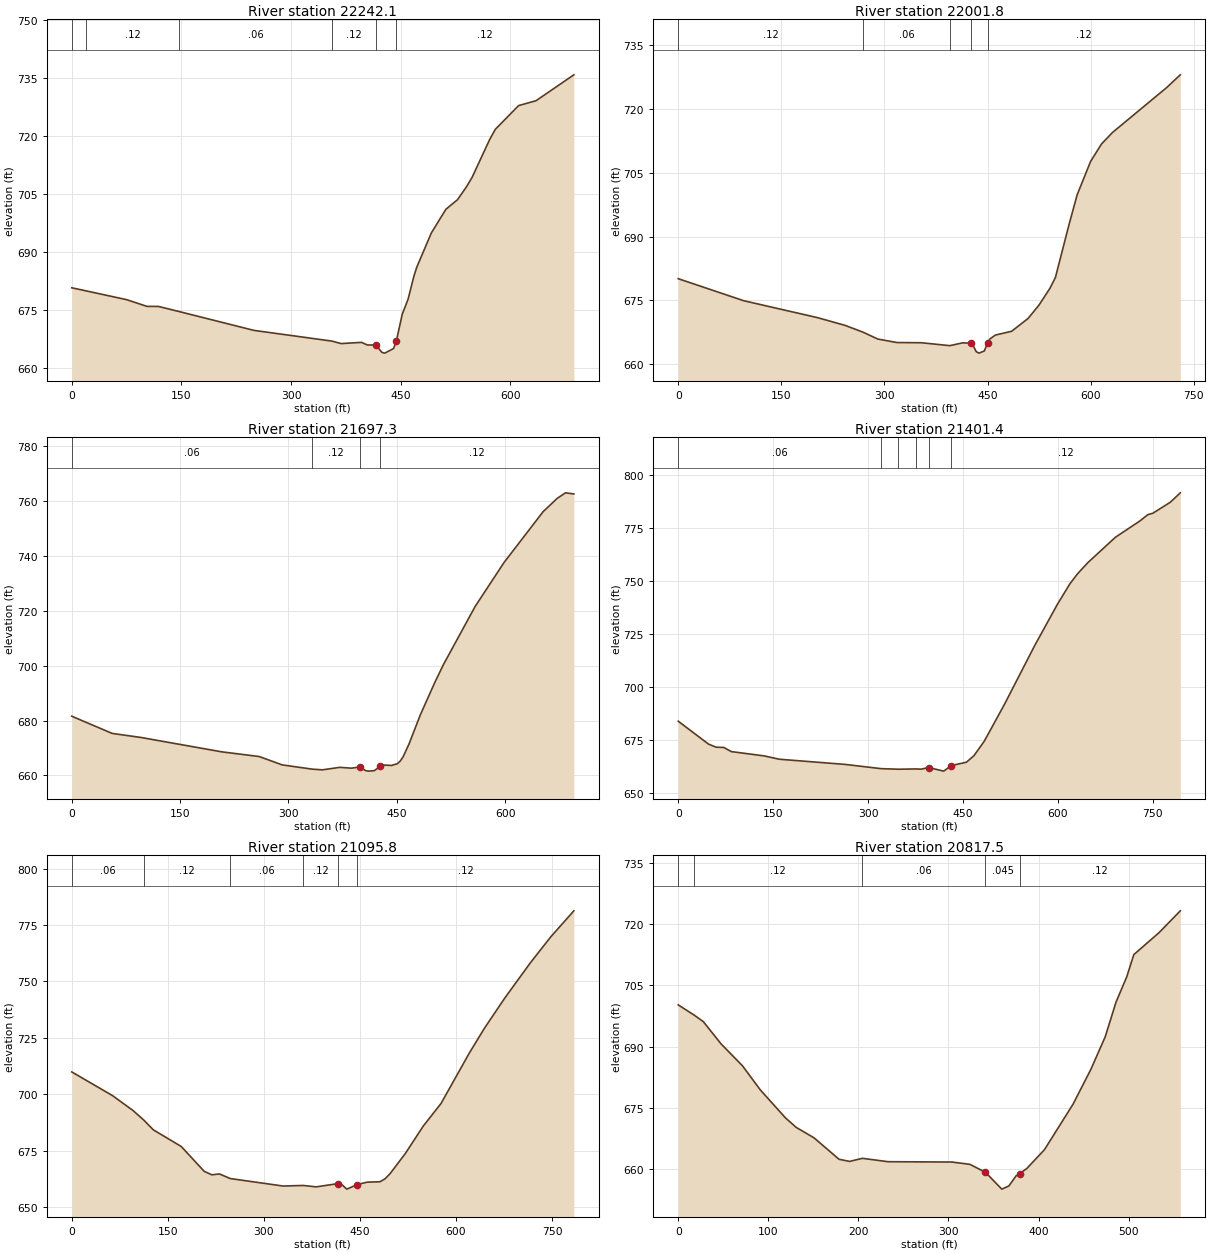
Type RM Length L Ch R = 1 ,22242.1 ,233.2,240.3,245.7
XS GIS Cut Line= 3
     2319945.063      405857.619     2320112.155      405689.291
     2320494.968      405453.614
#Sta/Elev= 30
       0   680.8   19.85679.9971    75.1  677.73   102.8     676   118.6  675.98
  147.23674.6418   249.1  669.79   355.6667.0284   368.5  666.38   396.3  666.69
   404.3  666.02   415.9     666   424.2   664.1   428.1  663.91   440.1   665.1
     444  667.09     452  673.97     460  677.86   467.9  683.77   471.9  686.14
   491.8  694.98   511.7   701.1   527.6  703.58   539.5  706.81   547.5  709.33
   571.4  719.07   579.3  721.77   611.1   727.9     635  729.17   686.7  735.86
#Mann= 6 ,-1 , 0
       0     .06       0   19.85     .12       0  147.23     .06       0
   355.6     .12       0   415.9    .045       0     444     .12       0
Bank Sta=415.9,444
XS Rating Curve= 0 ,0
Exp/Cntr=0.3,0.1

Type RM Length L Ch R = 1 ,22001.8 ,289.5,304.5,318.9
XS GIS Cut Line= 3
     2319991.829      405928.994     2320509.291      405746.583
     2320592.624      405585.125
#Sta/Elev= 30
       0  680.09    95.4   674.9   202.8  670.92   242.5  669.12  268.72667.5154
   290.2   665.9   318.1  665.07   353.8  665.02   395.1664.3387   413.5  664.99
   425.4  664.92   429.4  664.26   433.4  662.95   437.4  662.58   445.3  663.09
  450.26  665.07   453.2  665.88   461.2  666.82   485.1  667.73   508.9  670.73
   524.8  673.87   540.7  677.81   548.7  680.37   568.4  692.74   580.3  699.81
     600   707.7   615.8  711.78   631.6  714.46   710.6  725.05   730.4  728.04
#Mann= 5 ,-1 , 0
       0     .12       0  268.72     .06       0   395.1     .12       0
   425.4    .045       0  450.26     .12       0
Bank Sta=425.4,450.26
XS Rating Curve= 0 ,0
Exp/Cntr=0.3,0.1

Type RM Length L Ch R = 1 ,21697.3 ,286.1,295.9,305.5
XS GIS Cut Line= 3
     2319992.949      406019.364     2320584.812      406108.562
     2320661.634      406167.156
#Sta/Elev= 30
       0  681.57    55.9   675.3    95.8  673.82   207.5  668.59   259.4  666.88
   291.3  663.83  332.96662.2708   347.2  662.02   371.1  662.93   387.1  662.63
     399  663.06     407  661.72     411  661.55     419  661.73     427  663.27
     431  663.77   442.9  663.62   450.9  664.26   454.9  665.25   458.9  666.83
   466.9   671.4   482.8  682.16   502.8  693.94   514.8  700.47   558.6  721.61
   598.6  737.62   652.6   756.1     672  760.95   683.6     763   695.2   762.6
#Mann= 4 ,-1 , 0
       0     .06       0  332.96     .12       0     399    .045       0
     427     .12       0
Bank Sta=399,427
XS Rating Curve= 0 ,0
Exp/Cntr=0.3,0.1

Type RM Length L Ch R = 1 ,21401.4 ,302.4,305.6,307.3
XS GIS Cut Line= 3
     2319925.957      406167.156     2320509.291      406465.333
     2320647.312      406460.125
#Sta/Elev= 30
       0  683.75    47.9   672.9    59.9  671.45    71.9  671.34    83.9  669.37
   135.8  667.34   159.8  665.76   263.6  663.32  320.43661.3159  347.91661.0331
  375.03661.1705   383.5  661.06   395.5  661.84   419.4  660.14   431.4  662.75
   455.4  664.37   467.4  667.51   483.4  674.24   515.3  691.66   563.2  719.53
   599.2  739.09   619.2  748.88   631.2  753.54   647.1  758.69   690.6  770.68
   730.1  778.56   741.9   781.4   749.8  782.04   777.5  787.27   793.2   791.7
#Mann= 6 ,-1 , 0
       0     .06       0  320.43     .12       0  347.91     .06       0
  375.03     .12       0   395.5    .045       0   431.4     .12       0
Bank Sta=395.5,431.4
XS Rating Curve= 0 ,0
Exp/Cntr=0.3,0.1

Type RM Length L Ch R = 1 ,21095.8 ,282.8,278.4,271.7
XS GIS Cut Line= 3
      2319746.27      406366.375     2320222.832      406661.947
     2320356.947      406840.333
#Sta/Elev= 30
       0  709.87    63.6  699.37    95.4  692.82  112.87688.4167   127.3  684.21
     171  676.81   206.8   665.8   218.7  664.27   230.7  664.64  247.61662.5993
   330.1  659.29  361.31659.5452   381.8  658.92   415.7  660.37   421.6  659.96
   429.5  657.92   445.7  659.94   461.4  661.02   481.2  661.18   489.2  662.49
   497.2  664.83     521  673.76   548.8  685.84   576.7  695.92   620.6  718.15
   644.5  729.27   676.4  742.71   716.2  758.26   748.1  769.78     784  781.27
#Mann= 6 ,-1 , 0
       0     .06       0  112.87     .12       0  247.61     .06       0
  361.31     .12       0   415.7    .045       0   445.7     .12       0
Bank Sta=415.7,445.7
XS Rating Curve= 0 ,0
Exp/Cntr=0.3,0.1

Type RM Length L Ch R = 1 ,20817.5 ,235.2,214.3,192.9
XS GIS Cut Line= 5
      2319621.27      406539.552     2319767.103      406642.416
     2319784.812      406706.218     2319945.731      406771.894
     2320076.131      406819.934
#Sta/Elev= 30
       0  700.19   17.71697.6772    27.8   696.1    47.6  690.63    71.4  685.26
    91.2  679.36     119  672.55   130.9  670.22   150.7  667.66   178.5  662.41
   190.2  661.88   204.5662.6362     233  661.81   303.9  661.73   323.7  661.17
     341  659.24   359.2   655.1   367.1  655.88     375  658.33     379  658.89
   386.9  660.13   406.6  664.76   438.3  675.88   458.2  684.45   474.1  692.42
     486  700.85   497.9  707.03   505.8  712.49   533.6  717.82   557.4   723.2
#Mann= 5 ,-1 , 0
       0     .06       0   17.71     .12       0   204.5     .06       0
     341    .045       0     379     .12       0
Bank Sta=341,379
XS Rating Curve= 0 ,0
Exp/Cntr=0.3,0.1

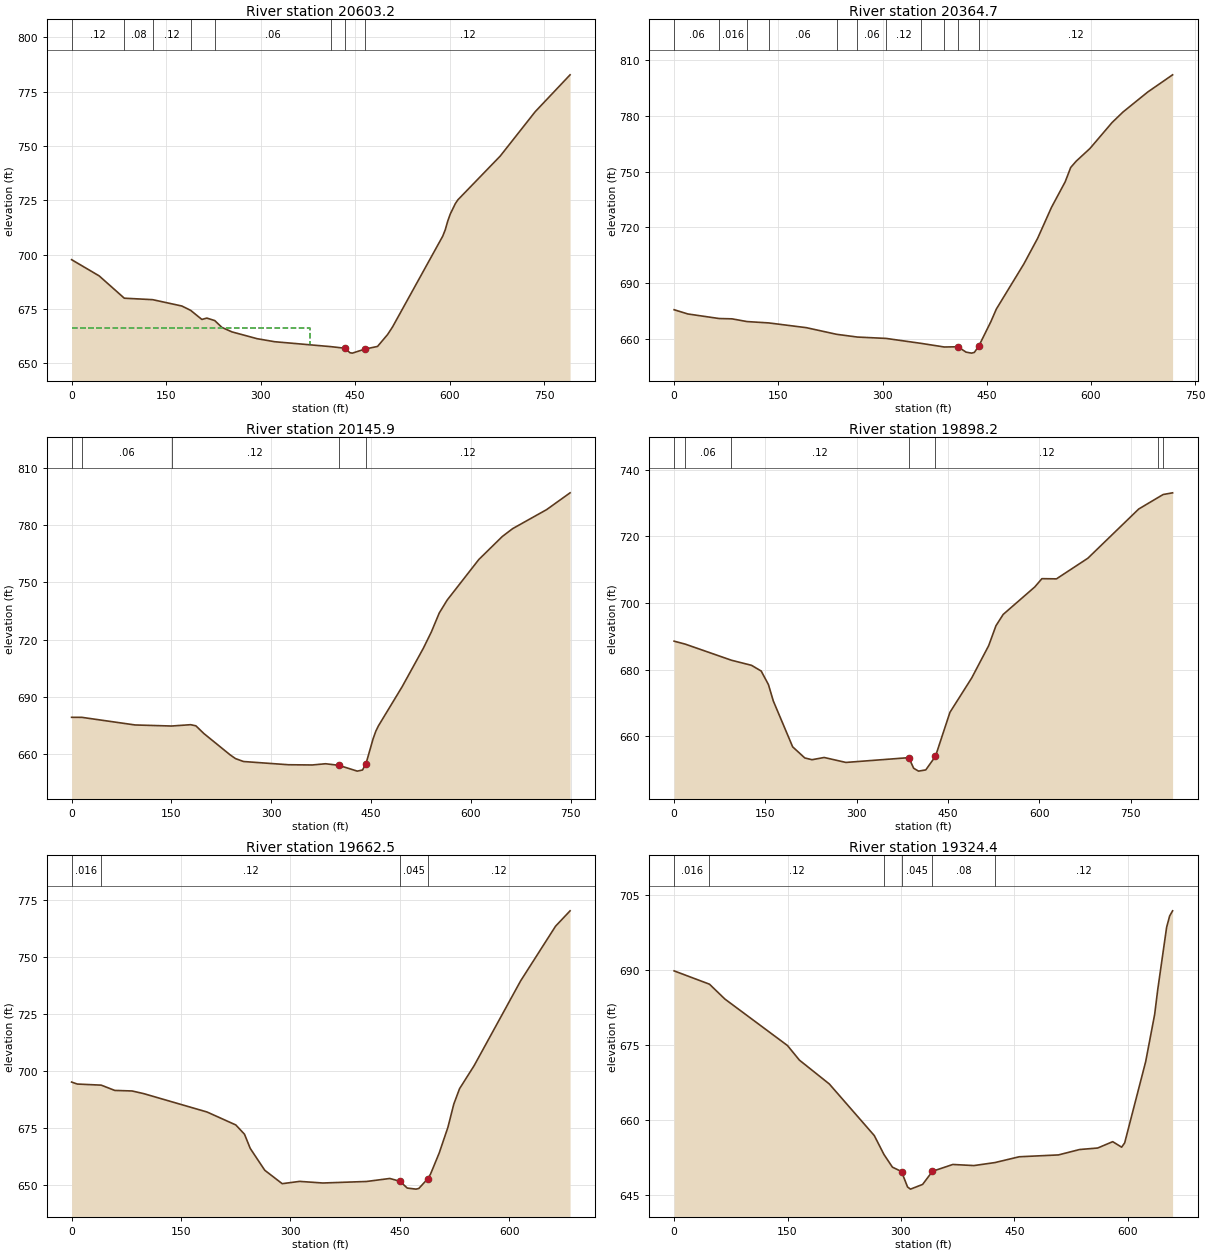
Type RM Length L Ch R = 1 ,20603.2 ,243.2,238.5,233.4
XS GIS Cut Line= 4
     2319475.871      406983.562     2319699.395      407020.454
     2320061.808      406898.927     2320237.589       406946.67
#Sta/Elev= 30
       0  697.62    43.7  690.16   83.65679.8669  128.72679.1868   174.9  676.27
  188.73674.3008   206.7  670.08   214.6   670.7  227.17669.5573   238.5   666.4
   254.4  664.35   294.2  661.22   322.1  659.82  411.37657.5466   433.6  656.81
   441.6  654.75   445.5  654.56   465.5  656.43   485.4  657.64   501.3   663.1
   509.2  666.61   588.9  708.47   592.9  711.43   596.8  715.38   600.8  718.63
   608.8  723.41   612.8  725.16   680.1  745.36   735.5  765.77   790.9  782.78
#Mann= 8 ,-1 , 0
       0     .12       0   83.65     .08       0  128.72     .12       0
  188.73    .016       0  227.17     .06       0  411.37     .12       0
   433.6    .045       0   465.5     .12       0
#XS Ineff= 2 , 0
          378.95  666.33
Permanent Ineff=
       F       F
Bank Sta=433.6,465.5
XS Rating Curve= 0 ,0
Exp/Cntr=0.3,0.1

Type RM Length L Ch R = 1 ,20364.7 ,218,218.8,219.2
XS GIS Cut Line= 3
     2319656.125      407296.357     2319972.832      407181.045
     2320309.204      407003.093
#Sta/Elev= 30
       0  675.71    19.8  673.43   64.85670.9781    83.3  670.81  104.97669.3439
  136.19668.6183   190.3  666.07  233.81662.5023  263.83661.0214  305.23660.2825
  355.85657.6125  388.96 655.675   408.4   655.8   420.3  652.91   428.2  652.38
   432.2  652.78   438.4  656.01     456   669.3   463.9  676.09   503.5  700.33
   523.4  714.17   543.2   730.7     563  744.49   570.9  752.16   578.8  755.56
   598.7  762.41   630.4   776.3   646.2  781.99   681.9  792.76   717.6  801.98
#Mann= 11 ,-1 , 0
       0     .06       0   64.85    .016       0  104.97     .08       0
  136.19     .06       0  233.81     .12       0  263.83     .06       0
  305.23     .12       0  355.85     .06       0  388.96     .12       0
   408.4    .045       0   438.4     .12       0
Bank Sta=408.4,438.4
XS Rating Curve= 0 ,0
Exp/Cntr=0.3,0.1

Type RM Length L Ch R = 1 ,20145.9 ,243.7,247.7,251.7
XS GIS Cut Line= 3
      2319783.47      407515.028     2320320.055      407246.149
     2320367.798       407105.09
#Sta/Elev= 30
       0  679.34   15.45679.3245    95.4  675.34  150.15674.7834   178.9  675.48
   186.8  674.89   198.7  670.88   238.5  659.63   246.4  657.72   258.4  656.21
   325.9  654.52   361.7   654.4   381.6  655.04   401.4  654.24   429.3  651.18
   437.2  651.76  442.48  655.16   453.1   668.1   457.1  672.01   461.1  674.87
   496.8  695.39   528.6  715.48   540.6  723.99   552.5  733.92   564.4  740.69
   611.9   761.9   647.2  773.95   662.9   778.1   713.8  788.02   749.1  796.82
#Mann= 5 ,-1 , 0
       0    .016       0   15.45     .06       0  150.15     .12       0
   401.4    .045       0  442.48     .12       0
Bank Sta=401.4,442.48
XS Rating Curve= 0 ,0
Exp/Cntr=0.3,0.1

Type RM Length L Ch R = 1 ,19898.2 ,233.6,235.7,237.9
XS GIS Cut Line= 3
     2319882.835       407680.55     2320270.042       407547.28
     2320657.249       407414.01
#Sta/Elev= 30
       0  688.54   18.02 687.664   94.28 682.806   127.2  681.28   143.1  679.56
     155  675.49     163  670.56   194.8  656.78   214.7  653.45   226.6  652.92
   246.5  653.59   282.3   652.1   385.6  653.54   393.6  650.35   401.6  649.49
   413.5  649.86   429.4  653.94   453.2  667.16     489   677.5   516.8  687.18
   528.8  693.18   540.7  696.58   592.4   704.8   604.3  707.32   628.2  707.26
   679.8  713.46   763.3  728.24  794.58731.6434  803.52732.6021     819  733.11
#Mann= 7 ,-1 , 0
       0     .12       0   18.02     .06       0   94.28     .12       0
   385.6    .045       0   429.4     .12       0  794.58    .016       0
  803.52     .12       0
Bank Sta=385.6,429.4
XS Rating Curve= 0 ,0
Exp/Cntr=0.3,0.1

Type RM Length L Ch R = 1 ,19662.5 ,324.2,338,316.1
XS GIS Cut Line= 3
     2319882.313      407806.622     2320122.046      407830.256
     2320549.614      407716.685
#Sta/Elev= 30
       0  695.19     7.9  694.32   40.63693.8381    59.2  691.52    82.9  691.28
    98.7  690.13   185.6  682.05   225.1  676.36     237  672.29   244.9  666.04
   264.8  656.46   288.7  650.56   312.6  651.57   344.5  650.86   404.3  651.53
   436.2  652.85     450  651.63   460.1  648.64   472.1  648.17     476  648.47
     488  652.65     492  654.76   503.9  664.03   515.9  675.38   523.9  685.51
   531.8  692.28   551.8  702.41   615.5  739.62   663.4  763.65   683.3   770.4
#Mann= 4 ,-1 , 0
       0    .016       0   40.63     .12       0     450    .045       0
     488     .12       0
Bank Sta=450,488
XS Rating Curve= 0 ,0
Exp/Cntr=0.3,0.1

Type RM Length L Ch R = 1 ,19324.4 ,319,340.1,333.9
XS GIS Cut Line= 4
      2319940.28       407886.34     2320138.848      408015.463
     2320454.603      408064.291     2320516.452      407981.826
#Sta/Elev= 30
       0  689.75    46.8 687.091    67.1  684.13     150  674.82   165.8   671.9
   205.3  667.14   264.8  656.82  277.59653.0411   288.8   650.5   300.8  649.63
   308.8  646.54   312.7  646.11   328.7  647.05   341.8  649.68   368.7  651.04
   396.6  650.82   424.3651.4177   456.5  652.58   508.4  652.95   536.4  654.03
   560.3  654.33   580.2   655.6     592   654.5     596  655.35   623.8  671.61
   635.7  681.06   639.6  685.84   651.5  698.47   655.5  700.73   659.4  701.76
#Mann= 6 ,-1 , 0
       0    .016       0    46.8     .12       0  277.59     .08       0
   300.8    .045       0   341.8     .08       0   424.3     .12       0
Bank Sta=300.8,341.8
XS Rating Curve= 0 ,0
Exp/Cntr=0.3,0.1

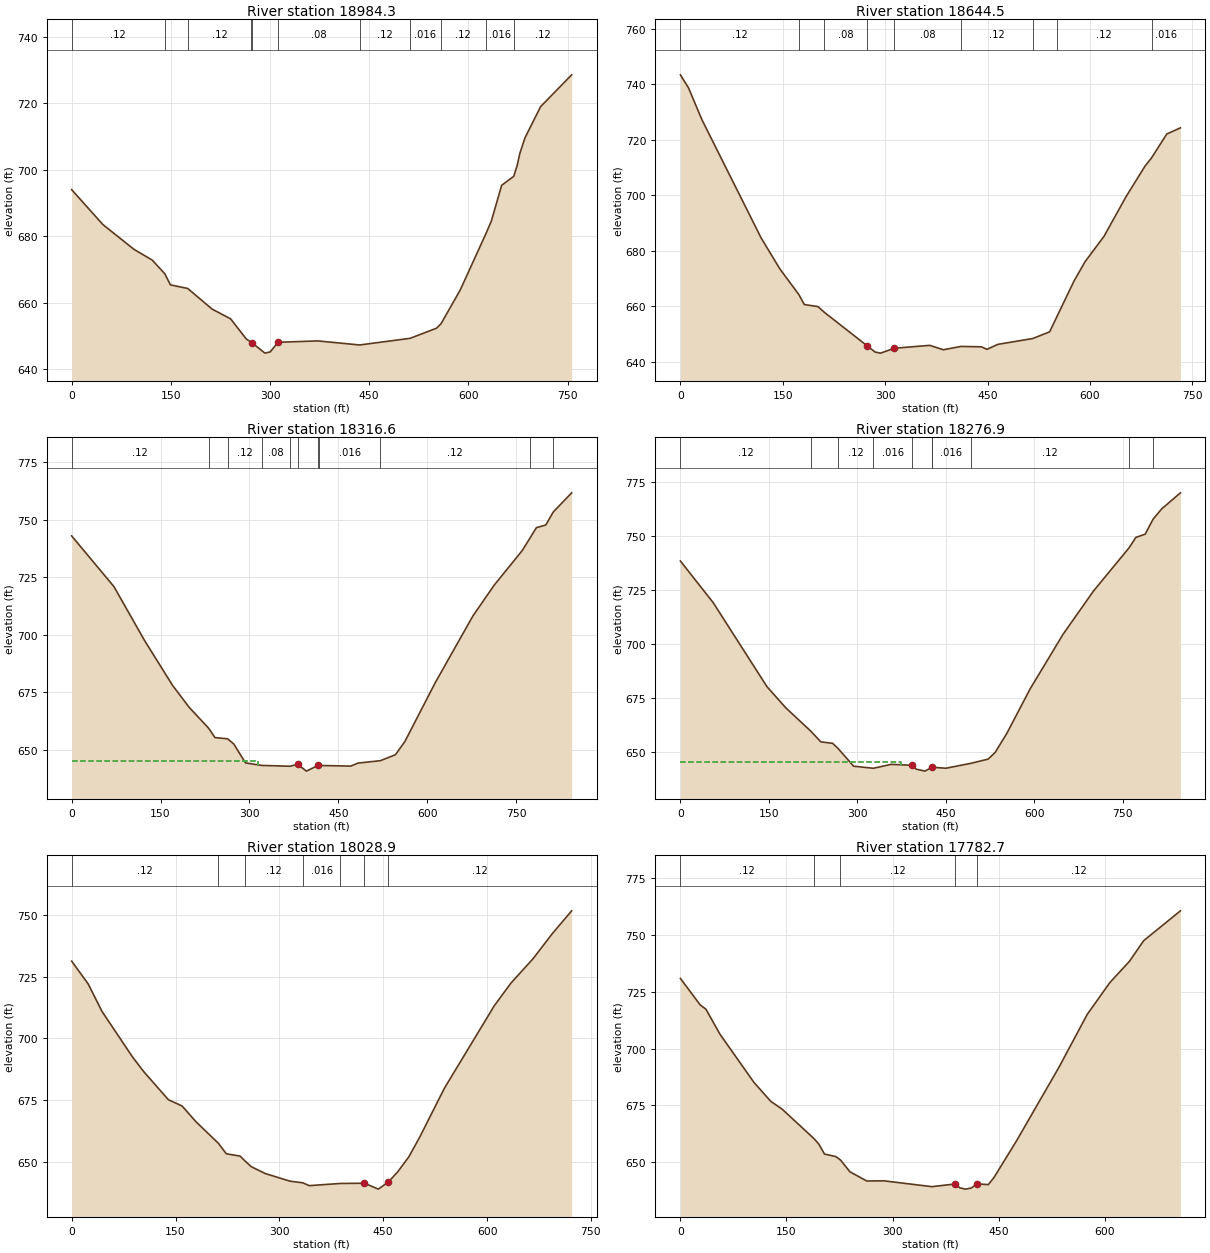
Type RM Length L Ch R = 1 ,18984.3 ,346.1,339.8,329
XS GIS Cut Line= 4
     2319879.516      408276.965     2320083.509      408263.944
     2320458.937      408267.811     2320629.299      408313.857
#Sta/Elev= 30
       0     694    47.2   683.5    94.3  676.03   121.9   672.8  140.85668.6883
   149.4  665.35  175.53664.2624   212.4  658.06   240.4  655.12   264.3  649.02
  271.63648.0654   272.3  647.99   292.3   644.8   300.3  645.17   312.2  648.06
   372.2  648.48  435.47647.2543  511.83649.2498   551.9   652.3  558.58653.6034
   587.7  663.78  626.35680.6321   634.8  684.53   650.4  695.31  668.69698.0201
     674  701.37   677.9   704.9   685.7   709.6   709.3  718.98   756.3  728.56
#Mann= 11 ,-1 , 0
       0     .12       0  140.85    .016       0  175.53     .12       0
  271.63     .08       0   272.3    .045       0   312.2     .08       0
  435.47     .12       0  511.83    .016       0  558.58     .12       0
  626.35    .016       0  668.69     .12       0
Bank Sta=272.3,312.2
XS Rating Curve= 0 ,0
Exp/Cntr=0.3,0.1

Type RM Length L Ch R = 1 ,18644.5 ,341.8,327.8,304.9
XS GIS Cut Line= 3
     2319918.401      408660.161      2320047.02      408591.928
     2320614.286      408441.729
#Sta/Elev= 30
       0  743.41    11.8  738.74    31.5  727.23     118  684.69   145.6  673.44
  173.36664.2078   181.5  660.57   201.5  659.82     211657.7263   273.3  645.72
   285.3  643.42   293.3  643.04   313.3   644.8   365.2  645.84   385.1  644.26
  410.94 645.454     441  645.31     449   644.4     465   646.2  516.03648.3052
   540.8  650.71  551.91656.4094   576.7  669.11   592.7     676   620.6  685.21
   652.6   699.4   680.5  710.47  690.06713.4314   712.4  722.06   732.4  724.29
#Mann= 9 ,-1 , 0
       0     .12       0  173.36    .016       0     211     .08       0
   273.3    .045       0   313.3     .08       0  410.94     .12       0
  516.03    .016       0  551.91     .12       0  690.06    .016       0
Bank Sta=273.3,313.3
XS Rating Curve= 0 ,0
Exp/Cntr=0.3,0.1

Type RM Length L Ch R = 1 ,18316.6 ,43.1,39.8,38.7
XS GIS Cut Line= 4
     2320013.545      408941.718     2320350.914       408765.34
     2320372.442      408743.118     2320761.461      408555.003
#Sta/Elev= 30
       0  742.93    71.4  720.91   122.9  697.58   170.5  677.98   198.3  668.53
   231.1659.4872   241.9  655.39  263.16 654.874   273.6  652.61   293.4  644.41
  320.75643.3201  368.21642.9564   381.5  643.77   396.2  640.84   415.6  643.29
  417.89643.2957   471.1  643.02     483  644.32  521.01645.3696   546.4  647.96
   562.3  653.68   613.8  679.33   677.2  708.21   712.9   721.5   760.5  736.62
  772.72741.6836   784.3  746.51   800.1  747.66   812.7753.2922   843.8  761.63
#Mann= 11 ,-1 , 0
       0     .12       0   231.1    .016       0  263.16     .12       0
  320.75     .08       0  368.21     .12       0   381.5    .045       0
   415.6     .12       0  417.89    .016       0  521.01     .12       0
  772.72    .016       0   812.7     .12       0
#XS Ineff= 2 , 0
          314.76  645.44
Permanent Ineff=
       F       F
Bank Sta=381.5,415.6
XS Rating Curve= 0 ,0
Exp/Cntr=0.3,0.1

Type RM Length L Ch R = 1 ,18276.9 ,238.2,247.9,248.3
XS GIS Cut Line= 4
     2320056.601      408981.996     2320388.414      408786.868
     2320407.858      408759.785     2320804.516      408595.281
#Sta/Elev= 30
       0  738.44    55.6  719.17   146.8  680.29   178.6  670.54   220.9659.7667
   238.1  654.77     258   654.1  266.78651.8834   293.7   643.5  327.27642.5547
   357.2  644.36   392.3  643.95   399.8  642.15   414.6  641.23   426.2  643.01
  426.54643.0397   450.1  642.57  492.28644.8268   521.6  646.78   533.6  649.86
   553.5  658.75   593.2  679.41   648.9  704.61   700.6  724.66  760.76744.5818
   772.2  749.37     788  750.87  801.34757.7793   815.9  762.54   847.7  769.99
#Mann= 10 ,-1 , 0
       0     .12       0   220.9    .016       0  266.78     .12       0
  327.27    .016       0   392.3    .045       0   426.2     .12       0
  426.54    .016       0  492.28     .12       0  760.76    .016       0
  801.34     .12       0
#XS Ineff= 2 , 0
          374.61  645.68
Permanent Ineff=
       F       F
Bank Sta=392.3,426.2
XS Rating Curve= 0 ,0
Exp/Cntr=0.3,0.1

Type RM Length L Ch R = 1 ,18028.9 ,238.2,246.3,247.2
XS GIS Cut Line= 2
     2320172.432      409133.423     2320819.056      408811.868
#Sta/Elev= 30
       0   731.3    23.9  722.05    43.9  710.92    87.8  692.56   103.7  686.72
   139.6  675.25   159.6  672.67   179.5  666.33  211.95657.5992   223.4  653.35
   243.4  652.41  250.41650.4415   259.3  648.16   279.3  645.39   315.2  642.28
  333.83641.6039   343.1  640.46  388.07 641.338   422.9  641.44   442.9  639.05
   457.2  641.87   470.8     646   486.8  652.02   502.7  660.07   538.6  679.98
   610.4  713.22   634.4  722.38   666.3  732.23   694.2  742.41   722.2  751.65
#Mann= 7 ,-1 , 0
       0     .12       0  211.95    .016       0  250.41     .12       0
  333.83    .016       0  388.07     .12       0   422.9    .045       0
   457.2     .12       0
Bank Sta=422.9,457.2
XS Rating Curve= 0 ,0
Exp/Cntr=0.3,0.1

Type RM Length L Ch R = 1 ,17782.7 ,257.8,273.7,267.3
XS GIS Cut Line= 2
     2320266.756      409293.639     2320923.223      409031.052
#Sta/Elev= 30
       0  730.91      28  719.23      36  717.38    55.9  706.34   103.9   685.1
   127.8  676.71   143.8  673.29  188.46660.4078   195.7  657.88   203.7  653.48
   219.7  652.37  226.34650.8652   239.7  645.64   263.6  641.59   287.6  641.67
   355.5   639.1   387.7  640.24   395.5  638.54   403.4  638.01   411.4  638.51
   419.4  640.33   435.4     640   443.4  643.14   475.4  659.37   535.3  691.76
   575.2  715.03   607.2  729.07   635.1  738.53   655.1  747.57     707  760.72
#Mann= 5 ,-1 , 0
       0     .12       0  188.46    .016       0  226.34     .12       0
   387.7    .045       0   419.4     .12       0
Bank Sta=387.7,419.4
XS Rating Curve= 0 ,0
Exp/Cntr=0.3,0.1

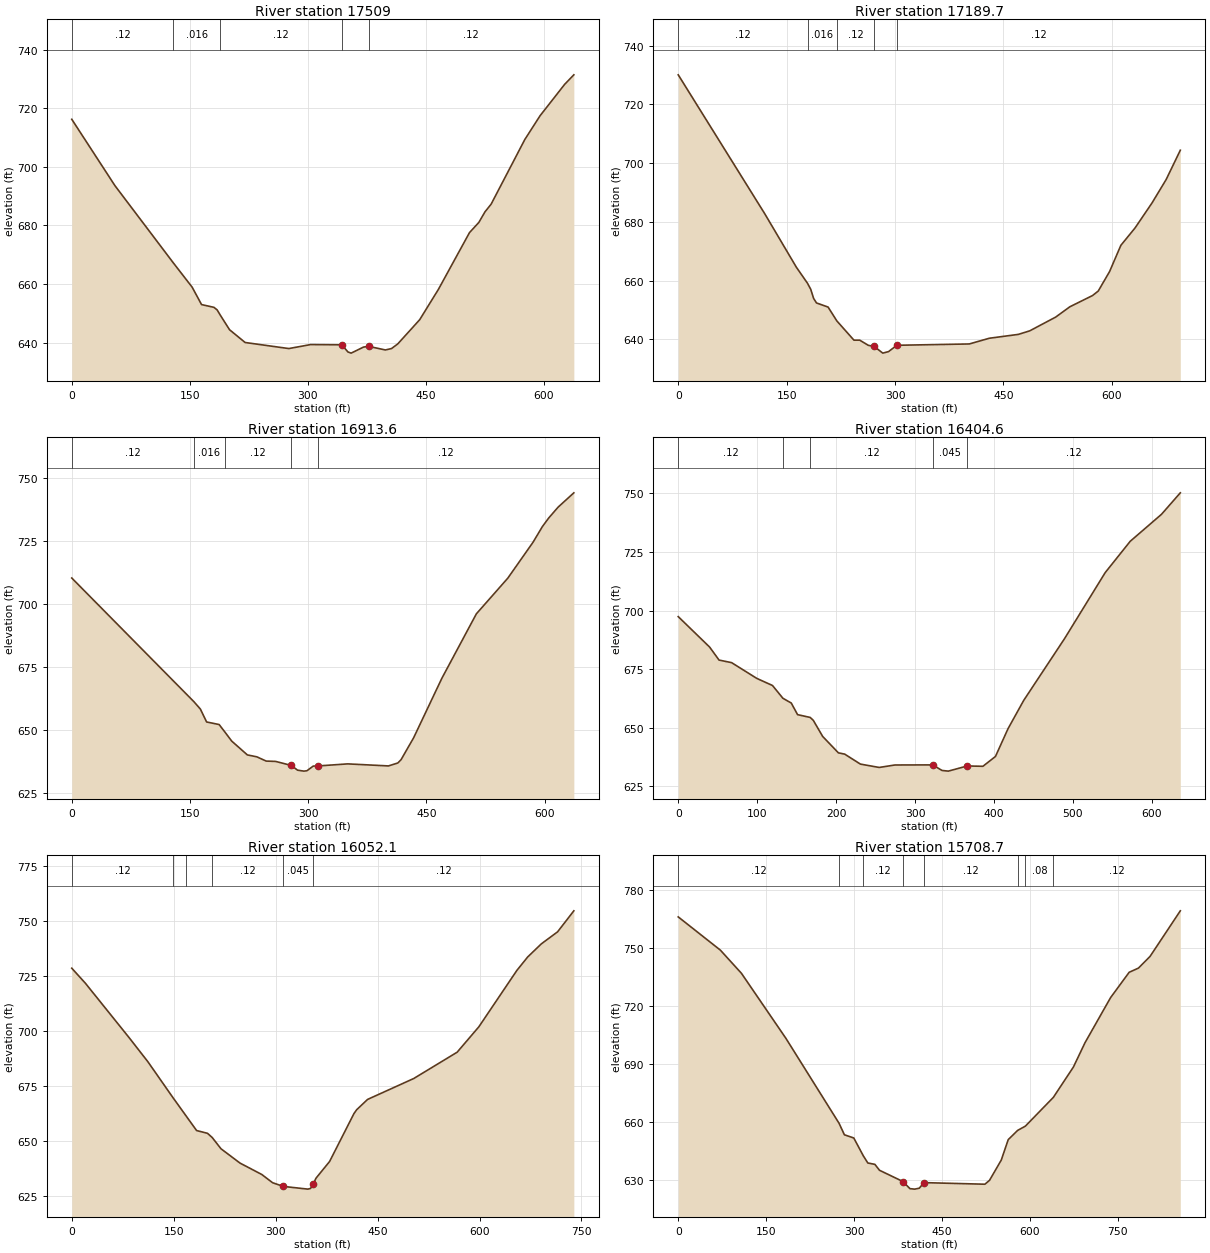
Type RM Length L Ch R = 1 ,17509   ,314.2,319.3,293.7
XS GIS Cut Line= 4
     2320365.497      409426.017     2320518.492      409427.102
     2320856.734      409291.805     2320918.883      409188.387
#Sta/Elev= 30
       0  716.24    54.9  693.56  128.69667.3375     153   658.9   164.9  652.97
   180.7  652.02   184.7  651.16   188.7649.3777   200.5  644.38   220.3  640.02
   275.8  637.95   303.5  639.31   343.1  639.23     351  636.78     355  636.39
   370.8  638.46   377.2  638.71   398.5  637.47   406.4  637.96   414.3  639.55
   442.1   647.8   465.8  658.11   505.4  677.54   517.3  681.03   525.1  684.64
   532.9  687.26   575.7  709.33   595.1  717.46   626.3  728.16     638  731.42
#Mann= 5 ,-1 , 0
       0     .12       0  128.69    .016       0   188.7     .12       0
   343.1    .045       0   377.2     .12       0
Bank Sta=343.1,377.2
XS Rating Curve= 0 ,0
Exp/Cntr=0.3,0.1

Type RM Length L Ch R = 1 ,17189.7 ,274.9,276.1,291.5
XS GIS Cut Line= 3
     2320401.305      409641.946     2320896.096      409450.974
     2321037.155      409535.609
#Sta/Elev= 30
       0  730.04   119.6  682.83   163.5  664.58  178.96659.1013   183.4  657.06
   187.4  653.95   191.4  652.42   207.4  651.02   219.6 646.286   243.2  639.76
   251.2  639.76   263.2  637.99   271.2  637.63   283.1  635.35   291.1  635.87
   302.6  638.02   402.8  638.47   430.7  640.42   470.6  641.72   486.5  642.93
   522.4  647.61   542.1  651.13   573.4  654.94   581.3  656.47     597   663.1
   612.6  672.02   632.2  677.92   655.7  686.43   675.3  694.41   694.9  704.38
#Mann= 5 ,-1 , 0
       0     .12       0  178.96    .016       0   219.6     .12       0
   271.2    .045       0   302.6     .12       0
Bank Sta=271.2,302.6
XS Rating Curve= 0 ,0
Exp/Cntr=0.3,0.1

Type RM Length L Ch R = 1 ,16913.6 ,475.3,509,518.1
XS GIS Cut Line= 3
     2320530.428      409877.406     2320998.093      409675.583
     2321123.961      409697.285
#Sta/Elev= 30
       0  710.27  154.94 661.271   163.2  658.34   171.1  653.22     187   652.2
  194.21649.2769     203  645.63   222.8  640.17   234.8  639.41   246.7  637.72
   258.7  637.59   278.6  635.99   286.5  634.12   294.5  633.74   298.4  633.89
   306.4  635.73   312.3  635.79   350.2  636.61   401.9   635.8   413.8  636.98
   417.8  638.25   433.8  646.95   469.6  670.52   513.4  696.07   553.3  710.21
   585.2  724.39   597.2  730.65   605.2  734.05   617.1  738.34   637.1  744.03
#Mann= 5 ,-1 , 0
       0     .12       0  154.94    .016       0  194.21     .12       0
   278.6    .045       0   312.3     .12       0
Bank Sta=278.6,312.3
XS Rating Curve= 0 ,0
Exp/Cntr=0.3,0.1

Type RM Length L Ch R = 1 ,16404.6 ,343.9,352.6,341.9
XS GIS Cut Line= 3
     2320602.042      410082.484     2321075.133      410102.015
     2321234.638      410070.548
#Sta/Elev= 30
       0  697.46    39.8  684.46    51.7  678.92    67.6  677.83    99.5  671.11
   119.4  668.08  132.64662.6193   143.2  660.59   151.2  655.64  167.16654.4512
   171.1  653.22     183  646.34   202.9  639.34   210.9  638.79   230.8  634.54
   254.6  633.11   274.6  634.16   322.3   634.2   334.2  631.83   342.2  631.54
   366.1  633.74     386   633.6   401.9  637.79   417.8  649.62   437.7  661.72
   489.4  688.05   540.9  716.22   572.6  729.59   612.3  741.13   636.1  750.28
#Mann= 5 ,-1 , 0
       0     .12       0  132.64    .016       0  167.16     .12       0
   322.3    .045       0   366.1     .12       0
Bank Sta=322.3,366.1
XS Rating Curve= 0 ,0
Exp/Cntr=0.3,0.1

Type RM Length L Ch R = 1 ,16052.1 ,355.4,343.3,330.6
XS GIS Cut Line= 2
     2320592.277      410438.387     2321289.976      410195.331
#Sta/Elev= 30
       0  728.42      20  721.61    83.9  697.08   111.8  686.04  149.45669.4164
  168.72661.1371   183.7  654.71   199.7  653.46  206.64651.5475   219.6  646.43
   247.6  639.93   279.6  634.76   295.5  631.02   311.5  629.34   347.4  628.11
   351.4  628.43   355.4  630.52   359.4  633.08   379.4  640.66   415.3  662.45
   419.3  664.18   435.3  668.84   503.2  678.33   567.1  690.28     599   701.8
     655  727.43   670.9  733.52   690.9  739.45   714.9  744.94   738.8  754.47
#Mann= 6 ,-1 , 0
       0     .12       0  149.45     .06       0  168.72    .016       0
  206.64     .12       0   311.5    .045       0   355.4     .12       0
Bank Sta=311.5,355.4
XS Rating Curve= 0 ,0
Exp/Cntr=0.3,0.1

Type RM Length L Ch R = 1 ,15708.7 ,324.8,332.3,337.9
XS GIS Cut Line= 3
     2320729.814      410881.822     2321157.598      410515.427
      2321416.93      410377.623
#Sta/Elev= 30
       0  766.09    71.9  748.91   107.9  736.92   183.8  703.29  274.51659.3831
   283.6  653.44   299.6  651.79  316.06642.4774   323.6  638.86   335.6  638.16
   343.5   635.1   383.5  629.28   395.5  625.59   403.5  625.35   411.4  625.83
   419.4  628.71   523.3  627.89   531.3   629.9   551.3  640.36   563.2  650.94
  579.31655.7152  592.46657.9152  640.21672.7797   674.4  688.45   694.2  701.02
   737.9  724.36   769.6  737.45   785.5  739.63   805.3  745.68   856.9  769.23
#Mann= 8 ,-1 , 0
       0     .12       0  274.51    .016       0  316.06     .12       0
   383.5    .045       0   419.4     .12       0  579.31     .06       0
  592.46     .08       0  640.21     .12       0
Bank Sta=383.5,419.4
XS Rating Curve= 0 ,0
Exp/Cntr=0.3,0.1