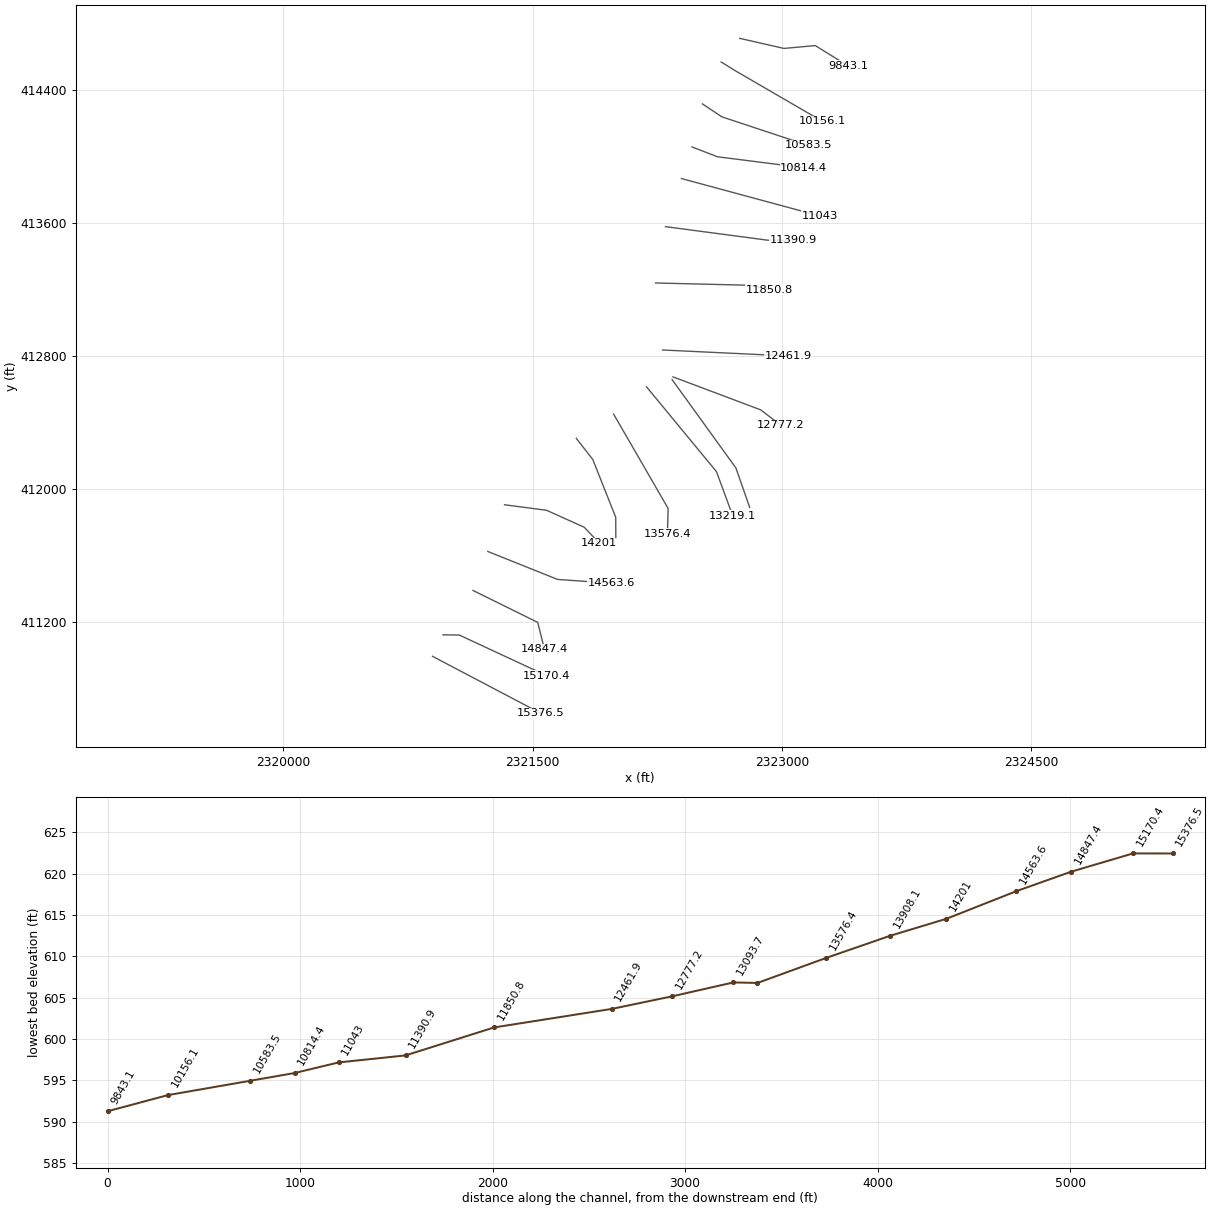
HEC-RAS study SIRJOHNSRN.prj: SIRJOHNSRN

--- SIRJOHNSRN.g01 (geometry) --- (continued)

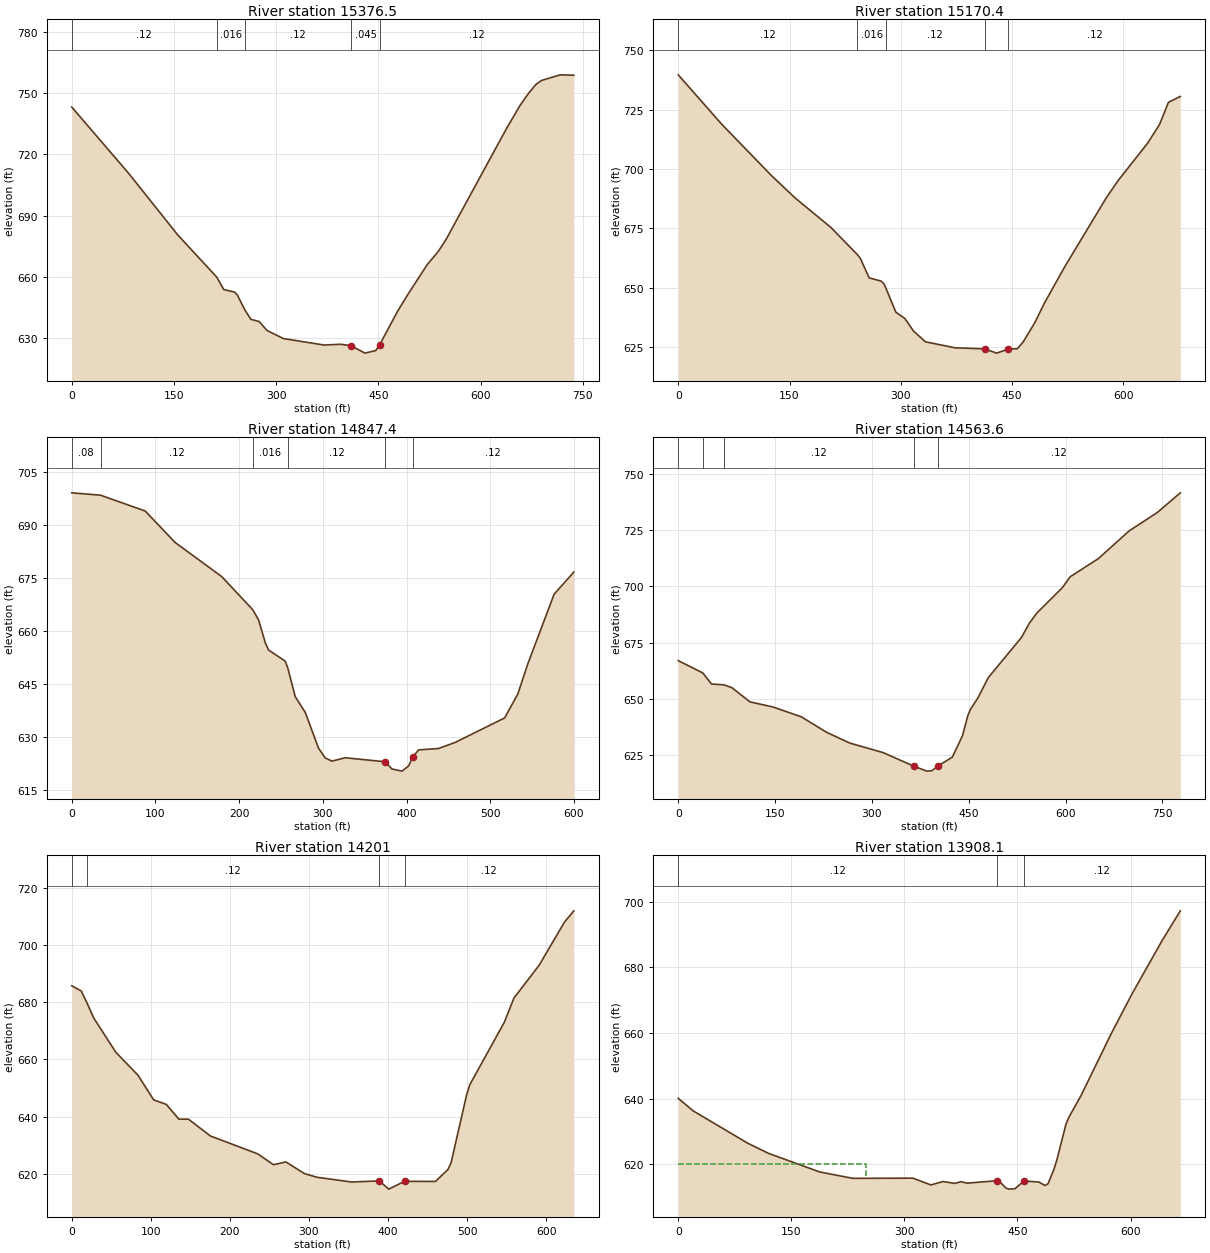
Type RM Length L Ch R = 1 ,15376.5 ,204.6,206.1,207.7
XS GIS Cut Line= 2
      2320896.92      410996.106     2321549.308      410653.231
#Sta/Elev= 30
       0  743.24    83.7  710.62   155.4  680.54  212.83659.7363   223.1  653.66
     239  652.39     243  651.04  253.93 643.722   262.9  639.03   274.9  637.97
   286.8  633.52   310.7  629.58   370.5   626.4   394.4  626.78   410.3  626.06
   430.2  622.43   446.2   623.7   452.1  626.61   478.1   642.9     494  651.58
   521.9  665.95   537.8  672.26   549.8  678.45   637.4  732.22   657.3  743.66
   669.3  749.47   681.2  754.31   689.2  756.26   717.1  759.07     737  758.88
#Mann= 5 ,-1 , 0
       0     .12       0  212.83    .016       0  253.93     .12       0
   410.3    .045       0   452.1     .12       0
Bank Sta=410.3,452.1
XS Rating Curve= 0 ,0
Exp/Cntr=0.3,0.1

Type RM Length L Ch R = 1 ,15170.4 ,321.8,323.1,319.4
XS GIS Cut Line= 3
      2320960.21      411125.221     2321057.772      411124.151
     2321582.945       410880.01
#Sta/Elev= 30
       0  739.73    58.5  718.95   125.5  697.31   157.5  687.84   205.4  675.51
  241.15664.0619   245.4  662.43   257.3  654.14   273.3  652.82   277.3  651.64
  279.91649.8065   293.3  639.69   305.3  637.08   317.2  631.73   333.2  627.21
   373.2  624.68   413.1  624.23   429.1  622.44   445.1  624.18     457  624.26
     465   627.2     481   635.5     493   643.2   520.9  658.83   576.9  687.88
   592.8  695.13   632.8     711   648.8  718.87   660.7  728.13   676.7  730.62
#Mann= 5 ,-1 , 0
       0     .12       0  241.15    .016       0  279.91     .12       0
   413.1    .045       0   445.1     .12       0
Bank Sta=413.1,445.1
XS Rating Curve= 0 ,0
Exp/Cntr=0.3,0.1

Type RM Length L Ch R = 1 ,14847.4 ,281.1,283.8,285.8
XS GIS Cut Line= 3
     2321140.237      411392.163     2321529.777      411200.106
     2321569.924      411039.515
#Sta/Elev= 30
       0  699.09   34.39698.4168    87.7  693.94   123.5  685.02   179.3  675.32
  216.27665.9443   223.1  663.12   231.1  656.66   235.1  654.54     255  651.39
  258.12 649.401     267  641.31   278.9  636.88   294.8  626.72   302.8  623.95
   310.8  623.06   326.7  624.01   374.5  622.87   382.5  620.83   394.5  620.22
   402.4   621.7   407.4  624.26   414.4  626.24   438.2  626.63     458  628.35
   517.1  635.29   532.8  642.03   544.7  650.54   576.2  670.35   599.8  676.63
#Mann= 6 ,-1 , 0
       0     .08       0   34.39     .12       0  216.27    .016       0
  258.12     .12       0   374.5    .045       0   407.4     .12       0
Bank Sta=374.5,407.4
XS Rating Curve= 0 ,0
Exp/Cntr=0.3,0.1

Type RM Length L Ch R = 1 ,14563.6 ,362.2,362.5,360.6
XS GIS Cut Line= 3
     2321229.213      411626.538     2321649.134      411458.352
      2321973.57      411435.566
#Sta/Elev= 30
       0  666.97   37.89661.5308    51.6  656.59   70.91656.2025    83.3  654.93
   111.1  648.64   146.8  646.36   190.5  642.02   230.1  635.07   265.9  630.32
   317.4   626.1     365  620.06   384.9  617.87   392.8  618.04   402.4  620.16
   424.6  624.13   440.4  633.71   448.4  642.41   452.4  645.23   464.2  650.43
   480.1  659.37   531.7  677.31   543.6  683.51   555.5  688.13   595.1  699.44
     607  704.22   650.7  712.29   698.3   724.6   741.9  732.77   777.6  741.52
#Mann= 5 ,-1 , 0
       0     .12       0   37.89    .016       0   70.91     .12       0
     365    .045       0   402.4     .12       0
Bank Sta=365,402.4
XS Rating Curve= 0 ,0
Exp/Cntr=0.3,0.1

Type RM Length L Ch R = 1 ,14201   ,314.9,293,268.6
XS GIS Cut Line= 4
     2321330.053      411907.247     2321582.945      411873.934
     2321809.357      411772.176     2321899.785      411676.451
#Sta/Elev= 30
       0  685.83      12  684.01   19.58679.6236    27.9  674.49    55.8  662.49
    83.7  654.51   103.6  645.83   119.6  644.25   135.5  639.06   147.5  639.07
   175.4  633.17   235.2  626.91   255.1   623.1   270.8  624.08   294.5  619.96
   310.2   618.7   353.6  617.04     389  617.41   400.9  614.54   420.9  617.27
     460  617.24   475.7   621.4   479.7  623.74   499.4   647.6   503.3  651.09
   547.2  673.13   559.2  681.52   591.1  693.04     623  708.11     635  712.12
#Mann= 4 ,-1 , 0
       0    .016       0   19.58     .12       0     389    .045       0
   420.9     .12       0
Bank Sta=389,420.9
XS Rating Curve= 0 ,0
Exp/Cntr=0.3,0.1

Type RM Length L Ch R = 1 ,13908.1 ,327.7,331.7,335.6
XS GIS Cut Line= 4
      2321761.96      412305.699     2321860.723      412179.923
     2321998.984      411832.006     2321999.612      411700.323
#Sta/Elev= 30
       0  640.13      20  636.28      92  626.49   119.9  623.35   187.8   617.7
   231.6  615.76   311.3  615.82   335.2  613.75   351.1   614.8     367  614.22
     375  614.75     383   614.3   422.8  615.03   426.8  614.69   434.7  612.78
   438.7  612.48   446.7   612.6   458.6  614.97   478.5  614.63   486.5  613.58
   490.5   614.1   498.4  618.52   502.4   621.5   514.4  632.32   518.4  634.45
   534.3  640.96   574.2  659.74   602.1  671.98     642   688.2     666   697.2
#Mann= 3 ,-1 , 0
       0     .12       0   422.8    .045       0   458.6     .12       0
#XS Ineff= 2 , 0
          248.91  620.15
Permanent Ineff=
       F       F
Bank Sta=422.8,458.6
XS Rating Curve= 0 ,0
Exp/Cntr=0.3,0.1

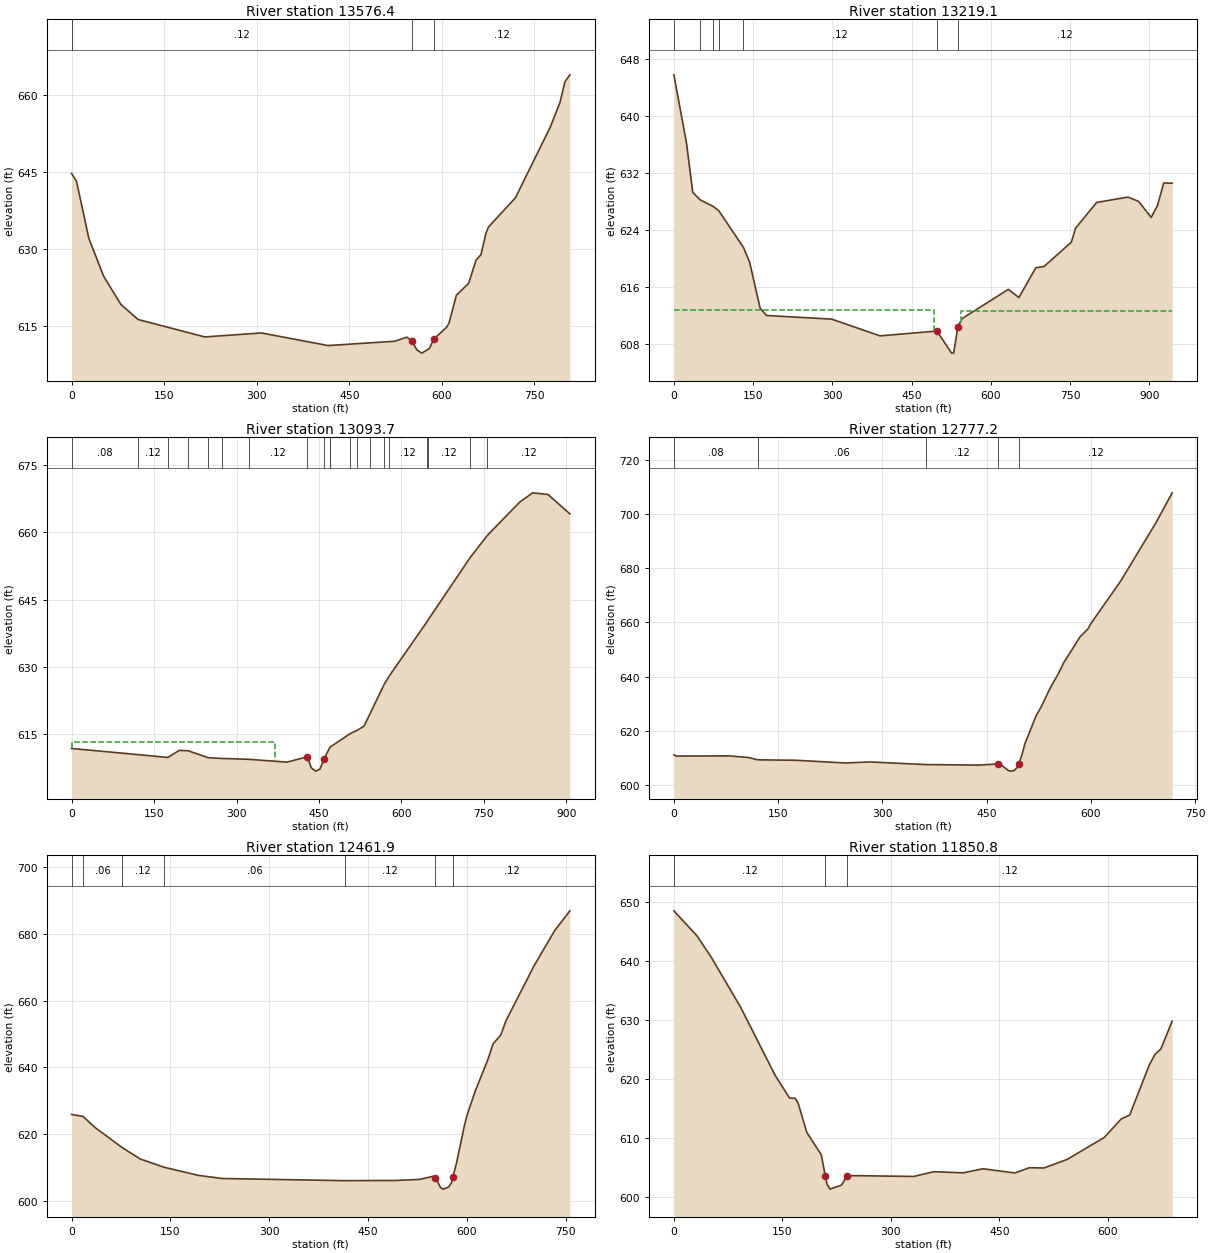
Type RM Length L Ch R = 1 ,13576.4 ,352.8,357.2,362.3
XS GIS Cut Line= 3
     2321986.183       412452.19     2322314.282      411884.785
     2322309.942      411732.875
#Sta/Elev= 30
       0  644.71     .26644.6801       8  643.22      28   632.1      52  624.75
    79.9  619.28   107.9  616.34   215.8  612.96   307.7  613.73   415.6  611.28
   523.6  612.12   543.5  612.92   551.5  612.15   559.5  610.44   567.5  609.81
   579.5  610.69   587.5  612.61   607.5  614.82   611.5  615.62   623.5  621.07
   643.4  623.38   655.4  627.89   663.4  628.96   671.4  633.11   675.4  634.31
   719.4  640.05   775.4  653.69   791.4  658.54   799.4  662.56   807.4  663.91
#Mann= 4 ,-1 , 0
       0    .016       0     .26     .12       0   551.5    .045       0
   587.5     .12       0
Bank Sta=551.5,587.5
XS Rating Curve= 0 ,0
Exp/Cntr=0.3,0.1

Type RM Length L Ch R = 1 ,13219.1 ,125.9,125.4,123.1
XS GIS Cut Line= 3
     2322184.074      412616.121     2322605.081      412106.139
     2322702.737      411841.382
#Sta/Elev= 30
       0  645.83    23.9  636.26    35.8  629.34   49.78 628.285   74.21627.3782
   84.98 626.762  131.81621.6039   143.4  619.55   163.3  613.09   175.3  612.06
   298.8  611.55   390.4   609.2     498  609.88   525.9  606.78   529.8  606.81
   537.8   610.5   545.8  611.63   633.4  615.73   653.3  614.58   685.2  618.75
     701  618.94   752.7  622.36   760.7  624.32   800.4  627.92     860  628.68
   879.9  628.07   903.8  625.82   915.7   627.5   927.6  630.66   943.5  630.62
#Mann= 7 ,-1 , 0
       0     .12       0   49.78     .08       0   74.21     .12       0
   84.98    .016       0  131.81     .12       0     498    .045       0
   537.8     .12       0
#XS Ineff= 2 , 0
          493.29  612.84  542.83          612.67
Permanent Ineff=
       F       F
Bank Sta=498,537.8
XS Rating Curve= 0 ,0
Exp/Cntr=0.3,0.1

Type RM Length L Ch R = 1 ,13093.7 ,297.3,316.5,332.1
XS GIS Cut Line= 3
     2322338.154      412659.524     2322722.268       412127.84
     2322804.733      411891.295
#Sta/Elev= 30
       0  611.88  121.18610.5082  174.99609.8799     196  611.46  211.85611.3782
  248.72609.8272  273.28609.6612  322.55609.4664     392  608.84   428.9  610.04
     436  607.57     444  606.84     452   607.3   458.9   609.5   469.9  612.13
  470.36612.1944  506.77615.1774  519.64615.9363   531.9  616.84  543.63619.7909
  568.91626.2121  577.88628.0009  646.26640.0325   648.8640.5245   725.1 654.358
  756.43659.2969     815  666.66   838.8  668.75   866.7  668.38   906.4  664.06
#Mann= 20 ,-1 , 0
       0     .08       0  121.18     .12       0  174.99     .08       0
  211.85     .12       0  248.72     .08       0  273.28     .06       0
  322.55     .12       0   428.9    .045       0   458.9     .12       0
   469.9     .08       0  470.36     .06       0  506.77     .08       0
  519.64     .06       0  543.63     .08       0  568.91     .06       0
  577.88     .12       0  646.26     .06       0   648.8     .12       0
   725.1     .06       0  756.43     .12       0
#XS Ineff= 2 , 0
          369.45  613.24
Permanent Ineff=
       F       F
Bank Sta=428.9,458.9
XS Rating Curve= 0 ,0
Exp/Cntr=0.3,0.1

Type RM Length L Ch R = 1 ,12777.2 ,304.9,315.3,325.4
XS GIS Cut Line= 3
     2322343.362      412676.017     2322872.008      412477.232
     2322992.667       412384.35
#Sta/Elev= 30
       0  611.14       4  610.72    79.6  610.79   107.4  610.19  120.79609.3363
     175  609.18   246.6  608.18   282.4  608.55  363.29607.5887   437.5  607.39
   466.2  607.81   469.3  607.81   481.3  605.41   485.2  605.17   489.2  605.36
   493.2  606.22   496.2  607.81   501.2  611.48   505.1  615.25     521  625.46
     529  629.08   540.9  635.51   552.8  640.91   560.8  645.07   584.3  654.64
     596  657.64   599.9  659.53   642.9  675.24   693.6  696.74     717  707.79
#Mann= 5 ,-1 , 0
       0     .08       0  120.79     .06       0  363.29     .12       0
   466.2    .045       0   496.2     .12       0
Bank Sta=466.2,496.2
XS Rating Curve= 0 ,0
Exp/Cntr=0.3,0.1

Type RM Length L Ch R = 1 ,12461.9 ,608.6,611.1,613.4
XS GIS Cut Line= 3
     2322280.862      412837.475     2322904.126      412807.962
      2323036.07      412802.753
#Sta/Elev= 30
       0  625.95   17.36625.3638      36  621.98   76.42616.1158     104  612.66
  140.76610.1496     192  607.77     228  606.82  414.24 606.168     492  606.24
     528  606.55     548  607.45     552   607.1     560  604.04     564  603.64
     572  604.26     576  605.43  578.95  607.16     579  607.65     584  611.41
     596  622.62     600  625.72     612  632.71   631.7  642.42   639.5  647.04
   651.2  649.69   658.9  653.89   701.6  670.34   732.7  680.82     756   686.8
#Mann= 7 ,-1 , 0
       0     .08       0   17.36     .06       0   76.42     .12       0
  140.76     .06       0  414.24     .12       0     552    .045       0
  578.95     .12       0
Bank Sta=552,578.95
XS Rating Curve= 0 ,0
Exp/Cntr=0.3,0.1

Type RM Length L Ch R = 1 ,11850.8 ,473.2,459.9,448.3
XS GIS Cut Line= 3
     2322239.195      413240.253     2322810.376      413226.364
     2322924.959      413200.323
#Sta/Elev= 30
       0  648.57      32  644.32    51.9  640.66    91.9  632.31   139.8  620.73
   159.8  616.84   167.8  616.79   171.8  615.96   183.8     611   203.8  607.22
  209.17  603.69   211.8  602.21   215.8   601.4   231.7  602.09   239.7   603.7
   331.6  603.55   359.6  604.36   399.6  604.16   427.5  604.85   471.5  604.14
   491.4  605.03   511.4  604.98   543.4  606.42   594.8  610.14   618.4  613.29
   630.1  613.96   657.5  622.54   665.4  624.29   673.2  625.16   688.8  629.88
#Mann= 3 ,-1 , 0
       0     .12       0  209.17    .045       0   239.7     .12       0
Bank Sta=209.17,239.7
XS Rating Curve= 0 ,0
Exp/Cntr=0.3,0.1

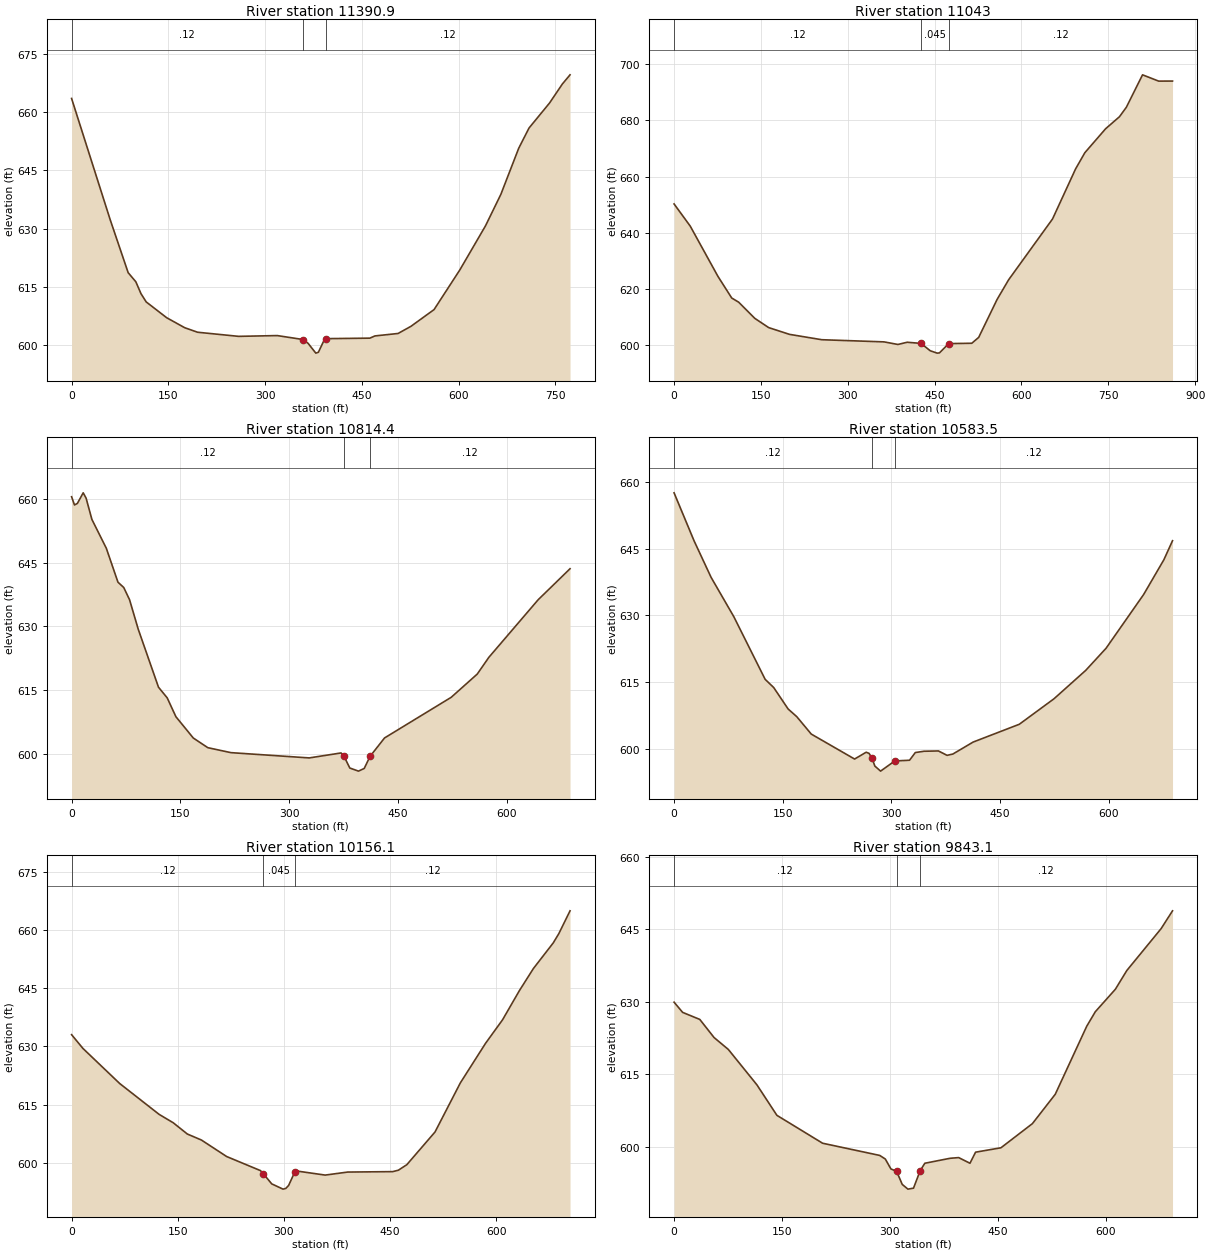
Type RM Length L Ch R = 1 ,11390.9 ,334.7,348,336.7
XS GIS Cut Line= 3
     2322298.223      413578.795     2322914.542      413497.198
     2323065.584      413497.198
#Sta/Elev= 30
       0  663.48    59.8  632.33    87.7   618.7    99.6  616.36   107.6   613.3
   115.6  611.19   147.4  607.12   175.4  604.55   195.3  603.39     259  602.33
   318.8  602.53   358.7  601.52   366.6  600.54   378.6  598.02   382.6  598.24
   390.6  601.05   394.5  601.74   462.3  601.87   470.3  602.44   506.1  603.07
     526   604.9   561.9  609.21   601.8  619.39   641.6  630.72   665.4  638.81
   693.2   650.7   709.1  655.87   740.9   662.3   760.8  667.19   772.7  669.55
#Mann= 3 ,-1 , 0
       0     .12       0   358.7    .045       0   394.5     .12       0
Bank Sta=358.7,394.5
XS Rating Curve= 0 ,0
Exp/Cntr=0.3,0.1

Type RM Length L Ch R = 1 ,11043   ,226.2,228.6,231
XS GIS Cut Line= 2
     2322394.655      413867.925     2323225.768      413643.298
#Sta/Elev= 30
       0  650.24    27.9  642.36    75.7   624.5    99.6  616.77   111.6  615.29
   139.5  609.53   163.4  606.25   199.3  603.85   255.1  601.94   362.7  601.17
   386.6  600.25   402.6  601.04   426.5  600.63   442.4  598.02   454.4  597.17
   458.4  597.26   474.3  600.56   514.2  600.68   526.1  602.76     558   616.3
   577.9  623.28   653.7  644.91   693.5  662.71   709.5  668.47   745.3  676.98
   769.3  681.27   781.2  684.65   809.1  696.17     837  693.93   860.9  693.95
#Mann= 3 ,-1 , 0
       0     .12       0   426.5    .045       0   474.3     .12       0
Bank Sta=426.5,474.3
XS Rating Curve= 0 ,0
Exp/Cntr=0.3,0.1

Type RM Length L Ch R = 1 ,10814.4 ,234.9,230.9,225.4
XS GIS Cut Line= 3
     2322457.945      414057.962     2322610.723      413998.934
      2323129.82      413932.962
#Sta/Elev= 30
       0  660.49       4  658.55       8  658.92      16  661.41      20  660.16
      28  655.15    47.9  648.35    63.9  640.38    71.9  639.12    79.9  636.25
    91.9  629.29   119.8  615.65   131.8  613.14   143.8   608.7   167.8  603.68
   187.8  601.41   219.7  600.24   327.6     599   371.5  600.17   375.5   599.4
   383.5  596.62   395.5  595.89   403.4  596.52   411.4  599.36   431.4   603.7
   523.3  613.27   559.2  618.74   575.2  622.68   643.1  636.23   687.1  643.54
#Mann= 3 ,-1 , 0
       0     .12       0   375.5    .045       0   411.4     .12       0
Bank Sta=375.5,411.4
XS Rating Curve= 0 ,0
Exp/Cntr=0.3,0.1

Type RM Length L Ch R = 1 ,10583.5 ,425.5,427.4,415.9
XS GIS Cut Line= 3
     2322520.445      414316.642     2322638.501      414238.517
     2323157.598      414066.642
#Sta/Elev= 30
       0  657.54    27.5  646.79    51.1  638.54    82.6  629.66   125.8  615.59
   137.6  613.75   157.5  608.93   169.5  607.19   189.5  603.28   249.3  597.67
   265.3   599.2   269.3  598.94   273.3  597.88   277.3  596.09   285.2  594.95
   304.8  597.24   325.2   597.4   333.2  599.13   345.1  599.42   365.1  599.49
     377   598.5     385  598.79     413  601.48   476.8  605.49   524.7  611.22
   568.6  617.62   596.6  622.58   648.5  634.67   676.4  642.47   688.4  646.77
#Mann= 3 ,-1 , 0
       0     .12       0   273.3    .045       0   304.8     .12       0
Bank Sta=273.3,304.8
XS Rating Curve= 0 ,0
Exp/Cntr=0.3,0.1

Type RM Length L Ch R = 1 ,10156.1 ,291.6,313,330.4
XS GIS Cut Line= 3
     2322633.292      414568.378      2322714.89      414518.031
     2323240.931      414212.475
#Sta/Elev= 30
       0  633.04      16   629.5    67.9  620.46   123.7  612.49   143.6  610.33
   163.5  607.43   183.4  605.88   219.1  601.62   266.8     598   270.8   597.2
   282.8  594.57   298.7  593.22   302.6   593.4   306.6  594.16   315.4  597.67
   318.5  597.88   358.3  596.84   390.1  597.62   453.7  597.73   461.7   598.1
   473.6  599.52   513.4  607.94   549.2   620.6   584.9  630.83   608.8  636.86
   632.7  644.41   652.5  650.11   680.4  656.68   688.3  659.07   704.2  664.97
#Mann= 3 ,-1 , 0
       0     .12       0   270.8    .045       0   315.4     .12       0
Bank Sta=270.8,315.4
XS Rating Curve= 0 ,0
Exp/Cntr=0.3,0.1

Type RM Length L Ch R = 1 ,9843.1  ,189,173.3,158.2
XS GIS Cut Line= 4
     2322744.404      414710.739     2323011.765      414649.975
     2323199.265      414667.337     2323395.445      414545.809
#Sta/Elev= 30
       0  629.93    11.9  627.82    35.8  626.36    55.6  622.62    75.5  620.15
   115.2  612.84     143  606.53   206.6  600.76     286  598.24   293.8  597.49
   301.6  595.44   309.5  594.95   317.3  592.25   325.2  591.27     333  591.47
   342.2  595.07   348.7  596.62     384  597.65   395.8  597.79   411.5  596.62
   419.3  598.91   454.6  599.82   498.3  604.81   530.1  610.88   573.9  624.96
   585.8  627.95   613.7   632.6   629.6  636.47   677.3  645.13   693.2  648.82
#Mann= 3 ,-1 , 0
       0     .12       0   309.5    .045       0   342.2     .12       0
Bank Sta=309.5,342.2
XS Rating Curve= 0 ,0
Exp/Cntr=0.3,0.1