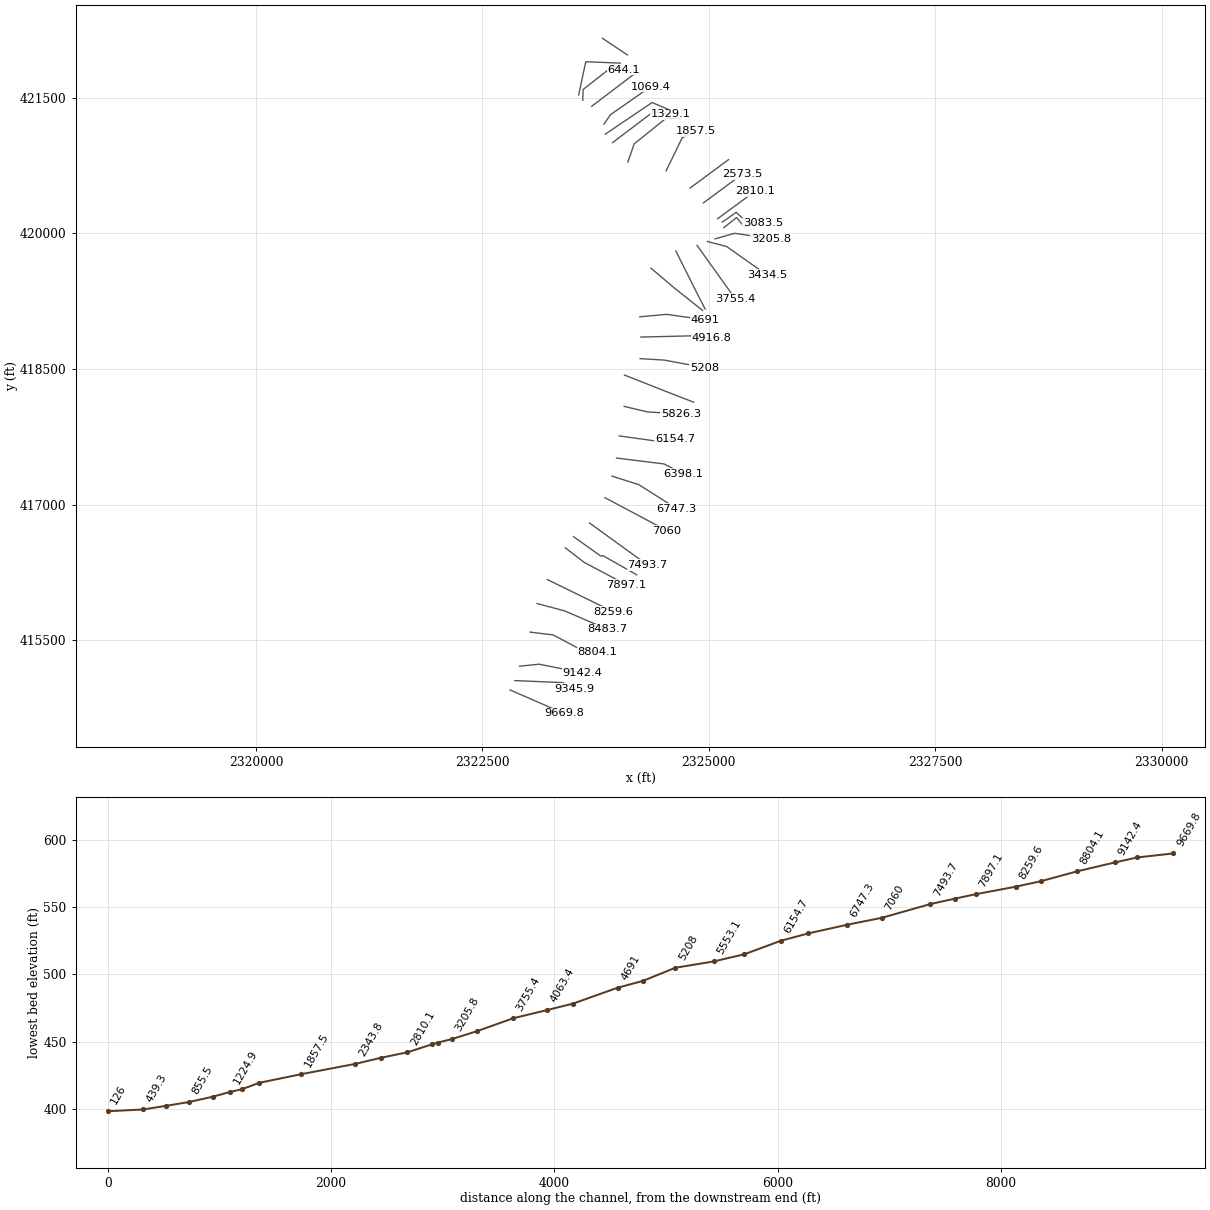
HEC-RAS study SIRJOHNSRN.prj: SIRJOHNSRN

--- SIRJOHNSRN.g01 (geometry) --- (continued)

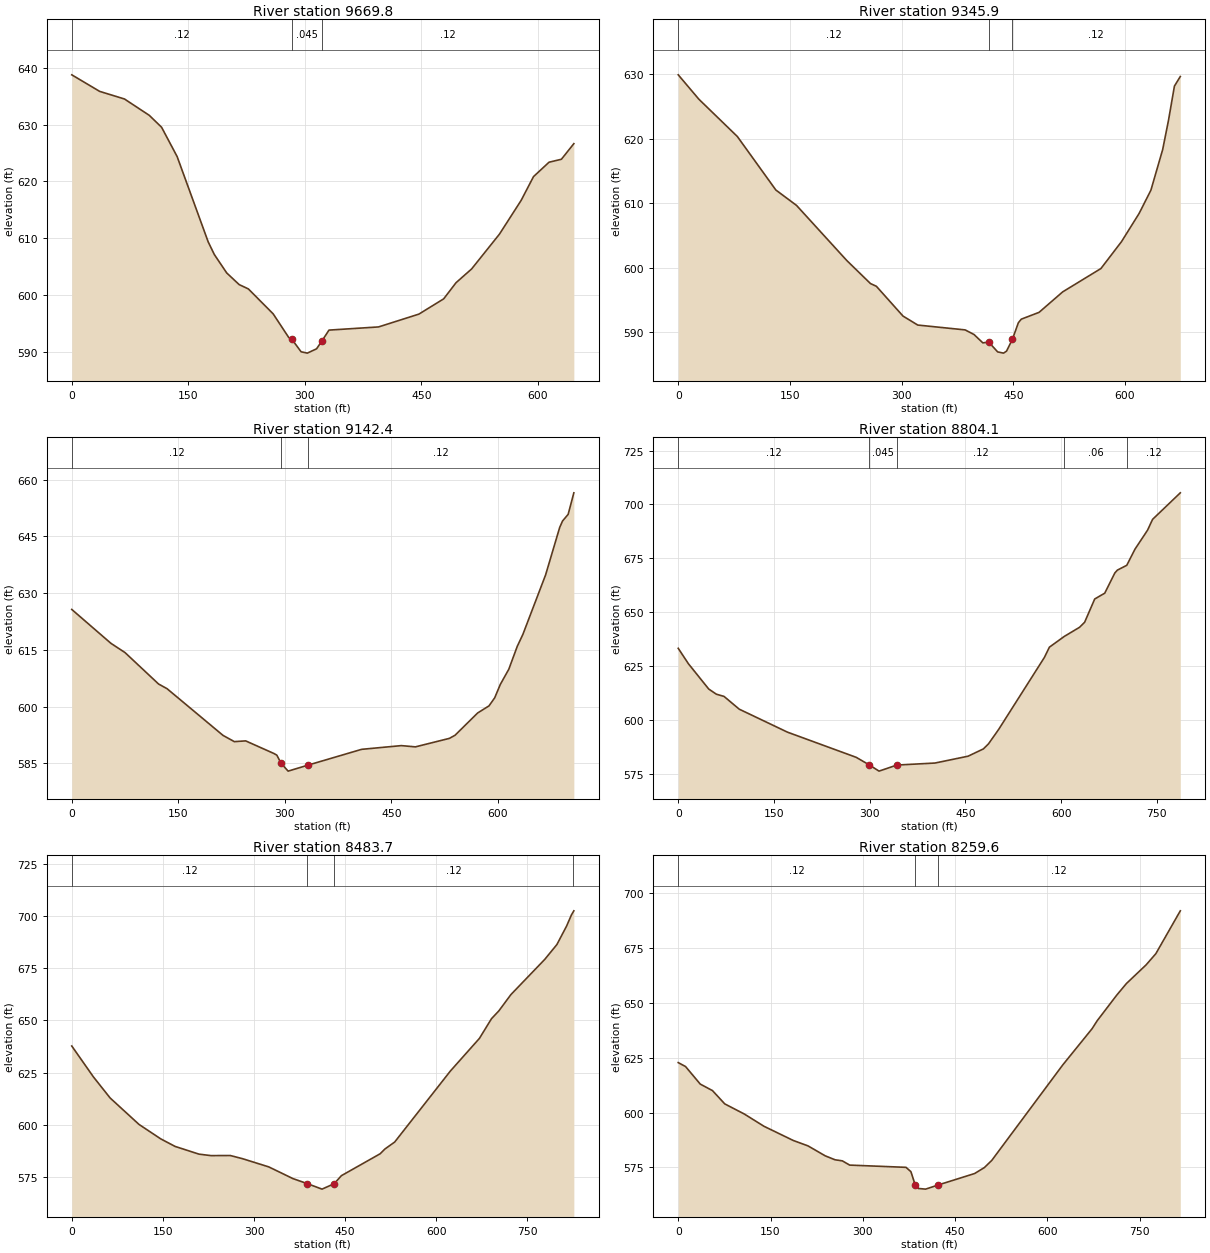
Type RM Length L Ch R = 1 ,9669.8  ,311.7,323.8,334.8
XS GIS Cut Line= 2
     2322806.904      414948.587     2323398.917      414689.906
#Sta/Elev= 30
       0  638.81    35.9  635.89    67.8  634.55    99.7  631.67   115.6  629.56
   135.6  624.39   175.5  609.37   183.4  607.13   199.4  603.87   215.4  601.82
   227.3  601.05   259.2  596.65   279.2  592.49   283.2  592.18   295.1  589.97
   303.1  589.73     315  590.49   321.5  591.79     331  593.79   394.8  594.35
   446.7  596.61   478.6   599.3   494.5  602.15   514.5  604.57   550.4  610.72
   578.3  616.67   594.2  620.86   614.2   623.4   630.1  623.92   646.1  626.67
#Mann= 3 ,-1 , 0
       0     .12       0   283.2    .045       0   321.5     .12       0
Bank Sta=283.2,321.5
XS Rating Curve= 0 ,0
Exp/Cntr=0.3,0.1

Type RM Length L Ch R = 1 ,9345.9  ,206.5,203.5,192.1
XS GIS Cut Line= 3
     2322858.987      415052.753     2323386.765      415030.184
     2323515.237      414960.739
#Sta/Elev= 30
       0  629.87    27.8  626.08    79.4  620.31   131.1  612.02   158.9  609.63
   226.4  601.09   258.2  597.52   266.1   597.1   301.9  592.48   321.7  591.09
   385.3  590.34   397.2  589.63   409.1  588.33     417  588.45     429  586.93
   436.9  586.74   440.9  587.05   448.8  588.88   456.8  591.45   460.7     592
   484.6  593.06   516.3  596.23   567.7  599.85   595.4  604.03     619  608.39
   634.8  611.99   650.6  618.28   658.5  622.86   666.4  628.12   674.3  629.61
#Mann= 3 ,-1 , 0
       0     .12       0     417    .045       0   448.8     .12       0
Bank Sta=417,448.8
XS Rating Curve= 0 ,0
Exp/Cntr=0.3,0.1

Type RM Length L Ch R = 1 ,9142.4  ,346.8,338.3,333.3
XS GIS Cut Line= 3
     2322910.182      415211.837     2323126.071      415234.176
     2323606.705      415138.475
#Sta/Elev= 30
       0   625.7    55.2  616.74      75   614.3   122.3  605.99   134.2  604.76
   213.1  592.41     229  590.77   244.9  590.97   284.8  587.63   288.8   587.2
  294.78  585.05   304.7  582.98   332.6  584.56   408.3  588.74   464.1  589.72
     484  589.39   531.8  591.63   539.8  592.46   571.6  598.34   587.6  600.22
   595.6  602.34   603.5  605.87   615.5   609.9   627.4  615.94   635.4  619.14
   667.3  634.81   687.2  647.38   691.2  649.07   699.1  650.83   707.1  656.51
#Mann= 3 ,-1 , 0
       0     .12       0  294.78    .045       0   332.6     .12       0
Bank Sta=294.78,332.6
XS Rating Curve= 0 ,0
Exp/Cntr=0.3,0.1

Type RM Length L Ch R = 1 ,8804.1  ,317,320.4,322.5
XS GIS Cut Line= 4
     2323025.654      415589.212     2323282.598      415557.962
     2323549.743      415415.196     2323770.445      415372.198
#Sta/Elev= 30
       0  633.29    15.9  626.16    47.8   614.4    59.7  612.02    71.7     611
    95.6  605.07   171.2  594.41   278.8  582.75   298.7  579.34   314.6  576.35
   342.5  579.16   402.3   580.1   454.1  583.27     478  586.64     486  588.96
     502  595.68   573.6  629.03   581.5  633.82  604.83638.8054   628.8  643.05
   636.7  645.37   652.5  656.16   668.2  658.85     684  668.21     688  669.54
  702.72671.7792   715.6  679.27   735.3  688.07   743.2  693.09   786.6  705.38
#Mann= 5 ,-1 , 0
       0     .12       0   298.7    .045       0   342.5     .12       0
  604.83     .06       0  702.72     .12       0
Bank Sta=298.7,342.5
XS Rating Curve= 0 ,0
Exp/Cntr=0.3,0.1

Type RM Length L Ch R = 1 ,8483.7  ,225.5,224.1,222.8
XS GIS Cut Line= 3
     2323103.779      415905.184     2323409.334      415823.587
     2323877.657      415621.278
#Sta/Elev= 30
       0  637.74    35.6  622.93    63.2  612.79   110.7  600.12   146.3  593.22
     170  589.58   209.5  585.86   229.3  585.16   260.9  585.21   280.7  583.72
   324.2  579.76   364.1  574.13     388  571.69   411.9  569.09   431.8  571.67
   443.8  575.54   507.6  586.05   515.5  588.35   531.5  591.67   623.2  625.74
     671  641.39   690.9  650.85   702.9  654.55   722.8  662.39   778.6   679.3
   798.5   686.4   814.5  695.28   822.4  700.59  825.79702.2681   826.4  702.57
#Mann= 4 ,-1 , 0
       0     .12       0     388    .045       0   431.8     .12       0
  825.79     .06       0
Bank Sta=388,431.8
XS Rating Curve= 0 ,0
Exp/Cntr=0.3,0.1

Type RM Length L Ch R = 1 ,8259.6  ,362.6,362.6,360
XS GIS Cut Line= 2
     2323216.626      416170.809      2323949.76      415812.272
#Sta/Elev= 30
       0  622.78    11.9  620.98    35.8  612.98    55.7     610    75.6  603.95
   107.5  599.31   139.3  593.74   187.1  587.24     211  584.78   238.9  580.25
   254.8  578.45   266.7  577.96   278.7  576.02   370.2     575   378.2  573.03
  385.12  567.05   390.1  565.36   402.1  565.06   421.6  566.87   481.7  572.17
   497.6  574.89   509.6  578.15     625  621.71   672.8  638.28   680.8  641.81
   712.6   653.5   728.5  658.85   760.4  667.33   776.3  672.46   816.1  692.02
#Mann= 3 ,-1 , 0
       0     .12       0  385.12    .045       0   421.6     .12       0
Bank Sta=385.12,421.6
XS Rating Curve= 0 ,0
Exp/Cntr=0.3,0.1

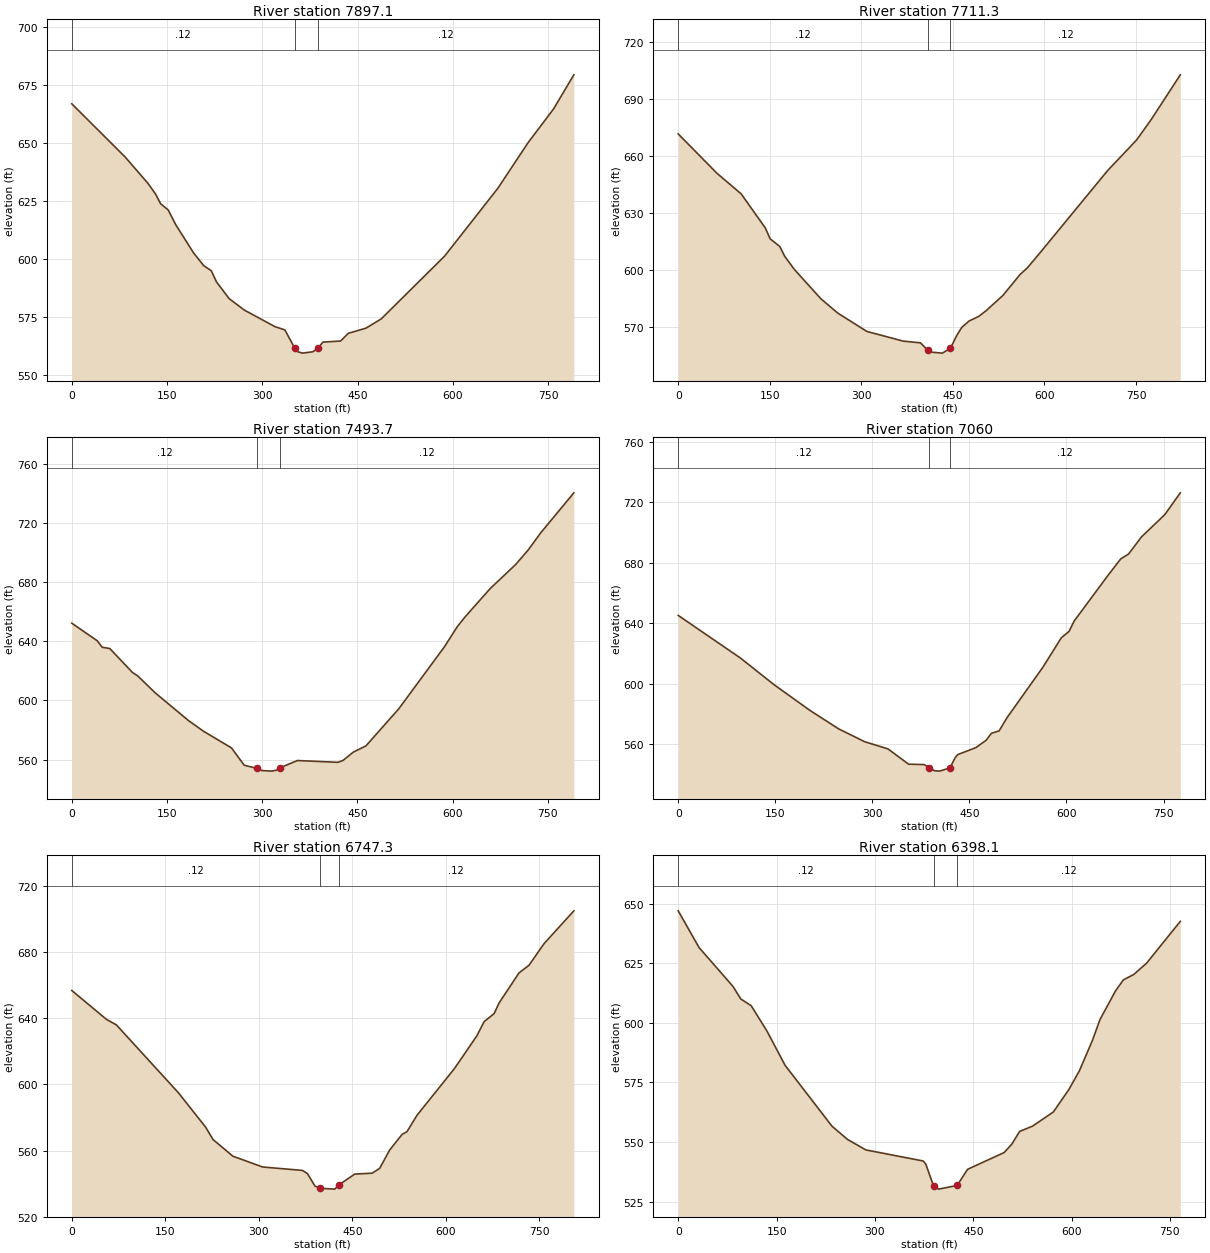
Type RM Length L Ch R = 1 ,7897.1  ,182.9,185.7,185.4
XS GIS Cut Line= 3
     2323416.279      416521.503     2323624.612      416360.045
      2324089.89      416113.517
#Sta/Elev= 30
       0  666.81    83.9   643.9   119.8  632.57   131.8  627.96   139.8  623.77
   151.8  621.07   163.7  614.68   191.7  602.57   207.7  597.09   219.6  594.88
   227.6  590.14   247.6   582.9   271.6  577.95   319.4  570.86   335.4  569.41
     351  561.48   355.3  560.02   363.3  559.41   379.3     560   387.2  561.44
   395.2  564.16   423.1  564.62   435.1  567.93     463  570.17     487  574.16
   586.7  601.18   670.5   630.4   718.3  650.13   758.2  664.59   790.1  679.27
#Mann= 3 ,-1 , 0
       0     .12       0     351    .045       0   387.2     .12       0
Bank Sta=351,387.2
XS Rating Curve= 0 ,0
Exp/Cntr=0.3,0.1

Type RM Length L Ch R = 1 ,7711.3  ,223.6,217.6,212
XS GIS Cut Line= 4
     2323506.556      416644.767     2323806.904      416431.225
     2323831.035      416435.219     2324204.473      416222.892
#Sta/Elev= 30
       0  671.54    63.4  650.83     103  640.01   142.6  622.08   150.6   616.3
   166.4  612.27   174.4  607.14   190.2  600.21   233.8   584.7   261.5  577.16
   309.1  567.53   368.5  562.44     397  561.52   408.9  557.53   412.9  556.68
   432.8  556.11     446  558.71   456.6  565.57   464.6  569.68   476.5  573.03
   492.4  575.46   504.4  578.44   532.2  586.56     560   597.5     572     601
   591.9  608.61   703.2  652.12     751  668.37   774.8  679.05   822.6  702.66
#Mann= 3 ,-1 , 0
       0     .12       0   408.9    .045       0     446     .12       0
Bank Sta=408.9,446
XS Rating Curve= 0 ,0
Exp/Cntr=0.3,0.1

Type RM Length L Ch R = 1 ,7493.7  ,428.5,433.8,438.3
XS GIS Cut Line= 2
     2323682.945       416796.33     2324323.383      416331.867
#Sta/Elev= 30
       0  652.37      40  640.48      48  636.05    59.9  635.19    95.9  618.87
   103.9  616.66   131.8  605.04   183.8  586.43   207.8   579.1   251.7  567.87
   271.7  556.13   292.1  553.98   299.7  552.52   315.6  552.14   323.6   552.9
   327.6  554.31   355.6  559.32   419.5   558.1   427.5  559.43   443.5  564.98
   463.5  569.23   515.4  594.42   587.4   636.5   607.3  649.88   619.3  656.39
   659.3  675.81   699.2     692   719.2  701.94   739.2   713.7   791.1  740.65
#Mann= 3 ,-1 , 0
       0     .12       0   292.1    .045       0   327.6     .12       0
Bank Sta=292.1,327.6
XS Rating Curve= 0 ,0
Exp/Cntr=0.3,0.1

Type RM Length L Ch R = 1 ,7060    ,313.7,312.7,310.8
XS GIS Cut Line= 2
     2323853.518      417076.278     2324538.414      416711.694
#Sta/Elev= 30
       0  645.13      96  616.94     148  599.25     204  582.05     248  569.93
     288  561.46     324   556.7     356  546.54     380  546.28     388  544.26
   395.9   542.2   403.9  541.94   419.9  544.06   427.9  550.82   431.9  552.88
   459.9  557.51   475.9  562.41   483.9  566.99   495.9  568.61   507.9  577.23
   563.9  611.02   591.9  630.25   603.9  634.52   611.9  641.42   663.9  671.54
   683.9  682.61   695.9   685.8   715.9  697.17   751.9  711.91   775.9  726.38
#Mann= 3 ,-1 , 0
       0     .12       0     388    .045       0   419.9     .12       0
Bank Sta=388,419.9
XS Rating Curve= 0 ,0
Exp/Cntr=0.3,0.1

Type RM Length L Ch R = 1 ,6747.3  ,335.9,349.2,357.9
XS GIS Cut Line= 3
     2323931.643      417314.559     2324227.216      417220.809
     2324645.185      416955.184
#Sta/Elev= 30
       0  656.74    55.7  639.28    71.6  635.95   170.9  595.02   214.7  574.21
   226.6   566.7   258.4  556.65   306.1  550.12     370  548.06     378  546.15
     390  538.66     398  537.26   421.9  536.75     428  539.18   453.9  545.84
   481.8  546.38   493.8  549.26   509.8   560.3   529.7  569.76   537.7  571.49
   553.7  581.34   613.6  609.48   649.6  629.26   661.5  637.95   677.5  642.81
   685.5  649.26   717.4  667.38   733.4  671.98   757.4  684.98   805.3  704.86
#Mann= 3 ,-1 , 0
       0     .12       0     398    .045       0     428     .12       0
Bank Sta=398,428
XS Rating Curve= 0 ,0
Exp/Cntr=0.3,0.1

Type RM Length L Ch R = 1 ,6398.1  ,243.3,243.3,245.6
XS GIS Cut Line= 3
     2323981.122       417515.08     2324505.862      417449.975
     2324716.799      417341.903
#Sta/Elev= 30
       0  646.96    31.8  631.54    83.5  615.28    95.4  610.01   111.3  607.17
   135.2  596.61     163  582.19   234.6  556.64   258.4  551.08   286.2  546.72
   373.7  542.07   377.7  540.71   389.6  531.46   397.1  530.28   425.4  531.81
   441.3  538.58     497   545.6   508.9  549.17   520.8  554.48   540.6  556.72
   572.2  562.63   595.9  572.07   611.7  579.79   631.5  592.45   643.3  601.38
     667  613.39   678.9     618   694.7  620.26   714.4  625.02   765.8  642.55
#Mann= 3 ,-1 , 0
       0     .12       0   389.6    .045       0   425.4     .12       0
Bank Sta=389.6,425.4
XS Rating Curve= 0 ,0
Exp/Cntr=0.3,0.1

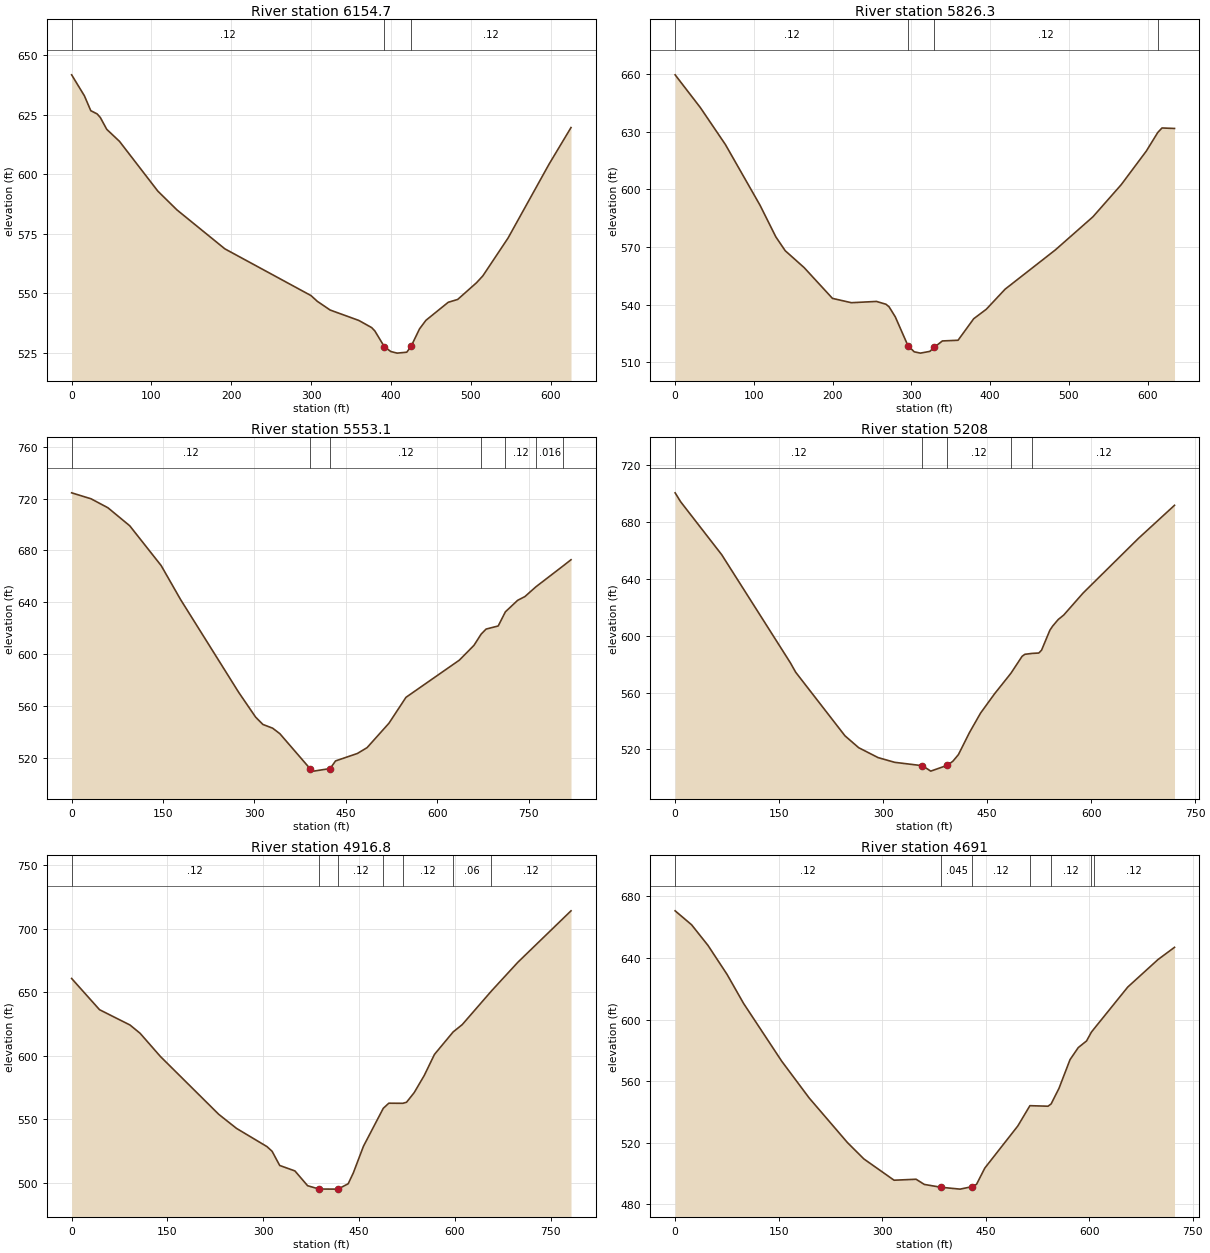
Type RM Length L Ch R = 1 ,6154.7  ,326,328.4,329.9
XS GIS Cut Line= 3
     2324009.877      417760.174     2324477.216      417694.767
     2324626.956      417729.923
#Sta/Elev= 30
       0   641.7      16  632.89      24  626.65      32  625.28      36  623.76
      44  618.82      60  613.76     108  592.89     132  584.99     192  568.65
   299.9  549.04   307.9  546.61   323.9  542.97   359.9  538.59   375.9   535.6
   379.9   534.2   391.9  527.54   399.9  525.55   407.9  524.88   419.9  525.27
   425.3   527.7   435.9  535.06   443.9  538.65   471.9  546.23   483.7  547.41
   507.4  554.46   515.3  557.34   546.8  573.18   598.1  604.15   625.7  619.56
#Mann= 3 ,-1 , 0
       0     .12       0   391.9    .045       0   425.3     .12       0
Bank Sta=391.9,425.3
XS Rating Curve= 0 ,0
Exp/Cntr=0.3,0.1

Type RM Length L Ch R = 1 ,5826.3  ,282.3,273.2,264.1
XS GIS Cut Line= 3
     2324065.758      418086.694     2324322.268      418025.496
      2324692.06      418002.059
#Sta/Elev= 30
       0  659.47      32  642.46    63.9   623.2   107.9  591.62   127.9  575.24
   139.8  568.04   163.8  559.28   199.8  543.27   223.8  541.02   255.7  541.68
   267.7  540.22   271.7  538.89   279.6  533.66   295.6  518.76   303.6   515.5
   311.5  514.81   323.5  515.72   329.1  517.86   339.4  521.14   359.3   521.5
   379.2  532.69   395.2  537.62   419.1  548.06   482.8  568.43   530.6  585.67
   566.5  602.36   598.4  619.84   612.9629.4796   618.3  631.84   634.2  631.59
#Mann= 4 ,-1 , 0
       0     .12       0   295.6    .045       0   329.1     .12       0
   612.9    .016       0
Bank Sta=295.6,329.1
XS Rating Curve= 0 ,0
Exp/Cntr=0.3,0.1

Type RM Length L Ch R = 1 ,5553.1  ,338.8,345.1,350.5
XS GIS Cut Line= 3
     2324069.284      418433.094     2324449.964      418282.603
     2324832.163      418133.171
#Sta/Elev= 30
       0  724.55    31.8  719.95    59.6     713    95.4  699.08     147  668.31
   178.8  642.12   274.2  570.42     302  551.27     314  545.58   329.9  542.72
   341.8  538.44   391.2  511.52   397.4  509.53   424.3  511.52   433.2  517.41
   469.1  523.18     485  527.69   520.9  546.56   548.8  566.55   636.4  595.27
   660.4   606.7  672.14615.3484   680.3  619.28   700.2  621.68  711.97632.5937
   732.1   641.5     744  644.38  762.04651.9326  807.32 668.286   819.7  672.84
#Mann= 7 ,-1 , 0
       0     .12       0   391.2    .045       0   424.3     .12       0
  672.14    .016       0  711.97     .12       0  762.04    .016       0
  807.32     .12       0
Bank Sta=391.2,424.3
XS Rating Curve= 0 ,0
Exp/Cntr=0.3,0.1

Type RM Length L Ch R = 1 ,5208    ,284.6,291.1,296.9
XS GIS Cut Line= 3
     2324241.539       418615.34     2324509.768      418598.413
     2324953.779      418516.382
#Sta/Elev= 30
       0  700.46     7.9  694.22    67.2  656.94     166  581.13   173.9  574.31
     245   529.6   264.8  521.24   292.7   514.3   316.7  510.97   356.7  508.59
   368.7  504.78   392.6  508.88   400.6  511.73   408.6  516.39   424.6  531.94
   440.6  545.62   460.6  559.06  484.29573.5599   500.5  585.54   504.5  586.93
  515.12587.5596   524.5  587.82   528.5  589.78   540.5  603.83   544.5  606.74
   552.5  611.35   560.5  614.52   588.4  629.98   668.3  668.44   720.3  691.69
#Mann= 5 ,-1 , 0
       0     .12       0   356.7    .045       0   392.6     .12       0
  484.29    .016       0  515.12     .12       0
Bank Sta=356.7,392.6
XS Rating Curve= 0 ,0
Exp/Cntr=0.3,0.1

Type RM Length L Ch R = 1 ,4916.8  ,230.5,225.8,220.6
XS GIS Cut Line= 3
     2324250.133      418853.882     2324802.216      418866.903
     2325030.081      418838.257
#Sta/Elev= 30
       0  660.84    43.7  636.26    91.4  624.21   107.3  617.65     139  599.44
   230.4  553.88   258.2  542.82   305.9  528.48   313.9   524.8   325.8  513.64
   349.6  509.35   369.5   497.7   387.3   495.1   413.2  495.02   417.3  495.14
     433  499.23     441  507.71   456.9  528.76  487.95558.6288   496.6  562.66
  518.61 562.578   524.4  563.42   536.4  571.02   552.2  584.58   568.1  601.07
  597.37618.7773   611.6  624.53  657.18650.9226   698.7  673.62   781.9   714.1
#Mann= 7 ,-1 , 0
       0     .12       0   387.3    .045       0   417.3     .12       0
  487.95    .016       0  518.61     .12       0  597.37     .06       0
  657.18     .12       0
Bank Sta=387.3,417.3
XS Rating Curve= 0 ,0
Exp/Cntr=0.3,0.1

Type RM Length L Ch R = 1 ,4691    ,412.9,396.4,377.9
XS GIS Cut Line= 3
       2324238.5      419078.345     2324534.508      419104.923
     2324956.383      419045.028
#Sta/Elev= 30
       0   670.5    23.8  661.47    47.6  648.06    75.3   629.2    99.1  610.46
   154.5  572.88   194.2  549.06   249.6  520.15   273.4  509.54   317.1  495.74
     349  496.37   360.9  493.01   384.8  491.18   412.7  489.96   430.6   491.6
   436.6  493.11   448.5  503.59   496.3   530.9  513.87544.0959   540.1  543.75
  544.56545.2188     556  555.36     572  573.97   583.9  581.78   595.9  586.09
  602.93591.8054  606.11593.6112   655.6  621.06   699.4   638.9   723.3  646.82
#Mann= 7 ,-1 , 0
       0     .12       0   384.8    .045       0   430.6     .12       0
  513.87    .016       0  544.56     .12       0  602.93     .06       0
  606.11     .12       0
Bank Sta=384.8,430.6
XS Rating Curve= 0 ,0
Exp/Cntr=0.3,0.1

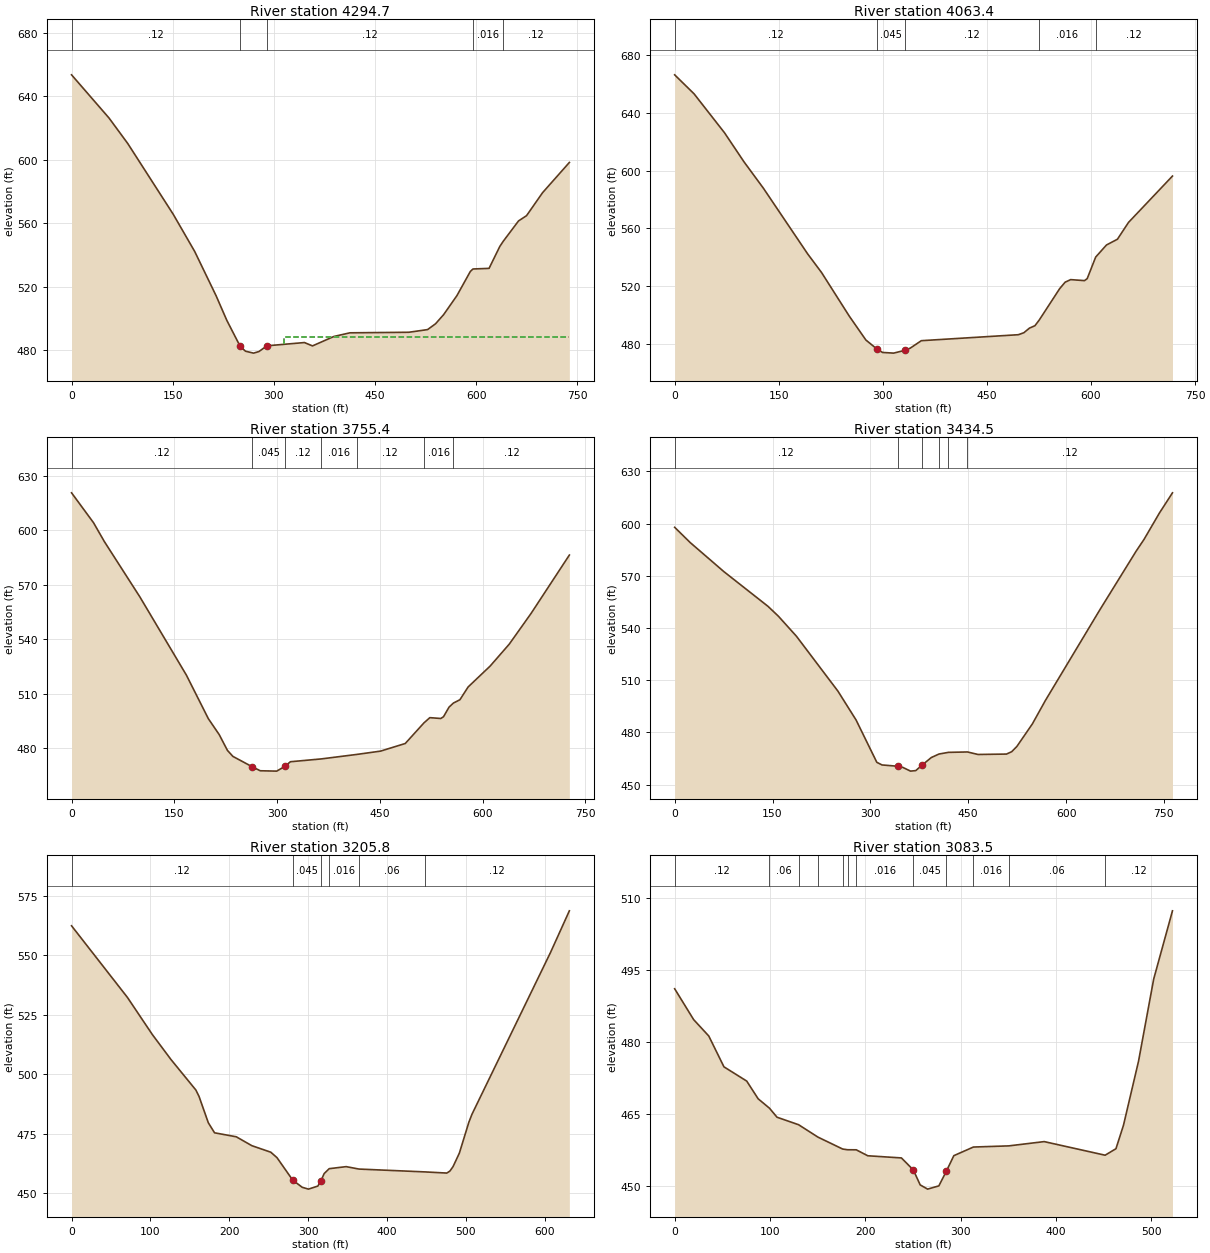
Type RM Length L Ch R = 1 ,4294.7  ,243.2,231.3,219.3
XS GIS Cut Line= 3
     2324361.331      419616.642     2324615.237      419400.496
     2324931.643      419147.892
#Sta/Elev= 30
       0  653.55    55.6  626.33    83.4  610.25   150.8   565.7   182.6   542.3
   214.4  514.36   230.2  498.94   250.1  482.49     258  479.44   269.9  478.23
   277.9  479.22   289.8  482.85   345.4  484.89   357.3  482.78     389  488.71
   412.8  491.02   500.2  491.37     528  493.05   539.8   496.7   551.8  502.46
   571.6   514.5   591.4  529.66  595.34 531.236   619.2  531.62   635.1   545.4
  640.05548.5888   662.9  561.51   674.8  564.83   698.6  579.32   738.3  598.35
#Mann= 5 ,-1 , 0
       0     .12       0   250.1    .045       0   289.8     .12       0
  595.34    .016       0  640.05     .12       0
#XS Ineff= 2 , 0
                          315.38          488.43
Permanent Ineff=
       F       F
Bank Sta=250.1,289.8
XS Rating Curve= 0 ,0
Exp/Cntr=0.3,0.1

Type RM Length L Ch R = 1 ,4063.4  ,302.3,308,311.3
XS GIS Cut Line= 3
      2324636.07      419805.444     2324865.237      419348.413
     2324958.987      419164.819
#Sta/Elev= 30
       0  666.46      28  653.26    71.9  626.23    99.9  606.13   127.8  587.86
   191.7  542.24   211.7  529.34   251.6  499.13   275.6  482.52   291.6  476.25
   299.6  473.91   315.6  473.44   332.3  475.46   339.5  476.91   355.5  482.07
   495.3  486.21   503.3  487.61   511.3  490.79   519.2  492.46  525.45496.4335
   554.9   518.2   562.8  522.67   570.7  524.42   590.6  523.73   594.5   525.1
  606.75540.0745   622.3  548.44   638.1  552.44     654  564.07   717.4  596.25
#Mann= 5 ,-1 , 0
       0     .12       0   291.6    .045       0   332.3     .12       0
  525.45    .016       0  606.75     .12       0
Bank Sta=291.6,332.3
XS Rating Curve= 0 ,0
Exp/Cntr=0.3,0.1

Type RM Length L Ch R = 1 ,3755.4  ,310.2,320.9,330.5
XS GIS Cut Line= 2
     2324870.445      419867.944     2325292.724      419276.428
#Sta/Elev= 30
       0  620.67      32  604.24    47.9   593.8    99.8  563.27   167.7  520.17
   199.7   496.2   215.6  487.39   227.6   478.7   235.6  475.39   263.6  469.72
   275.5  467.48   299.5  467.28   311.5   469.9   319.5  472.45  364.41474.0005
  416.18476.4686   451.2  478.31   487.2  482.51  514.59493.9078   523.1  496.75
   539.1  496.29   543.1  497.28   551.1  502.54  557.55504.8152     567  506.62
     579  513.67     611  525.13   638.9   537.2   670.9   554.2   726.8  586.37
#Mann= 7 ,-1 , 0
       0     .12       0   263.6    .045       0   311.5     .12       0
  364.41    .016       0  416.18     .12       0  514.59    .016       0
  557.55     .12       0
Bank Sta=263.6,311.5
XS Rating Curve= 0 ,0
Exp/Cntr=0.3,0.1

Type RM Length L Ch R = 1 ,3434.5  ,214.2,228.8,242.5
XS GIS Cut Line= 3
     2324985.029      419910.913     2325196.477       419855.87
     2325641.089      419541.357
#Sta/Elev= 30
       0  597.87    23.8  589.11    75.5  572.38     143  552.48   158.9  546.83
   186.7  535.26   250.3  503.71   278.1  487.14   309.9  462.82   317.9  461.31
   341.7  460.57   349.7  459.91   361.6  457.76   369.6  458.06   379.1  461.15
   393.4  465.57  405.22467.5877  419.56468.5416  448.82468.7682     465  467.33
   508.7  467.56   516.6  468.92   524.6  471.95   548.4  484.94   568.3  498.36
   651.8  550.47   707.4  584.16   719.4  590.87   743.2  606.14   763.1  617.68
#Mann= 6 ,-1 , 0
       0     .12       0   341.7    .045       0   379.1     .12       0
  405.22     .06       0  419.56    .016       0  448.82     .12       0
Bank Sta=341.7,379.1
XS Rating Curve= 0 ,0
Exp/Cntr=0.3,0.1

Type RM Length L Ch R = 1 ,3205.8  ,145.6,122.3,95
XS GIS Cut Line= 3
     2325068.796      419940.427     2325284.942      420001.625
     2325687.285      419943.031
#Sta/Elev= 30
       0  562.47    70.9  532.35   102.5  516.74   126.1  506.26   157.6  493.47
   161.6   490.8   173.4  479.71   181.3  475.48   208.9   473.8   228.6  470.07
   252.6  467.33   260.5  465.03   280.4  455.61   292.4  452.59   300.4  451.81
   312.3   453.1   316.3  455.37   320.3  458.34  326.67460.4044   348.2  461.26
  364.47460.2424  448.03 459.046   475.8  458.56   479.8  459.42   483.7  461.27
   491.7  466.92   503.7  479.85   507.7  483.26   607.3  551.26   631.2  568.76
#Mann= 6 ,-1 , 0
       0     .12       0   280.4    .045       0   316.3     .12       0
  326.67    .016       0  364.47     .06       0  448.03     .12       0
Bank Sta=280.4,316.3
XS Rating Curve= 0 ,0
Exp/Cntr=0.3,0.1

Type RM Length L Ch R = 1 ,3083.5  ,52.5,53.5,61.3
XS GIS Cut Line= 4
     2325166.814      420064.631     2325306.571       420176.61
     2325389.036      420076.784     2325599.974      420111.506
#Sta/Elev= 30
       0  491.02    19.9   484.6    35.8  481.18    51.7  474.76    75.6  471.79
    87.6   468.1   99.47466.1382   107.4  464.26  130.03462.6974   150.4 460.108
  176.27 457.633  181.45457.4826  190.53457.4715   202.6  456.23   237.9  455.78
   250.4  453.28   257.6  450.16   265.4  449.28   277.2  449.96     285  452.99
   292.9  456.25  313.43458.0488  350.63  458.29   387.7  459.18  451.64456.3472
     463   457.7   470.9  462.59   486.7  475.94   502.6  493.05   522.3  507.26
#Mann= 12 ,-1 , 0
       0     .12       0   99.47     .06       0  130.03     .08       0
   150.4     .06       0  176.27    .016       0  181.45     .06       0
  190.53    .016       0   250.4    .045       0     285     .12       0
  313.43    .016       0  350.63     .06       0  451.64     .12       0
Bank Sta=250.4,285
XS Rating Curve= 0 ,0
Exp/Cntr=0.3,0.1

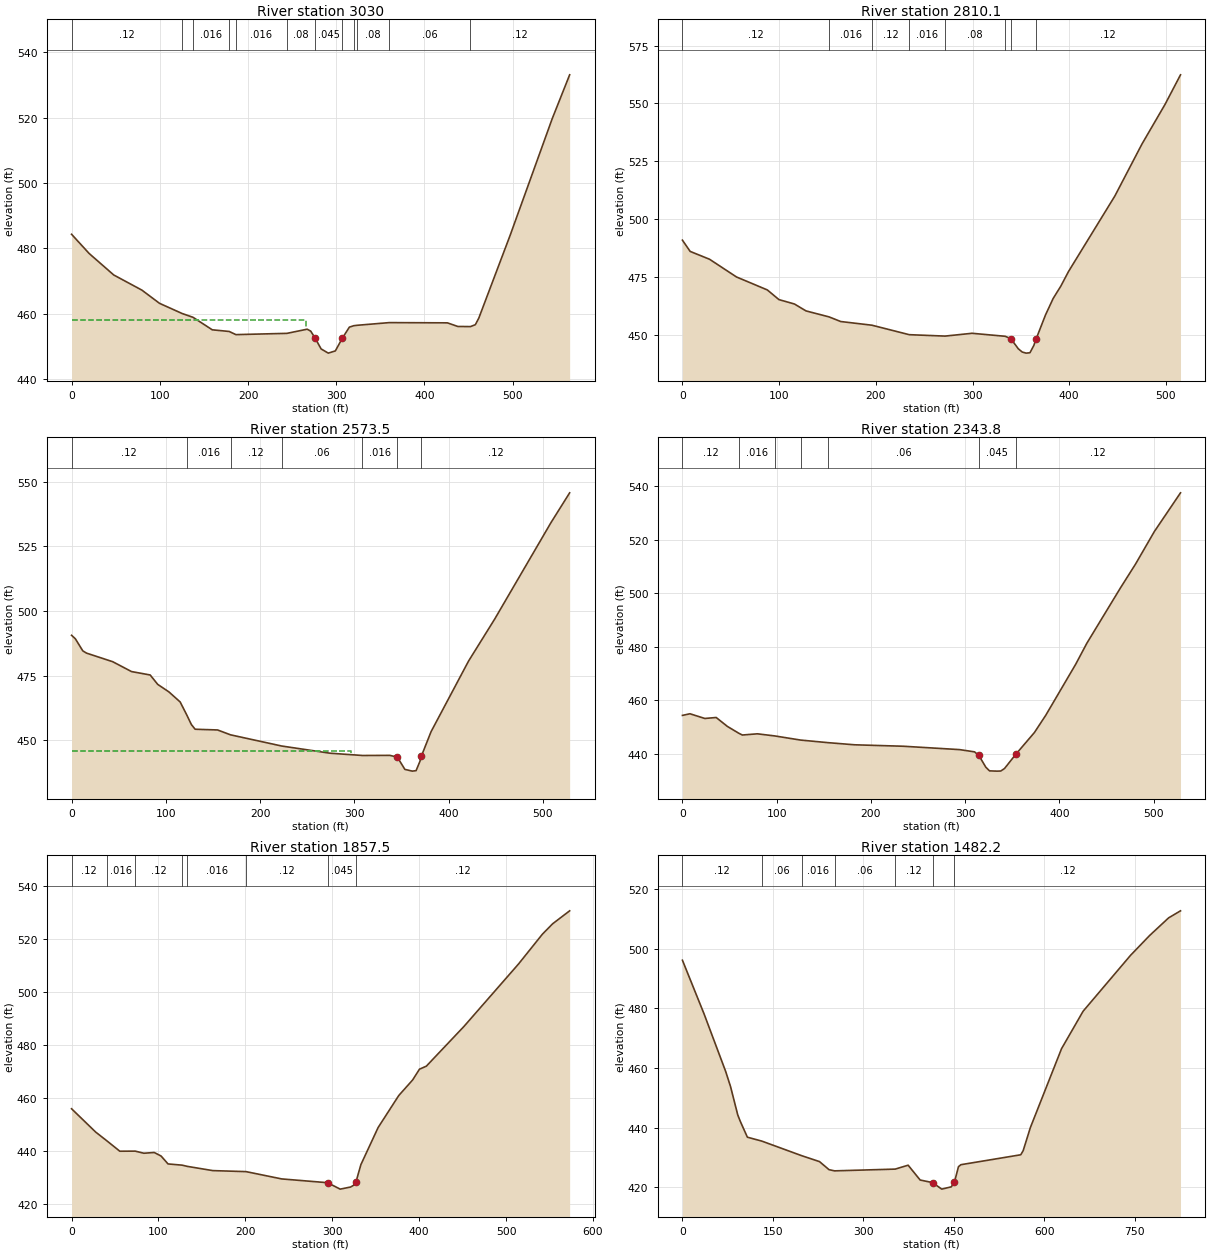
Type RM Length L Ch R = 1 ,3030    ,172.7,219.9,261.7
XS GIS Cut Line= 4
     2325149.453      420125.395     2325302.231      420233.902
     2325422.022      420122.791      2325632.96      420157.513
#Sta/Elev= 30
       0   484.3    19.9  478.43    47.8  471.85    79.7  467.22    99.7  463.18
  125.46460.0505  137.63458.9113   159.5  455.08  178.66454.5744  186.28453.6092
  244.14453.9958   267.1  455.27   271.1  454.67  275.76 452.672   282.9  449.23
     291  447.95     299  448.63   306.9   452.5   314.9   455.9  319.97456.3401
  323.44456.4568   360.1457.2815     426  457.21   437.9   456.1   452.2456.0677
   457.7  456.65   461.6  458.64   497.2  484.02   544.8  519.62   564.6  533.06
#Mann= 12 ,-1 , 0
       0     .12       0  125.46     .08       0  137.63    .016       0
  178.66     .12       0  186.28    .016       0  244.14     .08       0
  275.76    .045       0   306.9     .08       0  319.97    .016       0
  323.44     .08       0   360.1     .06       0   452.2     .12       0
#XS Ineff= 2 , 0
          265.73  457.98
Permanent Ineff=
       F       F
Bank Sta=275.76,306.9
XS Rating Curve= 0 ,0
Exp/Cntr=0.3,0.1

Type RM Length L Ch R = 1 ,2810.1  ,236.3,236.6,236.6
XS GIS Cut Line= 2
     2325097.478       420163.77     2325512.842      420468.458
#Sta/Elev= 30
       0  490.88       8  486.02      28  482.64    55.9  474.97    87.8  469.36
    99.8  465.18   115.8  463.28   127.8  460.29  151.61 457.705   163.7   455.7
  196.06454.0985  234.54450.0068  271.61449.3955   299.5  450.61  333.87449.3091
   339.6  448.28   347.4  443.89   351.4  442.51   355.4  442.03   359.4  442.19
   363.4  445.35   365.7  448.07   375.4  458.46   383.4  465.67   391.3  470.99
   399.3  477.34   447.2  509.98   475.2  532.43   499.2  549.68   515.1  562.39
#Mann= 8 ,-1 , 0
       0     .12       0  151.61    .016       0  196.06     .12       0
  234.54    .016       0  271.61     .08       0  333.87     .12       0
   339.6    .045       0   365.7     .12       0
Bank Sta=339.6,365.7
XS Rating Curve= 0 ,0
Exp/Cntr=0.3,0.1

Type RM Length L Ch R = 1 ,2573.5  ,230.8,229.8,228.7
XS GIS Cut Line= 2
     2324941.228      420338.684     2325365.707      420653.354
#Sta/Elev= 30
       0  490.57       4  489.24    11.9  484.55    15.9  483.67    43.7  480.34
    63.6  476.53    83.4  475.21    91.4  471.57   103.3  468.65   115.2  464.76
  121.94459.9352   127.1  456.02   131.1   454.2   154.9  453.92  168.64452.0346
  222.92447.7017   274.1  444.92  308.58444.0371   337.7  444.08   345.6   443.4
   353.6  438.65   361.5  437.98   365.5  438.17   369.5   441.7  370.99  443.68
   381.4  453.27   421.1  480.56   448.9  496.87   508.5  534.15   528.4  545.74
#Mann= 7 ,-1 , 0
       0     .12       0  121.94    .016       0  168.64     .12       0
  222.92     .06       0  308.58    .016       0   345.6    .045       0
  370.99     .12       0
#XS Ineff= 2 , 0
          295.98  445.78
Permanent Ineff=
       F       F
Bank Sta=345.6,370.99
XS Rating Curve= 0 ,0
Exp/Cntr=0.3,0.1

Type RM Length L Ch R = 1 ,2343.8  ,470.2,486.3,501.4
XS GIS Cut Line= 2
     2324794.092      420502.746     2325218.572      420817.416
#Sta/Elev= 30
       0  454.29       8   454.9    23.8  453.14    35.8  453.51    47.7  450.17
   59.73447.6273    63.6  446.95    79.5   447.4   97.87446.6137  125.37445.0598
  154.26444.0981   182.8  443.29   234.4  442.75     294  441.49   309.9  440.65
  314.46439.3099   321.8  434.94   325.8  433.54   333.7  433.44   337.7  433.48
   341.7  434.42   353.6  439.71   373.4  447.88   385.4  454.31   417.2  473.42
   429.1  481.33   464.8  502.06   480.7  510.92   500.6  523.06   528.4  537.57
#Mann= 7 ,-1 , 0
       0     .12       0   59.73    .016       0   97.87     .06       0
  125.37    .016       0  154.26     .06       0  314.46    .045       0
   353.6     .12       0
Bank Sta=314.46,353.6
XS Rating Curve= 0 ,0
Exp/Cntr=0.3,0.1

Type RM Length L Ch R = 1 ,1857.5  ,387.8,375.3,361.3
XS GIS Cut Line= 3
     2324528.467      420692.416     2324706.853      421059.604
     2324856.592      421128.614
#Sta/Elev= 30
       0     456    27.7  447.24   40.62443.9289    55.5  440.02   73.23440.0528
    83.2  439.26    95.1  439.54     103  438.21     111  435.23  127.22434.7716
  133.05434.3219   162.5  432.72  200.76432.3381   241.8  429.59   294.5  428.17
   309.1  425.75     321  426.54     325  427.29  327.29  428.52   332.9  434.97
   352.7  448.92   376.5  460.99   392.4  466.82   400.3  470.89   408.2  472.03
   451.4  486.95   514.2  510.46   541.7  521.69   553.5  525.62   573.1   530.5
#Mann= 8 ,-1 , 0
       0     .12       0   40.62    .016       0   73.23     .12       0
  127.22     .06       0  133.05    .016       0  200.76     .12       0
   294.5    .045       0  327.29     .12       0
Bank Sta=294.5,327.29
XS Rating Curve= 0 ,0
Exp/Cntr=0.3,0.1

Type RM Length L Ch R = 1 ,1482.2  ,153.4,153.1,151.8
XS GIS Cut Line= 4
     2324106.592       420790.94     2324176.037      420990.593
     2324528.467      421275.315     2324689.926      421271.843
#Sta/Elev= 30
       0  496.18    35.9  478.16    71.8  458.81    79.8  453.77    91.7   444.3
    95.7  442.23   107.7  436.79  131.68435.4748  198.21 430.552   227.3   428.6
   243.2  425.88  252.43425.4901  352.84426.0778   374.3  427.39   394.2  422.42
     415  421.54     430  419.36   445.9  420.13  451.13  421.75   457.8  426.89
   461.8  427.56   561.1  430.89   565.1  432.29     577  440.01   628.7  466.49
   664.5  479.07   743.2  497.84   774.8  504.48   806.3   510.4     826  512.76
#Mann= 7 ,-1 , 0
       0     .12       0  131.68     .06       0  198.21    .016       0
  252.43     .06       0  352.84     .12       0     415    .045       0
  451.13     .12       0
Bank Sta=415,451.13
XS Rating Curve= 0 ,0
Exp/Cntr=0.3,0.1

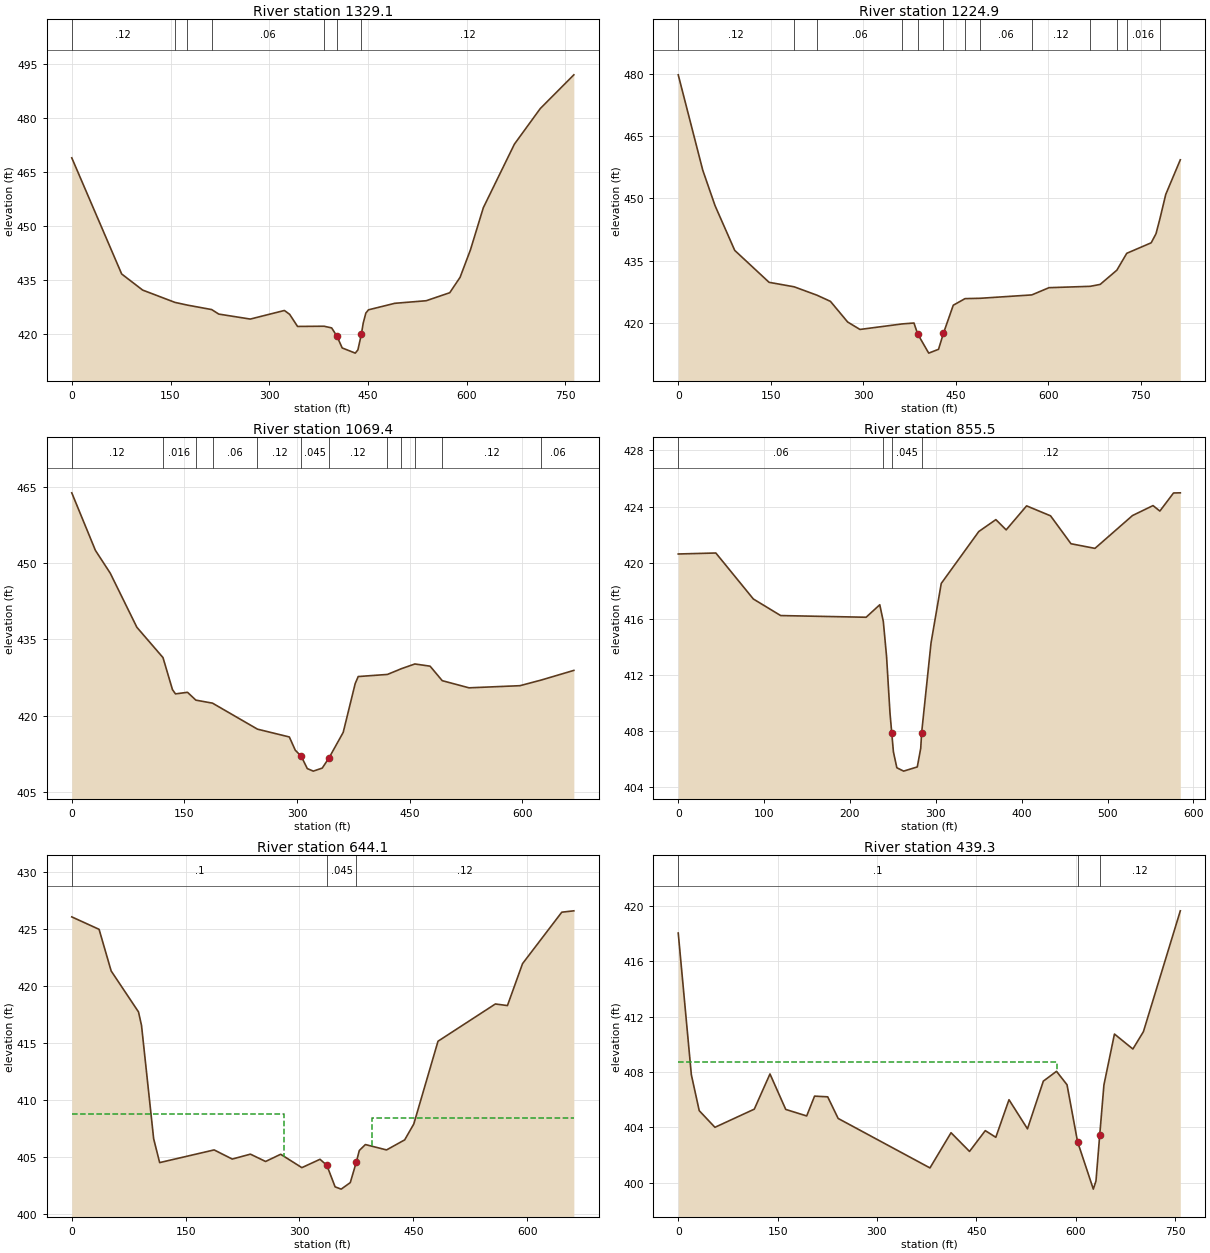
Type RM Length L Ch R = 1 ,1329.1  ,106.5,104.1,102.4
XS GIS Cut Line= 3
     2323936.454      421004.482     2324387.842      421346.496
     2324582.287      421318.718
#Sta/Elev= 30
       0  468.96    75.8  436.66   107.7  432.18  156.77428.7574  175.63428.0042
  212.55 426.762   223.3  425.51   271.2  424.12     323  426.51     331  425.43
     343  422.07   383.2  422.13   394.8  421.66   402.8  419.36   410.8  416.09
   430.7  414.65   434.7  415.57     440  419.97   442.7  422.96   446.7  425.78
   450.7  426.69   490.6   428.5   538.4  429.22   574.2  431.45   589.9  435.74
   605.6  443.36   625.2  455.09   672.4  472.76   711.7  482.66   762.7  492.04
#Mann= 7 ,-1 , 0
       0     .12       0  156.77     .06       0  175.63    .016       0
  212.55     .06       0   383.2     .12       0   402.8    .045       0
     440     .12       0
Bank Sta=402.8,440
XS Rating Curve= 0 ,0
Exp/Cntr=0.3,0.1

Type RM Length L Ch R = 1 ,1224.9  ,154.2,155.5,155.9
XS GIS Cut Line= 3
     2323856.592      421098.232     2324373.954      421448.927
     2324547.565      421374.274
#Sta/Elev= 30
       0  479.77    39.8  456.76    59.7  448.22    91.6  437.44   147.3  429.74
  187.88 428.663  224.89426.6404   246.8  425.15   274.7  420.17   294.6  418.38
  363.51419.7176   382.2  419.93  388.17   417.3   406.1  412.67     422  413.59
     430  417.47   445.9  424.22  465.01425.8121  489.94425.8943  573.23426.7061
   601.1  428.45  667.98428.7777   684.1  429.24  711.12  432.67  727.18436.7373
   766.8  439.27   774.6  441.46  780.91445.0547   790.4  450.94     814  459.28
#Mann= 13 ,-1 , 0
       0     .12       0  187.88    .016       0  224.89     .06       0
  363.51     .12       0  388.17    .045       0     430     .12       0
  465.01     .08       0  489.94     .06       0  573.23     .12       0
  667.98     .06       0  711.12     .12       0  727.18    .016       0
  780.91     .12       0
Bank Sta=388.17,430
XS Rating Curve= 0 ,0
Exp/Cntr=0.3,0.1

Type RM Length L Ch R = 1 ,1069.4  ,212.7,213.9,215.1
XS GIS Cut Line= 3
     2323842.704      421209.343     2323913.884       421313.51
     2324358.329      421624.274
#Sta/Elev= 30
       0  463.86    31.5  452.53    51.2  448.06    86.7   437.4  121.44431.4437
   134.1  425.13   138.1   424.3   154.1  424.61  165.23423.0674   187.4 422.475
  247.25417.3576   289.7  415.82   297.6  413.22   305.6     412   313.6   409.6
   321.6   409.1   333.5   409.7   342.6  411.73   361.4  416.72   377.4  426.34
   381.4  427.71  420.37428.1266  438.97429.2616  456.82430.1843   477.1  429.75
  493.27 426.899   528.9  425.49   596.7  425.91   624.9427.0143   668.5  428.92
#Mann= 12 ,-1 , 0
       0     .12       0  121.44    .016       0  165.23     .12       0
   187.4     .06       0  247.25     .12       0   305.6    .045       0
   342.6     .12       0  420.37     .08       0  438.97     .06       0
  456.82     .08       0  493.27     .12       0   624.9     .06       0
Bank Sta=305.6,342.6
XS Rating Curve= 0 ,0
Exp/Cntr=0.3,0.1

Type RM Length L Ch R = 1 ,855.5   ,210.7,211.4,212.6
XS GIS Cut Line= 2
     2323707.287       421407.26     2324172.565      421761.427
#Sta/Elev= 30
       0  420.62    43.8  420.69    87.5  417.41   119.3  416.23   218.8  416.11
   234.7     417  238.84415.8074   242.6  413.32   246.6  409.28   248.7  407.83
   250.6  406.51   254.6  405.38   262.5  405.14   278.4  405.44   282.4  406.77
  283.44  407.86   294.4  414.28   306.3  418.52     350  422.22   369.9  423.07
   381.9  422.34   405.7  424.05   433.6  423.34   457.4  421.35   485.3  421.02
     529  423.36   552.9  424.07   560.9  423.68   576.8  424.97   584.7  424.98
#Mann= 4 ,-1 , 0
       0     .06       0  238.84     .12       0   248.7    .045       0
  283.44     .12       0
Bank Sta=248.7,283.44
XS Rating Curve= 0 ,0
Exp/Cntr=0.3,0.1

Type RM Length L Ch R = 1 ,644.1   ,225.9,204.8,183.4
XS GIS Cut Line= 4
     2323608.644      421472.909     2323612.117        421592.7
     2323941.116      421851.363     2324058.297      421813.186
#Sta/Elev= 30
       0  426.03      36  424.94    51.9   421.3    87.9  417.72    91.9  416.54
   107.9  406.62   115.8  404.53   187.6  405.64   211.5  404.84   235.4  405.27
   255.4  404.63   275.3  405.26   303.2  404.09   327.1  404.82   336.1   404.3
     347  402.41     355  402.21     367  402.78   374.9  404.56   378.9  405.59
   386.9  406.11   414.8  405.64   438.7  406.52   450.7  407.91   482.6  415.15
   558.2  418.41   574.1  418.27     594  421.94   645.7  426.44   661.6  426.56
#Mann= 3 ,-1 , 0
       0      .1       0   336.1    .045       0   374.9     .12       0
#XS Ineff= 2 , 0
          280.29  408.77  395.87          408.46
Permanent Ineff=
       F       F
Bank Sta=336.1,374.9
XS Rating Curve= 0 ,0
Exp/Cntr=0.3,0.1

Type RM Length L Ch R = 1 ,439.3   ,331,313.3,295.5
XS GIS Cut Line= 3
      2323563.19       421532.26     2323641.631      421899.992
     2324023.259       421884.69
#Sta/Elev= 30
       0  418.03    19.8   407.8    31.7  405.21    55.4  404.01   114.8  405.32
   138.5  407.86   162.3   405.3   193.9  404.83   205.8  406.26   225.6  406.21
   241.4  404.65     380  401.08   411.8  403.62   439.7  402.27   463.5  403.77
   479.4  403.29   499.3     406   527.2   403.9   551.1  407.34     571  408.05
   586.9  407.08   602.8  402.97   626.6  399.55   630.6  400.14   636.2  403.42
   642.6  407.07   658.5  410.74   686.3  409.66   702.2  410.91   757.9  419.63
#Mann= 3 , 0 , 0
       0      .1       0   602.8    .045       0   636.2     .12       0
#XS Ineff= 2 , 0
          572.02  408.71
Permanent Ineff=
       F       F
Bank Sta=602.8,636.2
XS Rating Curve= 0 ,0
Exp/Cntr=0.3,0.1

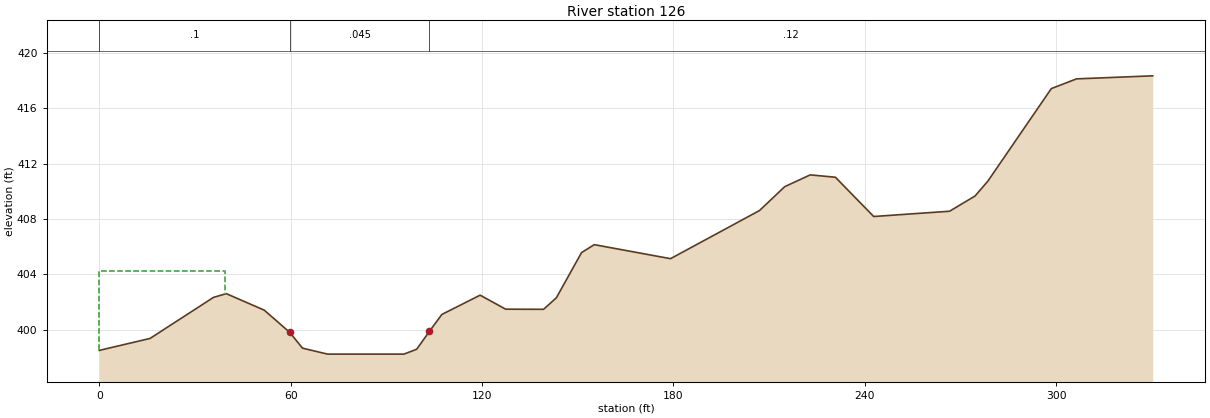
Type RM Length L Ch R = 1 ,126     ,125.9,126,126.1
XS GIS Cut Line= 2
     2323827.079      422158.996     2324101.384      421974.968
#Sta/Elev= 30
       0  398.53    15.9  399.39    35.8  402.35    39.8  402.62    51.7  401.43
    59.7  399.83    63.7  398.69    71.6  398.26    95.5  398.26    99.5  398.61
   103.5   399.9   107.4  401.12   119.4  402.51   127.4   401.5   139.3  401.49
   143.3  402.32   151.2  405.58   155.2  406.15   179.1  405.14     207  408.61
   214.9  410.33   222.9  411.18   230.8  411.01   242.8  408.18   266.6  408.56
   274.6  409.66   278.6  410.73   298.5   417.4   306.4   418.1   330.3  418.32
#Mann= 3 , 0 , 0
       0      .1       0    59.7    .045       0   103.5     .12       0
#XS Ineff= 2 , 0
           39.54  404.25
Permanent Ineff=
       F       F
Bank Sta=59.7,103.5
XS Rating Curve= 0 ,0
Exp/Cntr=0.3,0.1

Chan Stop Cuts=-1
Use User Specified Reach Order=0
Composite Channel Slope=5